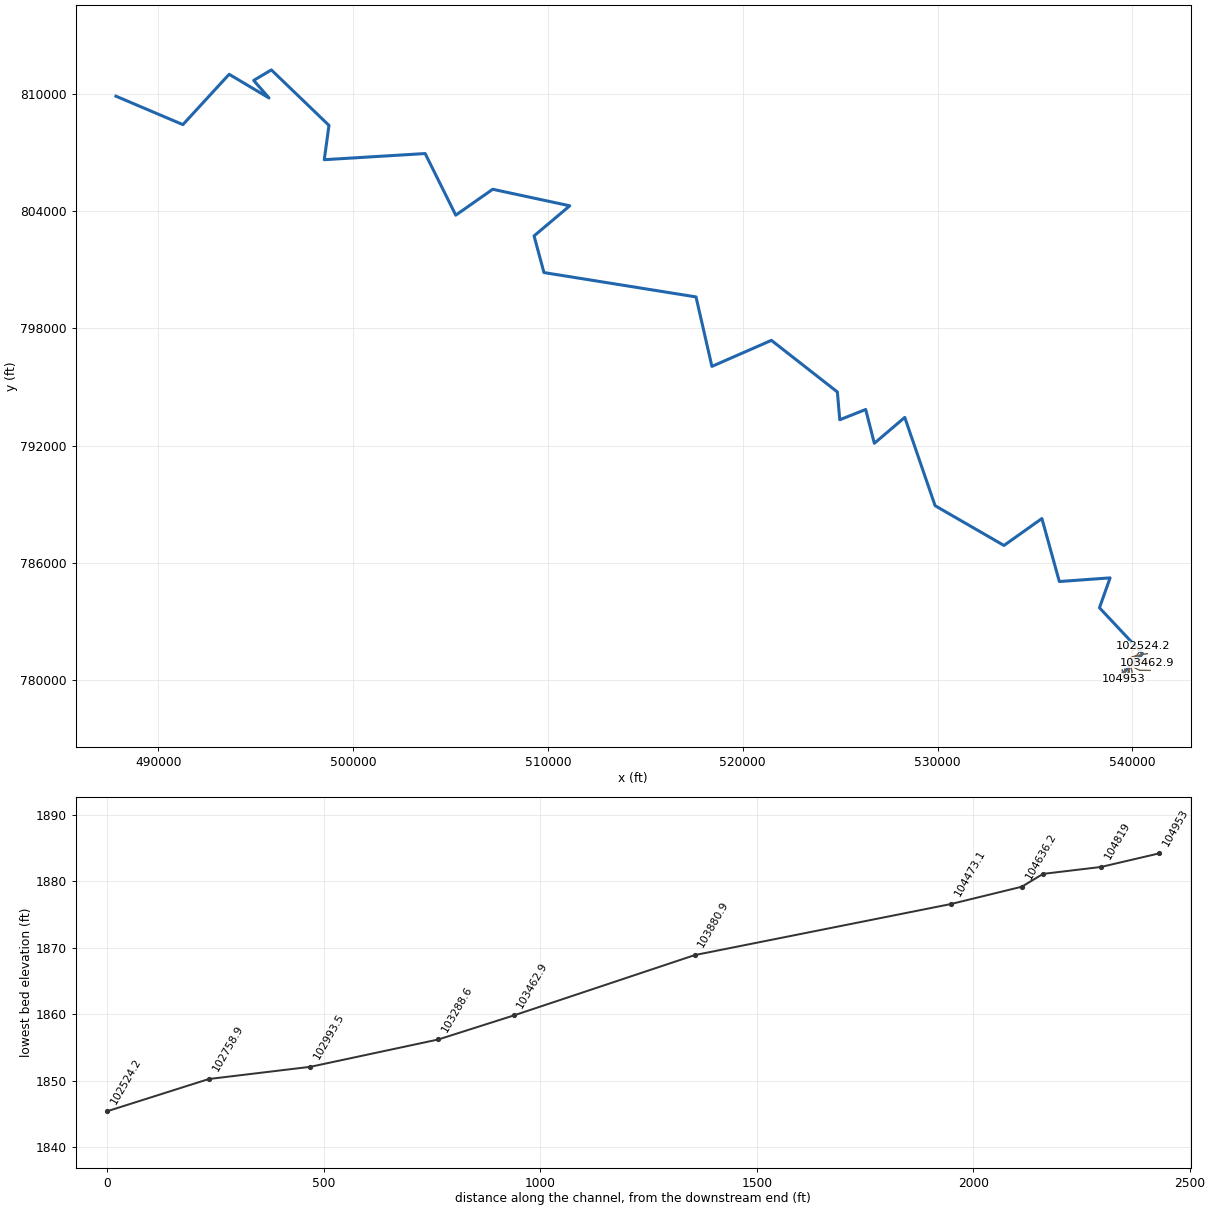
--- 5238_ras.prj (project) ---

Proj Title=5238
Current Plan=p01
Default Exp/Contr=0.3,0.1
English Units
Geom File=g01
Flow File=f01
Plan File=p01
Y Axis Title=Elevation
X Axis Title(PF)=Main Channel Distance
X Axis Title(XS)=Station
BEGIN DESCRIPTION:
RFD model 5238 exported to HEC-RAS
END DESCRIPTION:

--- 5238_ras.p01 (plan) ---

Plan Title=Plan 01
Program Version=4.10
Short Identifier=Plan 01
Geom File=g01
Flow File=f01
Subcritical Flow
Calc Critical at every XS
Secant Critical Depth

--- 5238_ras.f01 (steady flow) ---

Flow Title=Flow 01
Program Version=5.01
Number of Profiles= 6
Profile Names=10yr,25yr,50yr,100yr,100plus,500yr
River Rch & RM=5238,367,  104953
 1753.92 2755.87 3684.06 4499.11 6568.69 7999.94
River Rch & RM=5238,367,  104819
 1756.24 2759.63 3689.17 4505.45 6577.96 8009.98
River Rch & RM=5238,367,104685.1
 1764.86  2773.5 3708.02 4528.78 6612.02 8046.78
River Rch & RM=5238,367,104473.1
 1768.73 2779.75 3716.54 4539.34 6627.43 8063.49
River Rch & RM=5238,367,103880.9
  2067.9 3259.54 4367.03 5342.63 7800.24 9307.07
River Rch & RM=5238,367,103462.9
 2085.47 3287.85 4405.55 5390.35 7869.91 9380.61
River Rch & RM=5238,367,103288.6
 2088.96 3293.49 4413.23 5399.86  7883.8 9395.29
River Rch & RM=5238,367,102993.5
 2106.96 3322.52 4452.73 5448.81 7955.27 9470.65
River Rch & RM=5238,367,102758.9
 2110.18 3327.73 4459.83 5457.62 7968.12 9484.23
River Rch & RM=5238,367,102524.2
 2124.08 3350.18 4490.42 5495.54 8023.48 9542.65
River Rch & RM=5238,367,102289.5
 2131.69 3362.52 4507.24 5516.43 8053.99 9574.93
River Rch & RM=5238,367,102012.3
 2134.39 3366.89  4513.2 5523.84  8064.8 9586.37
River Rch & RM=5238,367,101585.5
  2351.1 3718.14 4992.73 6119.57 8934.5810500.42
River Rch & RM=5238,367,  101062
 2368.54 3746.43 5031.37 6167.59 9004.6910573.57
River Rch & RM=5238,367,101008.4
 2370.94 3750.31 5036.67 6174.17 9014.2910583.58
River Rch & RM=5238,367,  100755
 2373.33 3754.19 5041.96 6180.75 9023.8910593.58
River Rch & RM=5238,367,100454.4
 2375.23 3757.28 5046.18    6186 9031.5510601.58
River Rch & RM=5238,367,100021.2
 2387.06  3776.5 5072.48 6218.71 9079.3210651.52
River Rch & RM=5238,367,99776.61
 2391.79  3784.2    5083  6231.8 9098.4310671.47
River Rch & RM=5238,367,99532.01
 2393.69 3787.27  5087.2 6237.04 9106.0710679.44
River Rch & RM=5238,367,99287.41
  2404.8 3805.33 5111.89 6267.75 9150.9210726.26
River Rch & RM=5238,367,99042.82
 2408.79 3811.82 5120.79 6278.83 9167.0910743.17
River Rch & RM=5238,367,98844.68
 2409.96 3813.73  5123.4 6282.08 9171.8410748.14
River Rch & RM=5238,367,98533.21
 2412.29 3817.54 5128.62 6288.59 9181.3410758.08
River Rch & RM=5238,367,98309.02
 2436.24  3856.5 5181.94 6354.98 9278.2810859.28
River Rch & RM=5238,367,98064.42
  2436.7 3857.26 5182.98 6356.28 9280.1710861.26
River Rch & RM=5238,367,97819.83
  2500.9 3961.88 5326.31 6534.87 9540.9111133.25
River Rch & RM=5238,367,97575.23
 2502.06 3963.77  5328.9  6538.1 9545.6311138.15
River Rch & RM=5238,367,97330.63
 2505.55 3969.44 5336.67 6547.78 9559.7611152.86
River Rch & RM=5238,367,97086.03
 2509.97 3976.64 5346.52 6560.05 9577.6711171.47
River Rch & RM=5238,367,96871.73
 2528.79 4007.27 5388.47  6612.3 9653.9511250.69
River Rch & RM=5238,367,96677.13
 2530.41 4009.92 5392.09 6616.81 9660.5411257.53
River Rch & RM=5238,367,95863.04
 3804.88 6062.03 8183.1410070.9814703.6316244.83
River Rch & RM=5238,367,95154.73
 3813.33 6075.83 8202.07 10094.614738.1216278.64
River Rch & RM=5238,367,94884.65
 3816.08 6080.31 8208.2210102.2714749.3216289.62
River Rch & RM=5238,367,94640.05
 3818.82 6084.79 8214.3710109.9514760.52 16300.6
River Rch & RM=5238,367,94395.45
 3826.21 6096.86 8230.93 10130.614790.6816330.14
River Rch & RM=5238,367,93906.26
 3846.72 6130.32 8276.8410187.8414874.2416411.89
River Rch & RM=5238,367,93417.06
 3855.12 6144.05  8295.710211.37 14908.616445.56
River Rch & RM=5238,367,93172.46
 3861.39 6154.31 8309.7910228.97 14934.3 16470.8
River Rch & RM=5238,367,92927.86
 4108.33 6554.16 8855.7110906.7115923.7917422.91
River Rch & RM=5238,367,92683.26
 4114.46 6564.21 8869.5510924.0215949.0717447.58
River Rch & RM=5238,367,92438.67
 4119.97 6573.26 8882.01 10939.615971.8217469.77
River Rch & RM=5238,367,92148.72
  4218.1 6733.53 9102.03 11214.116372.5917857.55
River Rch & RM=5238,367,91704.87
 4226.82 6747.85 9121.7511238.77 16408.617892.56
River Rch & RM=5238,367,91460.27
 4234.12 6759.83 9138.2511259.4116438.7417921.86
River Rch & RM=5238,367,91215.68
  4333.2 6922.36    936211539.24 16847.318317.92
River Rch & RM=5238,367,90971.08
 4354.55 6957.41 9410.2911599.66 16935.518403.33
River Rch & RM=5238,367,90751.33
 4357.96 6963.01    941811609.32 16949.618417.01
River Rch & RM=5238,367,90683.73
 4367.38  6978.5 9439.3511636.0416988.6318454.82
River Rch & RM=5238,367,90472.02
 4376.74 6993.91 9460.6111662.6917027.52 18492.6
River Rch & RM=5238,367,90222.48
  4379.7  6998.8 9467.3711671.16 17039.918504.65
River Rch & RM=5238,367,89972.95
 4410.42 7049.42 9537.2711758.8117167.86   18629
River Rch & RM=5238,367,89723.42
 4413.78 7054.96 9544.92 11768.417181.8718642.62
River Rch & RM=5238,367,89473.89
  4420.9 7066.69 9561.1211788.7217211.5418671.44
River Rch & RM=5238,367,89224.36
 4424.84  7073.2 9570.11   1180017228.0118687.45
River Rch & RM=5238,367,88978.28
 4475.29 7155.86 9683.8311942.13 17435.518887.08
River Rch & RM=5238,367,88920.88
 4476.48 7157.82 9686.5311945.5117440.4518891.86
River Rch & RM=5238,367,88725.29
 4478.66 7161.41 9691.4911951.7217449.5118900.63
River Rch & RM=5238,367,88508.96
 4483.42 7169.24 9702.2911965.2617469.2818919.74
River Rch & RM=5238,367,88231.98
 4557.04  7289.4  9867.212170.9117769.5419206.36
River Rch & RM=5238,367,87985.33
 4559.22 7292.98 9872.13 12177.117778.5619215.07
River Rch & RM=5238,367,87738.67
 4563.96 7300.78  9882.912190.5817798.2519234.06
River Rch & RM=5238,367,87516.21
  4728.9 7569.5810251.4612649.8118468.7219870.02
River Rch & RM=5238,367,87245.36
 4767.52 7633.7610340.5512762.0318632.5620029.12
River Rch & RM=5238,367,86952.94
 4775.41  7646.9 10358.812785.0418666.1620061.82
River Rch & RM=5238,367,86739.22
 4778.04 7651.2710364.8812792.7118677.3520072.71
River Rch & RM=5238,367,86489.07
 4781.04 7656.2710371.8312801.4718690.1520085.16
River Rch & RM=5238,367,86258.74
 4786.31 7665.0410384.0112816.8218712.5620106.93
River Rch & RM=5238,367,86012.09
 4812.54 7708.5510444.3312892.7318823.3820214.12
River Rch & RM=5238,367,85765.43
 4816.67 7715.4310453.8812904.7718840.9620231.18
River Rch & RM=5238,367,85518.78
 4820.83 7722.3210463.4612916.8318858.5720248.25
River Rch & RM=5238,367,85272.12
 4873.07 7808.5910582.7113066.51 19077.120457.95
River Rch & RM=5238,367,85025.47
    4912 7873.09 10672.113178.9319241.2420616.02
River Rch & RM=5238,367,84778.81
 4920.98 7888.0410692.8513205.0919279.4320652.96
River Rch & RM=5238,367,84532.16
 4925.47  7895.510703.2213218.1619298.5120671.42
River Rch & RM=5238,367, 84285.5
 4931.25 7905.12 10716.613235.0219323.1320695.26
River Rch & RM=5238,367,84038.85
 4939.25 7918.4510735.1213258.3919357.25 20728.3
River Rch & RM=5238,367,83792.19
  4942.4  7923.710742.4313267.6219370.7220741.36
River Rch & RM=5238,367,83545.54
 4944.63 7927.4110747.5913274.1319380.2320750.58
River Rch & RM=5238,367, 83234.6
 4963.49  7958.810791.1913329.0719460.4520828.08
River Rch & RM=5238,367,82781.97
 4978.73 7984.1810826.4713373.5819525.4220890.93
River Rch & RM=5238,367,82558.92
 4980.77 7987.58 10831.213379.5419534.1320899.35
River Rch & RM=5238,367,82312.26
 4986.68 7997.4510844.9213396.8619559.4220923.85
River Rch & RM=5238,367, 82065.6
 4998.29 8016.8210871.8913430.9119609.1320972.05
River Rch & RM=5238,367,81818.95
 4999.57 8018.9610874.8813434.6919614.65 20977.4
River Rch & RM=5238,367,81572.29
 5181.84 8321.65 11294.9 13963.620386.8521718.62
River Rch & RM=5238,367,81325.64
 5186.77 8329.8811306.3513978.0620407.9721738.98
River Rch & RM=5238,367,81078.98
 5227.68 8398.1511401.3814098.0520583.1521907.63
River Rch & RM=5238,367,80832.33
 5234.42  8409.411417.0414117.8320612.0321935.44
River Rch & RM=5238,367,80585.67
 5241.13 8420.6211432.6814137.5820640.8821963.23
River Rch & RM=5238,367,80339.02
 5245.11 8427.2811441.9614149.32   2065821979.75
River Rch & RM=5238,367,80092.36
 9494.8715220.7520645.8425484.5537207.4536257.56
River Rch & RM=5238,367,79982.76
  9496.315223.15 20649.225488.8137213.6636263.11
River Rch & RM=5238,367, 79732.8
 9501.0415231.1420660.3825502.9937234.3736281.61
River Rch & RM=5238,367,79482.83
 9514.7915254.29 20692.8 25544.137294.3936335.24
River Rch & RM=5238,367,79232.86
 9526.1715273.4520719.6325578.1237344.06 36379.6
River Rch & RM=5238,367, 78982.9
 9529.1715278.5120726.71 25587.137357.16 36391.3
River Rch & RM=5238,367,78732.93
 9530.59 15280.920730.0625591.3537363.3736396.85
River Rch & RM=5238,367,78482.96
 9555.7515323.1620789.1525666.1837472.62 36494.1
River Rch & RM=5238,367,   78233
 9564.63 15338.120810.0525692.6537511.2736528.55
River Rch & RM=5238,367,77983.03
 9720.8315599.9221175.6326155.0738186.4137126.86
River Rch & RM=5238,367,77733.07
 9723.8215604.9621182.6826164.0138199.4537138.47
River Rch & RM=5238,367, 77483.1
 9727.2815610.7921190.8426174.3538214.5537151.91
River Rch & RM=5238,367,77233.13
  9730.915616.8721199.3726185.1638230.3437165.96
River Rch & RM=5238,367,76983.17
 9733.2515620.8421204.92 26192.238240.6237175.12
River Rch & RM=5238,367, 76733.2
    977815696.2121310.4626326.0538436.0337349.03
River Rch & RM=5238,367,76483.24
 9780.3515700.16   2131626333.08 38446.337358.18
River Rch & RM=5238,367,76233.27
 9785.9915709.6721329.3226349.9738470.9637380.12
River Rch & RM=5238,367, 75983.3
  9809.915749.9821385.8126421.64 38575.637473.32
River Rch & RM=5238,367,75733.34
 9812.2415753.9221391.3426428.6638585.8537482.45
River Rch & RM=5238,367,75483.37
 9815.6715759.7121399.4526438.9638600.8837495.84
River Rch & RM=5238,367, 75233.4
 9842.22 15804.421462.0126518.2638716.6637598.66
River Rch & RM=5238,367,74983.44
 9844.0915807.5621466.4326523.8838724.8637605.96
River Rch & RM=5238,367,74733.47
 9853.9715824.1921489.72 26553.438767.9737644.25
River Rch & RM=5238,367,74483.51
 9856.3115828.1321495.2426560.41 38778.237653.37
River Rch & RM=5238,367,74233.54
 9859.7515833.9221503.3626570.7138793.2437666.74
River Rch & RM=5238,367,73983.57
10016.9316097.2121870.85 27035.439471.6838264.61
River Rch & RM=5238,367,73733.61
10023.6416108.5121886.6827055.4739500.9838290.57
River Rch & RM=5238,367,73483.64
10041.94 16139.321929.78 27110.139580.7538361.18
River Rch & RM=5238,367,73233.67
10047.3816148.4721942.63 27126.439604.5538382.29
River Rch & RM=5238,367,72983.71
10051.5716155.5321952.5327138.97 39622.938398.57
River Rch & RM=5238,367,72733.74
10056.2216163.3821963.5327152.9339643.2838416.66
River Rch & RM=5238,367,72483.78
10058.3916167.0421968.6627159.4539652.7938425.11
River Rch & RM=5238,367,72221.61
10063.5116175.6721980.76 27174.839675.21   38445
River Rch & RM=5238,367,71941.08
10065.6816179.3321985.8927181.3139684.7238453.44
River Rch & RM=5238,367,71503.12
 10073.916193.1922005.3227205.9739720.7238485.38
River Rch & RM=5238,367,71233.95
10075.2916195.5422008.6127210.1639726.83 38490.8
River Rch & RM=5238,367,70983.98
 10216.616432.9522340.6127630.6540340.7539032.14
River Rch & RM=5238,367,70734.01
10224.7816446.7522359.9627655.2140376.6139063.89
River Rch & RM=5238,367,70484.05
 10227.116450.6522365.4327662.1640386.7539072.88
River Rch & RM=5238,367,70234.08
10231.2616457.6822375.2927674.6740405.0239089.05
River Rch & RM=5238,367,69984.11
10236.5216466.5422387.7127690.4340428.0339109.41
River Rch & RM=5238,367,69734.15
10262.2316509.7822448.2227767.1340540.0239208.14
River Rch & RM=5238,367,69484.18
10269.0216521.2522464.2927787.5240569.7839234.46
River Rch & RM=5238,367,69234.22
10311.1616591.8422562.8427912.1640751.7539393.99
River Rch & RM=5238,367,68947.08
10313.7816596.2522569.0327920.0240763.2239404.14
River Rch & RM=5238,367,67984.38
10430.8516793.4322845.2128270.3141274.6639855.02
River Rch & RM=5238,367,66984.52
10477.1816871.6122954.8428409.4841477.8540034.34
River Rch & RM=5238,367,66734.55
10483.6116882.4622970.0728428.8241506.0840059.26
River Rch & RM=5238,367,65984.66
10552.9916998.9923133.0328635.2241807.4340323.44
River Rch & RM=5238,367, 65438.9
10583.3217049.8523204.0728725.1241938.6740438.14
River Rch & RM=5238,367,64984.79
 10718.117270.79 23508.4 29105.442493.8940908.03
River Rch & RM=5238,367,64734.82
10723.4617279.8223521.0629121.4742517.3540928.61
River Rch & RM=5238,367,64484.86
 10727.317286.2823530.1129132.9542534.1140943.32
River Rch & RM=5238,367,64234.89
 10732.217294.5423541.6829147.6342555.5540962.14
River Rch & RM=5238,367,63887.51
10736.6317302.0123552.1629160.9342574.9640979.18
River Rch & RM=5238,367,63796.72
10739.42 17306.723558.7129169.2342587.0740989.76
River Rch & RM=5238,367,63724.57
10741.4617310.1123563.4729175.2442595.8640997.41
River Rch & RM=5238,367,63474.61
10755.92 17334.3 23597.229217.8742658.0941051.46
River Rch & RM=5238,367,63224.64
10761.1517343.0923609.5129233.4842680.8841071.43
River Rch & RM=5238,367,62974.68
10763.7317347.4523615.6329241.2542692.2241081.41
River Rch & RM=5238,367,62724.71
10871.5417524.28 23859.329545.8443136.9341457.18
River Rch & RM=5238,367,62426.28
11004.2717748.83 24174.729946.8443722.3941972.04
River Rch & RM=5238,367,62171.09
11009.2917757.2824186.5529961.8943744.3641991.26
River Rch & RM=5238,367,61916.01
11011.5717761.1324191.9529968.7343754.3441999.99
River Rch & RM=5238,367,61671.59
11013.0917763.6924195.5429973.29   4376142005.81
River Rch & RM=5238,367,61413.09
11022.4717779.6124217.9330001.7943802.6142042.48
River Rch & RM=5238,367,61161.11
11052.1417829.1524286.9730088.97 43929.942152.41
River Rch & RM=5238,367,60911.14
11056.0617835.7824296.2730100.7943947.1542167.53
River Rch & RM=5238,367,60661.18
11065.2317851.2824318.0430128.4643987.5642202.98
River Rch & RM=5238,367,60411.21
11068.3617856.5924325.5130137.9644001.4342215.19
River Rch & RM=5238,367,60161.25
11077.9417872.81 24348.330166.9544043.7542252.36
River Rch & RM=5238,367,59911.28
11082.8617881.1424360.0230181.8744065.5342271.53
River Rch & RM=5238,367,59661.31
11090.2217893.6624377.6730204.3744098.3942300.56
River Rch & RM=5238,367,59411.35
11095.0817901.9224389.3130219.2244120.0642319.71
River Rch & RM=5238,367,59135.12
11100.4817911.1324402.3130235.82 44144.342341.19
River Rch & RM=5238,367,58661.45
11104.9817918.8324413.1830249.7144164.5842359.18
River Rch & RM=5238,367,58411.48
11108.9117925.5324422.64 30261.844182.2242374.84
River Rch & RM=5238,367,58161.52
11170.4618030.1924570.11 30449.844456.7142617.08
River Rch & RM=5238,367,57842.05
11173.0818034.6624576.4330457.8744468.4842627.49
River Rch & RM=5238,367,57383.65
11193.5418069.52 24625.630520.62 44560.1 42708.5
River Rch & RM=5238,367,57084.97
11206.0918090.9724655.9430559.4244616.75 42758.8
River Rch & RM=5238,367,56866.78
11207.9618094.1824660.4730565.2144625.2142766.32
River Rch & RM=5238,367,56592.66
15808.9725666.8335121.3443667.0263753.8458480.03
River Rch & RM=5238,367,56329.04
15810.9925670.2735126.2143673.2563762.9458487.69
River Rch & RM=5238,367,56087.04
15815.4225677.8635136.9343686.9563782.9558504.56
River Rch & RM=5238,367,55866.92
15816.6425679.9335139.86 43690.763788.4258509.16
River Rch & RM=5238,367,55616.95
15819.3225684.5235146.3543698.9963800.5258519.38
River Rch & RM=5238,367,55366.99
15933.71 25874.835411.0544032.5164287.4658915.45
River Rch & RM=5238,367,55117.02
 15936.325879.2135417.2544040.4464299.0458925.13
River Rch & RM=5238,367,54867.05
15940.8725887.0135428.2944054.5364319.6258942.46
River Rch & RM=5238,367,54617.09
15943.6925891.83 35435.144063.2564332.3458953.16
River Rch & RM=5238,367,54356.07
15959.7225919.0635473.4644112.12 64403.759012.78
River Rch & RM=5238,367,54119.29
15961.8625922.7135478.6444118.7364413.3659020.93
River Rch & RM=5238,367,53841.07
15975.7425946.4735512.2644161.7564476.1659073.89
River Rch & RM=5238,367, 53350.4
15986.3525964.4635537.5744193.9864523.2159113.09
River Rch & RM=5238,367,53119.42
15989.4325969.6535544.8644203.2464536.7359124.29
River Rch & RM=5238,367,52850.45
15990.6925971.7835547.8544207.0364542.2759128.88
River Rch & RM=5238,367,52619.49
16088.0426133.0535771.59 44488.364952.9159460.38
River Rch & RM=5238,367,52369.52
16091.19 26138.435779.1344497.8864966.9159472.05
River Rch & RM=5238,367,52166.15
 16092.426140.4635782.0444501.6264972.3659476.63
River Rch & RM=5238,367,51869.59
16192.8826303.9936006.3744780.7265379.8659796.73
River Rch & RM=5238,367,51555.79
16208.91 26331.436045.1344830.2865452.2159857.53
River Rch & RM=5238,367,51138.31
16215.6826342.93 36061.444851.0365482.5159882.86
River Rch & RM=5238,367,50932.17
16219.19 26348.936069.84 44861.865498.2459896.02
River Rch & RM=5238,367,50558.62
   1639926638.2736463.8545348.6766209.06 60443.5
River Rch & RM=5238,367, 50369.8
16414.8626665.5836502.6645398.4866281.7860505.05
River Rch & RM=5238,367,50119.83
16417.5726670.2536509.3145407.0266294.2660515.64
River Rch & RM=5238,367,49869.86
16422.2126678.2736520.7145421.6866315.66 60533.8
River Rch & RM=5238,367, 49619.9
 16432.426695.8636545.7345453.8366362.5960573.64
River Rch & RM=5238,367,49315.67
16435.2426700.7536552.7145462.7966375.6760584.73
River Rch & RM=5238,367,49046.51
 16553.526903.5336840.0645830.8166912.98 61036.8
River Rch & RM=5238,367,   48870
16554.2726904.8536841.9545833.2366916.5261039.82
River Rch & RM=5238,367,48800.03
16579.0926947.6436902.7645911.3467030.56 61136.3
River Rch & RM=5238,367,48552.25
16582.3926953.3736910.9345921.8667045.9161149.36
River Rch & RM=5238,367,48304.46
16584.0426956.2336915.0145927.1167053.5861155.89
River Rch & RM=5238,367,48012.99
 16587.626962.3836923.7945938.4267070.0961169.96
River Rch & RM=5238,367, 47561.1
16594.8426974.9436941.6945961.4667103.7361198.59
River Rch & RM=5238,367,47313.31
16614.8127009.3236990.5446024.1467195.25 61275.9
River Rch & RM=5238,367,47065.52
16616.7427012.6436995.2746030.2367204.1461283.43
River Rch & RM=5238,367,46817.73
16763.2227258.1837338.4546464.4867838.1461800.53
River Rch & RM=5238,367,46569.94
 16764.927261.0737342.5646469.7667845.8561807.03
River Rch & RM=5238,367,46322.16
 16770.827271.2637357.0646488.3867873.0361830.04
River Rch & RM=5238,367,46074.37
16773.38 27275.737363.3746496.4967884.8861840.04
River Rch & RM=5238,367,45826.58
16776.7327281.4737371.5746507.0467900.2761853.04
River Rch & RM=5238,367,45578.79
16778.5227284.5737375.99 46512.767908.5461860.05
River Rch & RM=5238,367,45083.22
17076.4127793.6238095.9847433.2669252.5562981.68
River Rch & RM=5238,367,44688.64
17085.6327809.5238118.5947462.3169294.9863017.42
River Rch & RM=5238,367,44111.93
 17107.827847.6838172.7947531.8769396.5363102.79
River Rch & RM=5238,367,43844.28
17119.3427867.5738201.0747568.1969449.5663147.44
River Rch & RM=5238,367,43596.49
17130.7827887.2838229.0747604.1469502.0563191.57
River Rch & RM=5238,367, 43348.7
17133.8627892.5938236.6247613.83 69516.263203.48
River Rch & RM=5238,367,43100.91
17139.0227901.4638249.23   47630 69539.863223.31
River Rch & RM=5238,367,42853.13
17140.5727904.1338253.0147634.86 69546.963229.26
River Rch & RM=5238,367,42605.34
17259.82 28108.6 38542.848006.0470088.8163682.25
River Rch & RM=5238,367,42357.55
17263.43 28114.838551.6148017.3470105.32 63696.1
River Rch & RM=5238,367,42109.76
17268.0828122.7938562.9548031.8870126.5563713.89
River Rch & RM=5238,367,41861.97
17271.0728127.9338570.2348041.2170140.1663725.26
River Rch & RM=5238,367,41614.19
 17306.628188.7138656.27 48151.3 70300.963859.14
River Rch & RM=5238,367, 41366.4
17311.0528196.3338667.05 48165.170321.0563875.93
River Rch & RM=5238,367,41118.61
17313.02 28199.738671.8248171.1970329.9463883.34
River Rch & RM=5238,367,40870.82
17316.6828205.9638680.6848182.5570346.5263897.16
River Rch & RM=5238,367,40623.04
17321.2428213.7838691.7748196.7370367.2363914.44
River Rch & RM=5238,367,40375.25
17325.6828221.3838702.5348210.5170387.3563931.23
River Rch & RM=5238,367,40127.46
17330.6328229.8738714.5648225.9170409.8463949.98
River Rch & RM=5238,367,39879.67
17333.1328234.14 38720.648233.6470421.1163959.36
River Rch & RM=5238,367,39631.88
17341.3728248.1738740.4148258.9370458.0563989.96
River Rch & RM=5238,367,38888.52
17366.69 28290.438799.2748333.2170566.4964077.28
River Rch & RM=5238,367,38145.16
17442.9828413.91 38968.148542.5770872.1564312.36
River Rch & RM=5238,367,37897.37
17447.7828422.0138979.4748557.0170893.2364329.59
River Rch & RM=5238,367,37649.58
 17450.8 28427.138986.6248566.0970906.4864340.42
River Rch & RM=5238,367,37401.79
 17453.828432.1738993.7548575.1470919.7164351.25
River Rch & RM=5238,367,37154.01
17458.6128440.3539005.2848589.8670941.1964368.98
River Rch & RM=5238,367,36906.22
17460.1128442.8939008.8548594.3970947.8164374.39
River Rch & RM=5238,367,36658.43
17466.2528453.2739023.4348612.9270974.8764396.55
River Rch & RM=5238,367,36410.64
17471.4328462.0239035.7348628.56 70997.764415.24
River Rch & RM=5238,367,36162.85
17499.3428508.3439100.0948709.5771115.9864509.71
River Rch & RM=5238,367,35667.28
17512.5928530.3339130.6348747.9871172.0664554.47
River Rch & RM=5238,367,35366.75
17517.12 28537.9 39141.248761.3571191.5764570.21
River Rch & RM=5238,367, 35171.7
17518.8928540.9139145.41 48766.771199.38 64576.6
River Rch & RM=5238,367,34923.92
17522.8328547.5739154.7948778.6171216.7764590.86
River Rch & RM=5238,367,34676.13
17526.6628554.0439163.8648790.1671233.6364604.62
River Rch & RM=5238,367,34428.34
 17535.828569.4739185.5548817.7371273.8864637.56
River Rch & RM=5238,367,34180.55
17653.1928759.4639445.25 49139.771743.9664998.41
River Rch & RM=5238,367,33932.76
17655.8428763.9239451.4749147.5971755.4865007.73
River Rch & RM=5238,367,33462.12
17667.5228783.2739478.3449181.3671804.7965046.96
River Rch & RM=5238,367,33079.89
17674.4528794.86 39494.549201.7971834.6265070.98
River Rch & RM=5238,367,32693.82
17687.3328816.5839524.99 49240.571891.1465117.05
River Rch & RM=5238,367, 32627.2
17688.1628817.9839526.9549242.9871894.7565119.99
River Rch & RM=5238,367,32381.41
 17692.328824.9439536.7149255.3771912.8465134.69
River Rch & RM=5238,367,32135.62
17767.2728952.8939717.5449486.4372250.1965413.77
River Rch & RM=5238,367,31889.84
17769.8728957.28 39723.749494.2572261.6165423.07
River Rch & RM=5238,367,31644.05
17774.81 28965.639735.3849509.0772283.2465440.68
River Rch & RM=5238,367,31072.05
17794.2328998.56 39781.849568.22 72369.665511.59
River Rch & RM=5238,367,30663.74
17803.0729013.5639802.9449595.14 72408.965543.85
River Rch & RM=5238,367,30417.95
17865.5529119.9539953.0949786.7772688.6965774.41
River Rch & RM=5238,367,30172.17
 17873.929134.0939972.99 49812.172725.6665804.67
River Rch & RM=5238,367,29926.38
17875.39 29136.639976.5349816.5972732.2365810.05
River Rch & RM=5238,367, 29680.6
17879.6329143.7539986.5649829.3372750.8265825.17
River Rch & RM=5238,367,29458.73
17882.9229149.2939994.33 49839.272765.2365836.88
River Rch & RM=5238,367,29189.03
 17890.729162.3640012.6149862.3572799.0465864.21
River Rch & RM=5238,367,28943.24
17896.3329171.7740025.7549878.9672823.2865883.72
River Rch & RM=5238,367,28697.46
17900.3829178.5740035.2549890.9872840.8465897.87
River Rch & RM=5238,367,28451.67
17906.2429188.3940048.9949908.3672866.2165918.35
River Rch & RM=5238,367,28205.88
18082.7829471.9840434.6950384.3473561.14 66443.3
River Rch & RM=5238,367,28026.54
18084.7329475.2540439.2750390.1373569.5966450.11
River Rch & RM=5238,367,27714.31
18090.9829485.6640453.7850408.4573596.34 66471.5
River Rch & RM=5238,367,27468.53
18118.8529532.6440519.6950492.1173718.4866570.64
River Rch & RM=5238,367,27222.74
18123.0829539.65 40529.450504.32 73736.366584.73
River Rch & RM=5238,367,26929.27
 18125.729543.9940535.4250511.8873747.3466593.48
River Rch & RM=5238,367,26564.02
19052.5230997.9942481.53   5287777200.4269082.92
River Rch & RM=5238,367,26267.28
19054.8331001.8142486.8452883.6677210.1569090.58
River Rch & RM=5238,367,25993.81
19057.4231006.12 42492.852891.1777221.11 69099.2
River Rch & RM=5238,367,25748.03
19058.5831008.0342495.4652894.5177225.9869103.03
River Rch & RM=5238,367,25502.24
 19068.531024.6842518.7452923.9877269.0169137.49
River Rch & RM=5238,367,25256.46
19110.4231095.7842618.8553051.4677455.13 69288.7
River Rch & RM=5238,367,25010.67
 19115.331103.87 42630.1 53065.677475.7869304.96
River Rch & RM=5238,367,24764.89
19124.4931119.2442651.5553092.7177515.3769336.52
River Rch & RM=5238,367, 24519.1
19128.0631125.2342659.9453103.3377530.8669348.95
River Rch & RM=5238,367,24273.32
19133.7531134.8342673.3953120.41 77555.869369.02
River Rch & RM=5238,367,24027.53
19153.9631169.0842721.5953181.7677645.3769441.67
River Rch & RM=5238,367,23781.75
19164.4531186.7842746.4753213.3677691.5269478.94
River Rch & RM=5238,367,23535.96
19167.7731192.3642754.2553223.2177705.8869490.41
River Rch & RM=5238,367,23290.17
19171.3231198.2542762.4653233.5577720.9869502.34
River Rch & RM=5238,367,23044.39
19190.6131230.1442806.6653289.0577802.0269565.87
River Rch & RM=5238,367, 22798.6
19196.5931240.0842820.4853306.4577827.4169585.92
River Rch & RM=5238,367,22552.82
19198.4331243.1542824.7453311.8277835.2669592.13
River Rch & RM=5238,367,22307.03
19201.1131247.6142830.9653319.65 77846.7 69601.2
River Rch & RM=5238,367,22061.25
19288.4731389.1343024.5253559.7778197.2669867.41
River Rch & RM=5238,367,21815.46
19294.0731398.4843037.5653576.2178221.2769886.47
River Rch & RM=5238,367,21569.68
19298.6631406.1543048.2753589.7578241.04 69902.2
River Rch & RM=5238,367,21323.89
19302.5531412.6543057.3553601.23 78257.869915.55
River Rch & RM=5238,367, 21078.1
19371.6431529.9643222.6253811.7978565.2170165.09
River Rch & RM=5238,367,20832.32
19373.0231532.2743225.8553815.8878571.1870169.85
River Rch & RM=5238,367,19875.81
19382.8631548.7943248.9953845.1978613.9870204.12
River Rch & RM=5238,367,19019.43
19398.4431574.8343285.32 53891.178681.01 70257.4
River Rch & RM=5238,367,18772.51
19401.4931579.9543292.4653900.1178694.1670267.86
River Rch & RM=5238,367, 18525.6
19405.54 31586.743301.8853912.0178711.5370281.66
River Rch & RM=5238,367,18278.68
19416.6931605.1343327.4353944.0878758.3670318.27
River Rch & RM=5238,367,18031.76
19418.1531607.5443330.7653948.2678764.4670323.03
River Rch & RM=5238,367,17784.85
19427.8431623.4943352.8253975.8878804.7970354.41
River Rch & RM=5238,367,17537.93
 19430.931628.5543359.8153984.66 78817.670364.39
River Rch & RM=5238,367,17291.02
 19473.131697.4243454.4754102.6178989.81 70496.5
River Rch & RM=5238,367, 17044.1
19476.0231702.2343461.1354110.9679002.01   70506
River Rch & RM=5238,367,16797.19
19707.2132067.5143952.4554710.8779877.8871141.38
River Rch & RM=5238,367,16550.27
19710.4832072.8743959.8454720.1179891.36 71151.8
River Rch & RM=5238,367,16303.36
19727.6832101.0943998.7854768.7979962.43 71206.7
River Rch & RM=5238,367,16056.44
19733.2232110.1744011.2854784.38 79985.2 71224.2
River Rch & RM=5238,367,15809.53
19738.4632118.7344023.0854799.1280006.7271240.76
River Rch & RM=5238,367,15562.61
19741.1432123.1444029.14 54806.780017.7871249.27
River Rch & RM=5238,367, 15315.7
19766.4832164.6744086.3854878.1780122.1371329.68
River Rch & RM=5238,367,15068.78
19769.6332169.8144093.4654887.0280135.0571339.61
River Rch & RM=5238,367,14821.87
19771.57   3217344097.85 54892.580143.0571345.76
River Rch & RM=5238,367,14574.95
19774.4232177.6544104.27 54900.580154.7371354.73
River Rch & RM=5238,367,14328.04
 19908.332388.48 44387.255245.2180658.0171716.99
River Rch & RM=5238,367,13834.21
20068.9732640.5344724.5755655.2381256.6472144.45
River Rch & RM=5238,367,13340.38
20095.0432682.5144781.7855725.9381359.8672221.64
River Rch & RM=5238,367,12599.63
20104.0932697.2144801.9455750.9881396.44 72249.4
River Rch & RM=5238,367,11858.88
20111.3932709.1844818.4155771.5681426.4872272.45
River Rch & RM=5238,367,11611.97
20114.8232714.7944826.1555781.2181440.5772283.27
River Rch & RM=5238,367,11365.05
 20118.432720.6444834.2255791.2981455.2872294.56
River Rch & RM=5238,367,11118.14
20121.2332725.28 44840.655799.2581466.9172303.49
River Rch & RM=5238,367,10871.22
20127.7832736.0144855.3855817.7181493.8672324.19
River Rch & RM=5238,367,10624.31
20141.9232759.18 44887.355857.5781552.0572368.86
River Rch & RM=5238,367,10377.39
20155.7632781.8544918.5255896.5681608.9872412.58
River Rch & RM=5238,367,10130.48
   2015832785.5144923.5755902.8681618.1872419.63
River Rch & RM=5238,367,9883.563
20167.52 32801.144945.0555929.6981657.3472449.71
River Rch & RM=5238,367,9666.018
20173.7632811.3344959.1555947.2981683.0572469.45
River Rch & RM=5238,367,9389.732
 20174.832813.04 44961.555950.2381687.3472472.73
River Rch & RM=5238,367,9142.817
20185.3932830.3844985.3855980.0281730.84 72506.1
River Rch & RM=5238,367,8895.902
20189.1332836.4844993.7955990.5281746.1672517.84
River Rch & RM=5238,367,8648.987
20192.1232841.3845000.5355998.9381758.4472527.24
River Rch & RM=5238,367,8402.072
20196.0832847.8245009.3756009.9281774.4872539.45
River Rch & RM=5238,367,8155.156
20341.6633079.8445323.3256395.41 82337.372952.35
River Rch & RM=5238,367,7853.314
20351.8433096.4145346.0656423.7282378.6472983.75
River Rch & RM=5238,367,7661.326
20353.7833099.5845350.4356429.1782386.5972989.84
River Rch & RM=5238,367,7414.411
20355.5633102.5145354.45 56434.282393.9372995.47
River Rch & RM=5238,367,7113.619
20387.5433154.7345426.2756523.7282524.6473095.25
River Rch & RM=5238,367,6673.665
20393.1733163.96   4543956539.6382547.8573113.05
River Rch & RM=5238,367, 6426.75
20399.8233174.8645454.03 56558.482575.2773134.12
River Rch & RM=5238,367,6179.834
20406.7333186.22 45469.7   5657882603.8873156.12
River Rch & RM=5238,367,5932.919
   20422 33211.345504.3256621.3182667.11 73204.8
River Rch & RM=5238,367,5651.446
20423.3133213.4645507.3156625.0582672.5873209.02
River Rch & RM=5238,367,5439.089
20461.3533275.8245593.2556732.4182829.3373329.26
River Rch & RM=5238,367,5192.174
20465.8733283.2545603.5456745.2982848.1373343.76
River Rch & RM=5238,367,4945.258
20467.7633286.3645607.8456750.6782855.9873349.84
River Rch & RM=5238,367,4641.086
20471.6533292.7945616.7356761.8382872.2773362.47
River Rch & RM=5238,367,4204.513
30809.8150389.9569323.4186526.18126328.2106044.1
River Rch & RM=5238,367,3712.291
30815.35 50399.169336.1286542.13126351.5106061.1
River Rch & RM=5238,367, 3272.15
30822.7250411.2969353.0286563.36126382.5106083.7
River Rch & RM=5238,367,2792.427
30849.9650456.2369415.2686641.38126496.4106166.7
River Rch & RM=5238,367,2301.401
30856.6150467.2669430.5786660.63126524.5106187.3
River Rch & RM=5238,367,1810.376
30864.4550480.2569448.6186683.32126557.6106211.5
River Rch & RM=5238,367,1319.351
30872.6750493.8969467.5586707.13126592.4  106237
Boundary for River Rch & Prof#=5238,367,1
Up Type= 0
Dn Type= 2
Boundary for River Rch & Prof#=5238,367,2
Up Type= 0
Dn Type= 2
Boundary for River Rch & Prof#=5238,367,2
Up Type= 0
Dn Type= 2
Boundary for River Rch & Prof#=5238,367,2
Up Type= 0
Dn Type= 2
Boundary for River Rch & Prof#=5238,367,2
Up Type= 0
Dn Type= 2
Boundary for River Rch & Prof#=5238,367,2
Up Type= 0
Dn Type= 2

--- 5238_ras.g01 (geometry) ---

Geom Title=5238
Program Version=4.10

River Reach=5238,367
Reach XY= 30
539499.342873096780330.096888959540522.287790835 781342.24330622
538308.256512463783697.662632003538853.361529589785227.761168957
536248.663148284785041.434920609535353.524207741788265.740466446
533407.876075566786887.346490145529872.465231389 788922.30312255
528315.694376469793441.573716298526754.756791592 792117.09459047
 526310.38537553793846.833881602524980.277501225793321.261541069
524857.534485459794743.830662742521472.222054005797385.260393858
518418.856670707796053.567379311517603.472168416 799608.87160109
509799.999664962800855.399451748509292.402924478802732.237284794
511124.305350542804272.760394633507170.833067179 805119.28825675
505273.610960245803794.982655287503702.777570069806947.760461599
498525.694377303806632.482467055498767.361045063 808389.42707625
495809.105431139811228.829109892494903.472210824 810690.81595996
495690.277430207809792.204711825493643.359058231811004.451723561
491270.169802308808428.521079212487833.616111696809884.409971714

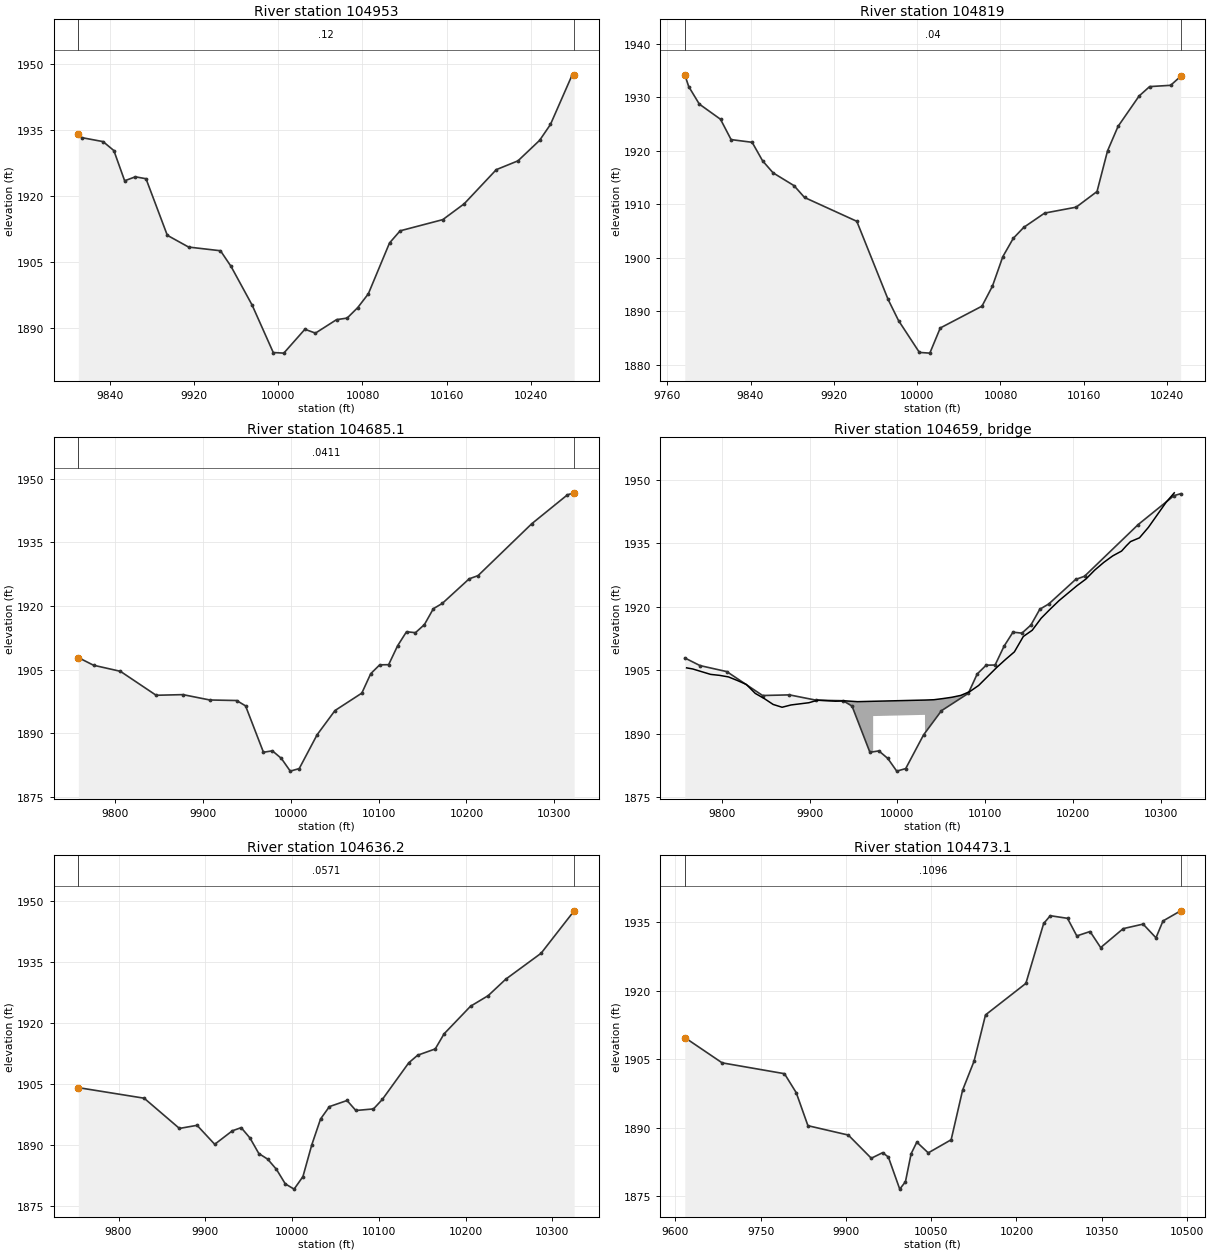
Type RM Length L Ch R = 1 ,  104953,133.940000,133.940000,133.940000
XS GIS Cut Line= 6
539471.362185331780517.940933782 539495.10815993780390.245932787
539504.474091673780275.369720768539513.832142926780202.731440971
539528.099603038780126.534938594539546.324516603780053.122155551
#Sta/Elev= 30
9809.7211934.0869812.7791933.2999833.2781932.3819843.5281930.3379853.7771923.457
9863.9681924.3629874.0961923.9259894.3511911.0379914.6061908.3539944.942 1907.51
 9954.981903.9439975.0571895.1169995.1341884.32210005.161884.18410025.221889.621
10035.251888.74410055.31 1891.8110065.391892.16810075.471894.55310085.561897.696
10105.721909.286 10115.81912.05210156.391914.60410176.741918.21210207.281925.993
10227.881927.99610248.491932.67210258.791936.292 10279.41947.54910281.34  1947.6
#Mann= 3 , 0 , 0
9809.721    0.12       09809.721    0.12       010281.34    0.12       0
#XS Ineff= 2 , 0
       0                               0
Bank Sta=9809.721,10281.34
Exp/Cntr=0.3,0.1

Type RM Length L Ch R = 1 ,  104819,133.940100,133.940100,133.940100
XS GIS Cut Line= 6
539609.522784863780558.707616207539619.255459027780506.722737333
539629.131723713780416.966701969539638.643409101780257.304327245
539645.149307661780183.169582096539659.460709769780085.587324035
#Sta/Elev= 30
9776.8421934.2059780.6141932.0059790.788 1928.739811.1351925.8939821.3091922.089
9841.5231921.5829851.584 1918.119861.6441915.8699881.7651913.4739891.8251911.264
9942.0371906.8069972.0951892.1919982.1151888.23810002.151882.27810012.171882.147
10022.181886.84910062.251890.93410072.271894.66410082.29  1900.210092.331903.626
10102.361905.66810122.441908.34210152.691909.44910172.741912.37510182.841919.982
10192.941924.56410213.141930.24210223.241932.00210243.441932.24410253.031933.913
#Mann= 3 , 0 , 0
9776.842    0.04       09776.842    0.04       010253.03    0.04       0
#XS Ineff= 2 , 0
       0                               0
Bank Sta=9776.842,10253.03
Exp/Cntr=0.3,0.1

Type RM Length L Ch R = 1 ,104685.1,48.861100,48.861100,48.861100
XS GIS Cut Line= 2
539814.384564668780582.007202297 539705.87762019780027.536716193
#Sta/Elev= 30
9757.7041907.8659775.0341906.0629805.6031904.6339846.3621898.9849876.9311899.135
  9907.51897.8739938.0691897.7489948.2591896.4849968.6381885.5559978.8281885.888
9989.0171884.1099999.2071881.105 10009.41881.70310029.781889.67510050.161895.385
10080.72 1899.4910090.911904.079 10101.11906.15310111.291906.19610121.481910.641
10131.671913.96310141.861913.73310152.051915.63810162.241919.38610172.431920.633
   10203 1926.4210213.191927.18510274.331939.40710315.091946.23910322.691946.698
#Mann= 3 , 0 , 0
9757.704  0.0411       09757.704  0.0411       010322.69  0.0411       0
#XS Ineff= 2 , 0
       0                               0
Bank Sta=9757.704,10322.69
Exp/Cntr=0.3,0.1

Type RM Length L Ch R = 3 ,  104659,,,
BEGIN DESCRIPTION:
END DESCRIPTION:
Bridge Culvert--1,0,-1,-1, 0
Deck Dist Width WeirC Skew NumUp NumDn MinLoCord MaxHiCord MaxSubmerge Is_Ogee
15.736350,17.388400,2.6,0, 47, 46, , , 0.95, 0, 0,0,,
 9759.76 9766.75 9787.11 9797.29 9807.48 9817.66 9827.84 9838.02 9848.20 9858.38
 9868.56 9878.74 9899.10 9909.28 9929.64 9940.73 9954.48 9972.33 9972.3310031.39
10031.3910041.6310051.8110061.9910072.1710082.3510092.5310112.8910123.0710133.25
10143.4310153.6110163.7910173.9710184.1510204.5110214.6910224.8710235.0610245.24
10255.4210260.8010265.6010275.7810285.9610306.3210315.44
 1905.52 1905.26 1903.98 1903.75 1903.38 1902.53 1901.60 1899.48 1898.27 1896.87
 1896.21 1896.75 1897.28 1897.89 1897.64 1897.72 1897.53 1897.62 1897.62 1897.91
 1897.91 1897.99 1898.26 1898.57 1899.01 1899.90 1901.36 1905.57 1907.49 1909.30
 1912.94 1914.42 1917.26 1919.39 1921.42 1924.94 1926.51 1928.65 1930.45 1931.99
 1933.14 1934.38 1935.38 1936.27 1938.74 1944.72 1946.91
  905.52  905.26  903.98  903.75  903.38  902.53  901.60  899.48  898.27  896.87
  896.21  896.75  897.28  897.89  897.64  897.72  897.53  897.62 1894.12 1894.41
  897.91  897.99  898.26  898.57  899.01  899.90  901.36  905.57  907.49  909.30
  912.94  914.42  917.26  919.39  921.42  924.94  926.51  928.65  930.45  931.99
  933.14  934.38  935.38  936.27  938.74  944.72  946.91
 9759.76 9766.75 9787.11 9797.29 9807.48 9817.66 9827.84 9838.02 9848.20 9858.38
 9868.56 9878.74 9899.10 9909.28 9929.64 9940.73 9954.48 9970.93 9970.9310029.98
10029.9810041.6310061.9910072.1710082.3510092.5310112.8910123.0710133.2510143.43
10153.6110163.7910173.9710184.1510204.5110214.6910224.8710235.0610245.2410255.42
10260.8010265.6010275.7810285.9610306.3210315.44
 1905.52 1905.26 1903.98 1903.75 1903.38 1902.53 1901.60 1899.48 1898.27 1896.87
 1896.21 1896.75 1897.28 1897.89 1897.64 1897.72 1897.53 1897.61 1897.61 1897.90
 1897.90 1897.99 1898.57 1899.01 1899.90 1901.36 1905.57 1907.49 1909.30 1912.94
 1914.42 1917.26 1919.39 1921.42 1924.94 1926.51 1928.65 1930.45 1931.99 1933.14
 1934.38 1935.38 1936.27 1938.74 1944.72 1946.91
  905.52  905.26  903.98  903.75  903.38  902.53  901.60  899.48  898.27  896.87
  896.21  896.75  897.28  897.89  897.64  897.72  897.53  897.61 1894.11 1894.40
  897.90  897.99  898.57  899.01  899.90  901.36  905.57  907.49  909.30  912.94
  914.42  917.26  919.39  921.42  924.94  926.51  928.65  930.45  931.99  933.14
  934.38  935.38  936.27  938.74  944.72  946.91
BR Coef=-1 , 0 , 0 ,, 0 ,,,0.8,0,1,0,
WSPro=,,,, 1 ,,,, 0 ,,,, 0 ,,,,-1 ,-1 ,-1 , 0 , 0 , 0 , 0 , 0
BC Design=,, 0 ,, 0 ,,,,,,

Type RM Length L Ch R = 1 ,104636.2,163.134600,163.134600,163.134600
XS GIS Cut Line= 2
539861.042550772780589.602688432539757.960953504780027.536716193
#Sta/Elev= 30
  9753.71904.1369829.5461901.5379870.2141894.1039890.5471894.8699910.8811890.201
9931.2141893.5269941.3811894.2989951.5481891.7449961.7151887.9329971.8811886.556
9982.048 1884.049992.2151880.47710002.381879.17910012.551882.26310022.721890.048
10032.881896.43210043.051899.46810063.381900.97210073.551898.51310093.881898.903
10104.051901.22910134.551910.24610144.721912.10210165.051913.65310175.221917.362
10205.721924.15110226.051926.75410246.381930.81710287.051937.17910325.141947.611
#Mann= 3 , 0 , 0
  9753.7  0.0571       0  9753.7  0.0571       010325.14  0.0571       0
#XS Ineff= 2 , 0
       0                               0
Bank Sta=9753.7,10325.14
Exp/Cntr=0.3,0.1

Type RM Length L Ch R = 1 ,104473.1,592.174900,592.174900,592.174900
XS GIS Cut Line= 6
539868.161111325780719.196176842539922.392118424780634.841259643
 539956.49641192780537.487103552539976.100619078780418.924226716
540010.110203117780120.551714867540137.287560552779908.391260892
#Sta/Elev= 30
9616.6651909.7899682.3621904.2499791.9511901.8749812.6831897.7079833.2281890.481
9904.2631888.4299944.6321883.3529964.664 1884.579974.6791883.6129994.7071876.583
10004.721878.20410014.731884.34410024.74 1886.8810044.841884.52810085.12  1887.4
10105.261898.26610125.391904.61810145.551914.75510216.541921.65610247.811934.781
10259.471936.48610289.751935.91410306.111932.05910329.431933.022 10348.11929.501
10387.721933.655 10422.71934.64710445.351931.64810457.681935.333 10488.71937.556
#Mann= 3 , 0 , 0
9616.665  0.1096       09616.665  0.1096       0 10488.7  0.1096       0
#XS Ineff= 2 , 0
       0                               0
Bank Sta=9616.665,10488.7
Exp/Cntr=0.3,0.1

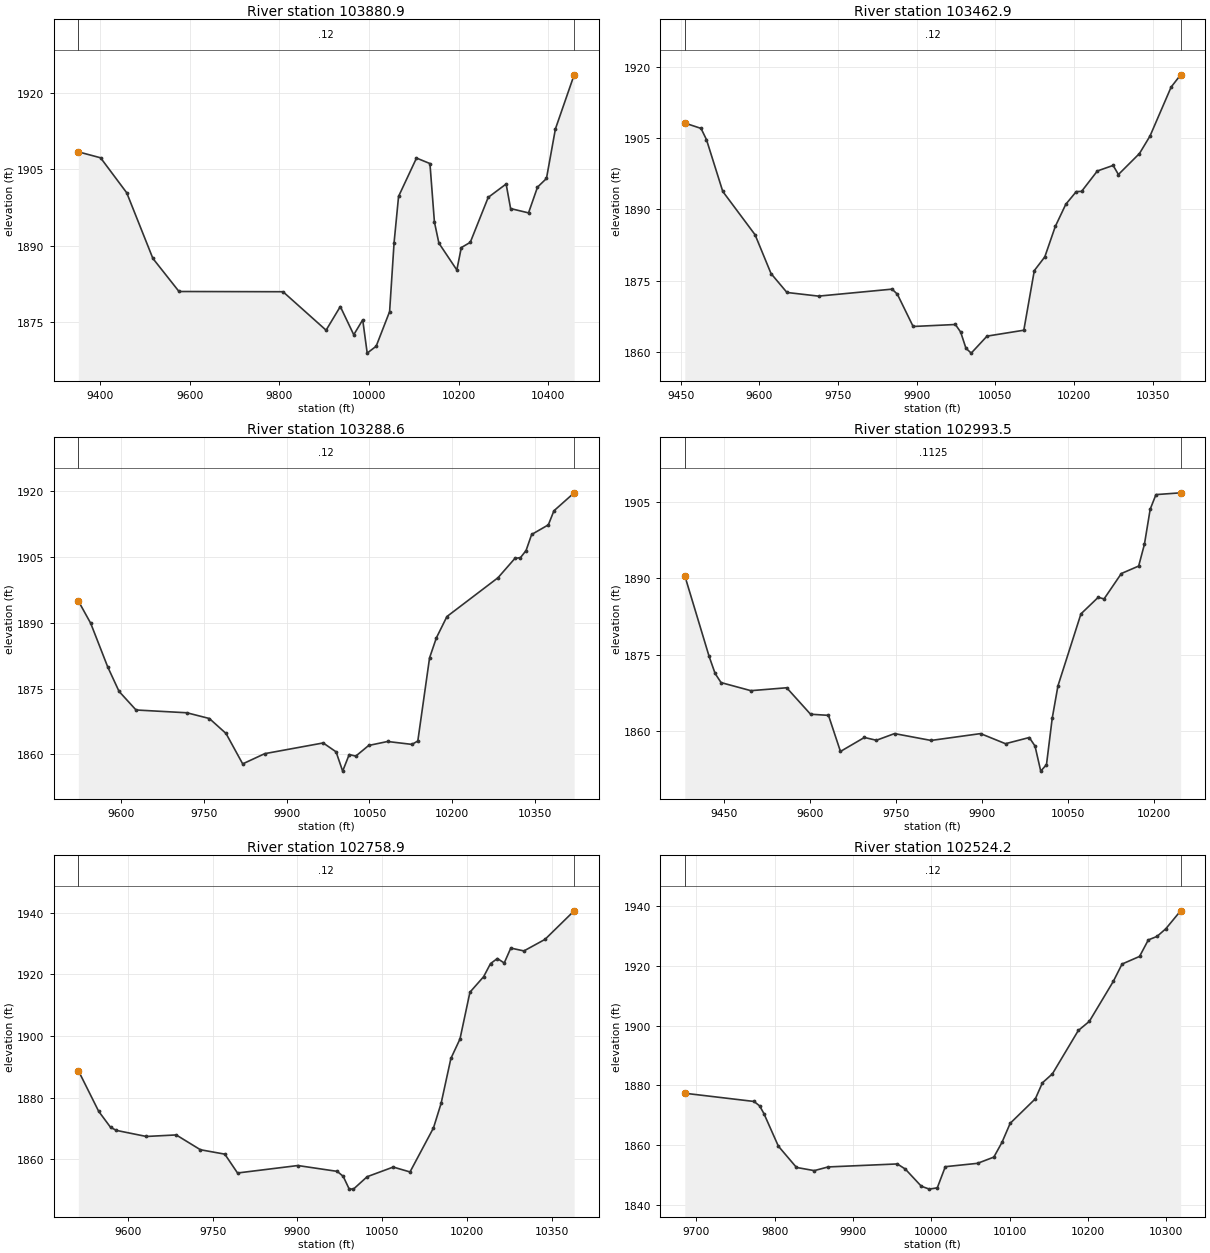
Type RM Length L Ch R = 1 ,103880.9,418.048100,418.048100,418.048100
XS GIS Cut Line= 4
539882.430529058780773.357009709540262.513691247780545.000000015
540390.759782791780496.932927579540916.801449448 780491.72459425
#Sta/Elev= 30
9351.4741908.4019401.1351907.2329459.4661900.3669517.7961887.4899576.1261880.994
9808.2161880.9489904.3291873.3989936.0791878.0439966.0811872.5069986.0821875.437
9996.0821868.89910016.081870.25410046.081877.04710056.091890.60810066.09 1899.66
10106.091907.18210136.091906.10410146.091894.63610156.09 1890.4810196.09 1885.22
10206.091889.61310226.091890.643 10266.11899.461 10306.11902.089 10316.11897.268
 10356.11896.422 10376.11901.474 10396.11903.172 10416.11912.90210457.911923.516
#Mann= 3 , 0 , 0
9351.474    0.12       09351.474    0.12       010457.91    0.12       0
#XS Ineff= 2 , 0
       09767.221                       0
Bank Sta=9351.474,10457.91
Exp/Cntr=0.3,0.1

Type RM Length L Ch R = 1 ,103462.9,174.321800,174.321800,174.321800
XS GIS Cut Line= 6
539825.317773621780927.979266858539962.762144727780892.743139334
540088.435607853780879.117705895 540156.22371358780879.597785539
540475.681064226780906.559999787540762.994184526780884.956779396
#Sta/Elev= 30
9457.9321908.1439488.8931907.0199499.2981904.6519530.3181893.7829591.9111884.681
9622.3491876.5319652.6621872.5629712.9231871.7959853.1041873.2629863.1291872.204
9893.2461865.4179973.7741865.836 9983.841864.2499993.9061860.84610003.971859.823
10034.111863.39310104.241864.63510124.251877.15810144.251880.03710164.261886.429
10184.271891.08710204.321893.75710214.351893.78710244.44 1898.0810274.541899.245
10284.571897.33410324.711901.74410344.831905.42110385.081915.70110403.181918.271
#Mann= 3 , 0 , 0
9457.932    0.12       09457.932    0.12       010403.18    0.12       0
#XS Ineff= 2 , 0
       0                               0
Bank Sta=9457.932,10403.18
Exp/Cntr=0.3,0.1

Type RM Length L Ch R = 1 ,103288.6,295.021200,295.021200,295.021200
XS GIS Cut Line= 6
539913.153114412781062.137659207540143.792893362781113.786062666
540251.211841737781120.705948661540322.813574279781100.941777874
540528.591180659780994.263601136540771.308766936780946.276824633
#Sta/Elev= 30
9522.0231894.9539544.4651889.8659575.2831879.9429595.8281874.3689626.645 1870.13
9718.8141869.4959759.616 1868.19 9789.841864.7859820.0631857.8599860.0661860.189
9966.0451862.6269989.4151860.60110001.341856.21110013.251859.99210025.111859.624
10048.51 1862.0510082.781862.95710126.981862.29710137.631863.06810158.941881.995
10171.291886.55110190.421891.40110283.061900.23910313.621904.62910323.81 1904.82
10333.921906.42610344.031910.07910374.341912.27510384.451915.47210421.141919.564
#Mann= 3 , 0 , 0
9522.023    0.12       09522.023    0.12       010421.14    0.12       0
#XS Ineff= 2 , 0
       0                               0
Bank Sta=9522.023,10421.14
Exp/Cntr=0.3,0.1

Type RM Length L Ch R = 1 ,102993.5,234.671500,234.671500,234.671500
XS GIS Cut Line= 6
539933.991429029781136.763039933540240.611403495781225.142187951
540314.556361663781249.540804839540493.686051448781319.879886006
540594.257771029  781325.2890629540767.715137482781345.470611298
#Sta/Elev= 30
9381.8041890.4669424.2531874.6249434.6591871.2859445.065 1869.499497.0951867.904
9559.5311868.4769601.155 1863.289632.4561863.0589653.326 1855.979695.0661858.715
9716.0731858.1679747.6641859.4789811.3691858.1329897.7741859.4759941.2341857.491
9982.6881858.7059992.7031857.03610002.711852.10710012.731853.38710022.751862.508
10032.761868.86710072.831882.98310103.031886.242 10113.11885.914 10143.31890.906
 10173.51892.37310183.571896.64910193.63 1903.54 10203.71906.40510246.711906.752
#Mann= 3 , 0 , 0
9381.804  0.1125       09381.804  0.1125       010246.71  0.1125       0
#XS Ineff= 2 , 0
       0                               0
Bank Sta=9381.804,10246.71
Exp/Cntr=0.3,0.1

Type RM Length L Ch R = 1 ,102758.9,234.671500,234.671500,234.671500
XS GIS Cut Line= 6
539930.668381145781155.039803306540177.214900776781242.027650153
540250.571763296781285.341939401540384.964331509781497.147284331
540504.026867049781589.679294047540613.082020767781650.372043294
#Sta/Elev= 30
9512.2461888.7589548.256 1875.539569.2561870.3359579.7561869.3339632.5121867.366
9685.4291867.8659728.2261863.0579771.4171861.6269793.9321855.5079900.694 1857.93
  9970.21856.0399980.8171854.4519991.3931850.347    9999 1850.27 10023.31854.303
 10069.41857.43310099.111855.84910140.651870.14910154.111878.09910171.431892.682
10187.551899.02510205.141914.19810229.431919.25110241.571923.49610253.721925.139
10265.811923.68210277.431928.52710300.661927.60310337.941931.34810389.55 1940.62
#Mann= 3 , 0 , 0
9512.246    0.12       09512.246    0.12       010389.55    0.12       0
#XS Ineff= 2 , 0
       0                               0
Bank Sta=9512.246,10389.55
Exp/Cntr=0.3,0.1

Type RM Length L Ch R = 1 ,102524.2,234.671500,234.671500,234.671500
XS GIS Cut Line= 6
539968.232264196781465.149485146540038.940210227781518.151649734
540112.457674226781561.460887684540176.300051175781584.948226307
540345.370107181 781624.85860665540541.933684047781716.880271083
#Sta/Elev= 30
9685.3751877.4129773.7431874.6749780.966 1873.189786.3241870.6449804.8081859.757
9827.9181852.6599850.6571851.5999868.3081852.8299956.5681853.829 9966.791852.131
9987.2361846.3989997.4581845.42610007.661845.86210017.871852.91310058.991854.034
10079.84 1856.1110090.261861.05210100.681867.38310132.861875.58410141.811880.887
 10154.61883.89710187.641898.35110201.741901.40610232.311914.74210243.481920.517
10265.821923.06310276.981928.56310288.151929.74710299.321932.28910318.231938.274
#Mann= 3 , 0 , 0
9685.375    0.12       09685.375    0.12       010318.23    0.12       0
#XS Ineff= 2 , 0
       0                               0
Bank Sta=9685.375,10318.23
Exp/Cntr=0.3,0.1