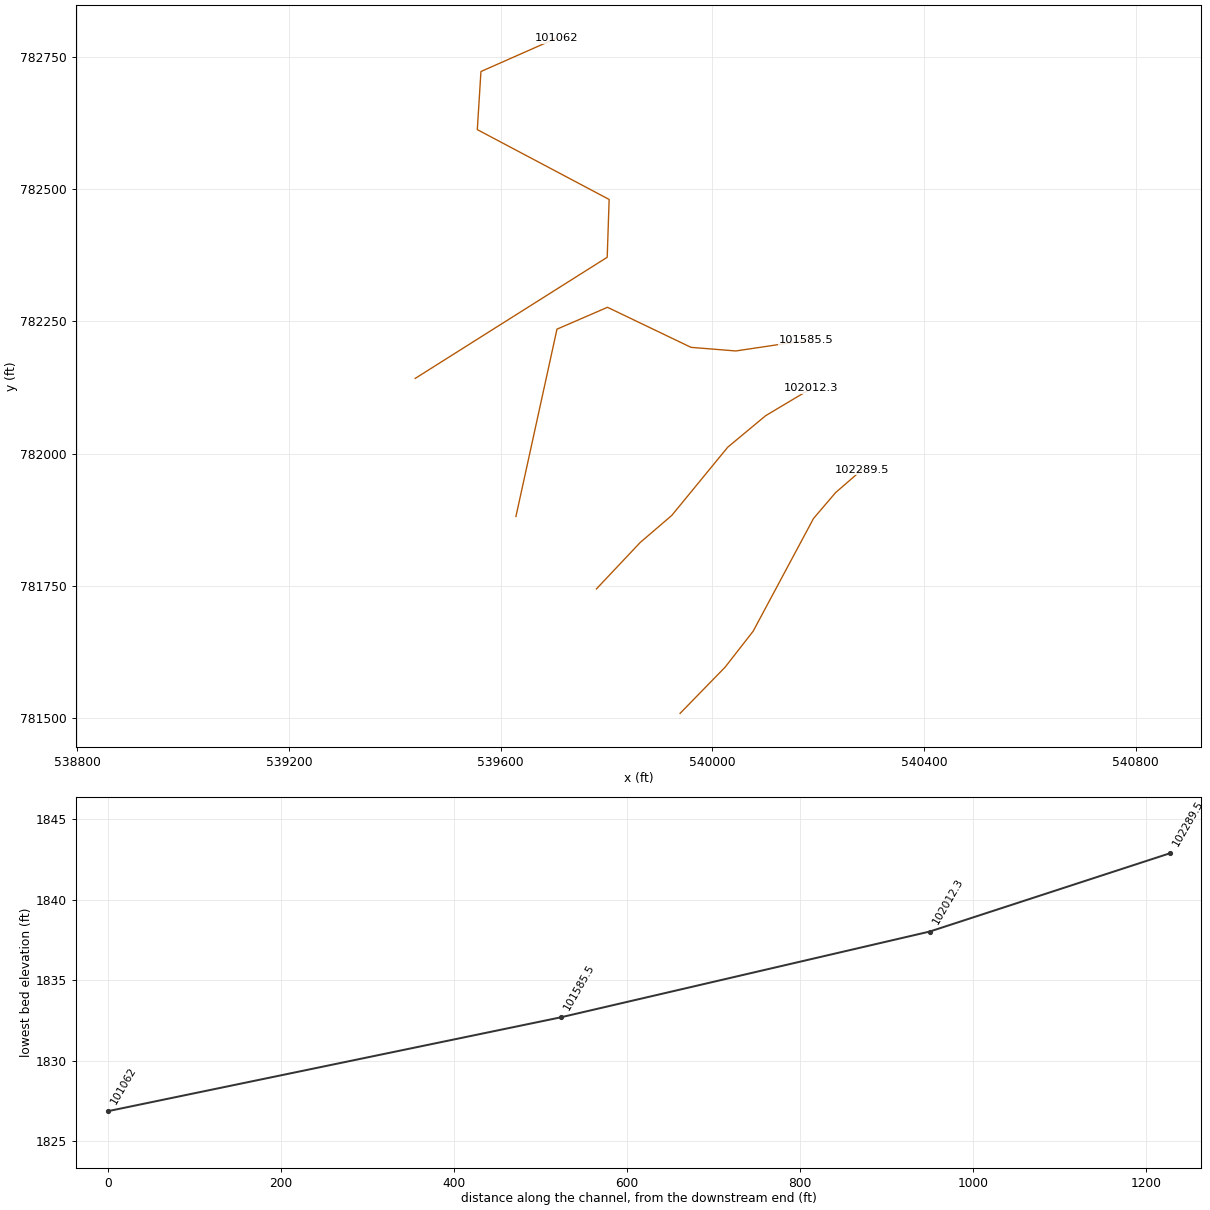
HEC-RAS study 5238_ras.prj: 5238

--- 5238_ras.g01 (geometry) --- (continued)

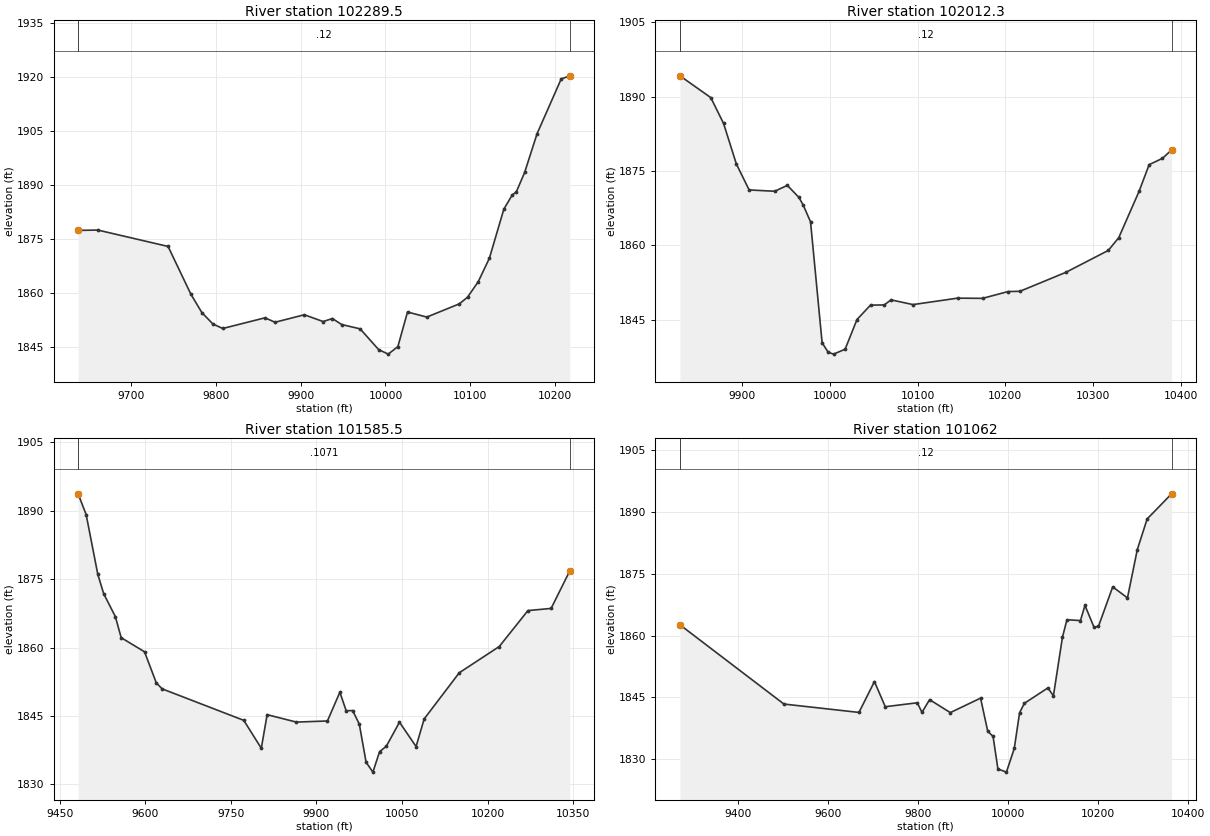
Type RM Length L Ch R = 1 ,102289.5,277.257900,277.257900,277.257900
XS GIS Cut Line= 6
  539939.0748702781509.070116607540024.070007094781596.282687302
540077.204076823781664.403447084540191.236607963781877.389079029
540233.109956196781926.445354562540282.847979758781969.479665727
#Sta/Elev= 30
9636.9751877.3389660.1521877.4439743.2091872.8739770.146 1859.579783.1821854.435
9796.2171851.2589807.8131850.0229857.7281852.9929869.5371851.7579904.1651853.842
9926.339 1851.959937.2711852.7939948.2031851.1249970.0671849.914 9991.931844.134
10003.241842.87710014.621844.97110026.011854.61210048.781853.19610087.261856.889
10096.891858.73310109.54 1863.0510122.711869.59610139.811883.27910149.851887.272
10154.39    188810164.371893.50410179.041904.28910207.521919.53110217.62  1920.4
#Mann= 3 , 0 , 0
9636.975    0.12       09636.975    0.12       010217.62    0.12       0
#XS Ineff= 2 , 0
       0                               0
Bank Sta=9636.975,10217.62
Exp/Cntr=0.3,0.1

Type RM Length L Ch R = 1 ,102012.3,426.756600,426.756600,426.756600
XS GIS Cut Line= 6
539780.910638772 781744.26380773539863.678979084781832.033222709
539923.384099506781883.218932531 540029.20631879782012.211763034
540100.860175457782071.761258223540187.463178144782123.374339418
#Sta/Elev= 30
9829.2381894.198 9864.351889.8039878.9251884.5919893.5011876.4159908.0771871.165
9937.2281870.8989951.6241872.0879964.8371869.6579969.7151868.1029978.0511864.739
9991.265 1840.329998.1181838.41510004.341838.02410017.491839.01910031.011845.009
10046.421847.91510062.141847.95310069.741848.97810094.871848.02210145.651849.324
10174.121849.28110203.271850.65710216.721850.70410268.941854.52110317.491858.956
 10329.41861.53610352.511870.86710364.021876.26710379.171877.53810389.62 1879.24
#Mann= 3 , 0 , 0
9829.238    0.12       09829.238    0.12       010389.62    0.12       0
#XS Ineff= 2 , 0
       0                               0
Bank Sta=9829.238,10389.62
Exp/Cntr=0.3,0.1

Type RM Length L Ch R = 1 ,101585.5,523.500100,523.500100,523.500100
XS GIS Cut Line= 6
539628.828491092781881.254700854539706.397897571782235.253264859
539801.870229423782276.580569148539959.744608134 782200.87229301
540044.396809906782194.064650491540176.873268008782213.846983522
#Sta/Elev= 30
9482.0731893.6879496.1451889.1419516.6191876.0249526.8561871.8149547.3311866.787
9557.5681862.1649598.5171859.0659618.9921852.3049629.2291850.9549772.551 1844.04
9803.2621837.924  9813.51845.2899864.7411843.6629919.2241843.9059941.0181850.205
9952.063 1846.159963.4351846.1859975.1071843.2239987.0231834.864 9998.941832.695
 10010.71837.194 10022.41838.35410045.561843.63610074.671838.30310088.841844.354
10150.361854.47110220.531860.226 10270.8  1868.110311.431868.57210344.111876.785
#Mann= 3 , 0 , 0
9482.073  0.1071       09482.073  0.1071       010344.11  0.1071       0
#XS Ineff= 2 , 0
       09946.965                       0
Bank Sta=9482.073,10344.11
Exp/Cntr=0.3,0.1

Type RM Length L Ch R = 1 ,  101062,53.586900,53.586900,53.586900
XS GIS Cut Line= 6
539438.430857062782142.169977114539801.332455128 782371.12300761
          539805782480.398457661 539555.81322968782612.414466336
539562.701623768782722.212229699539704.710296482782784.942182288
#Sta/Elev= 30
9270.4371862.6349501.4681843.3979668.2271841.3649702.6291848.8519726.725 1842.75
9797.7411843.707 9808.281841.3869825.2481844.4679871.2631841.3219938.4981844.835
9954.4691836.7749966.2561835.5519977.075 1827.649995.9661826.867 10013.41832.608
10025.191841.26910035.811843.57110088.191847.32110100.411845.37510120.451859.593
10130.471863.87210160.521863.67110170.541867.34410190.581862.077 10200.61862.287
10232.211871.855   102651869.17610286.871880.90810308.731888.34610363.081894.446
#Mann= 3 , 0 , 0
9270.437    0.12       09270.437    0.12       010363.08    0.12       0
#XS Ineff= 2 , 0
       09940.734        10041.21       0
Bank Sta=9270.437,10363.08
Exp/Cntr=0.3,0.1