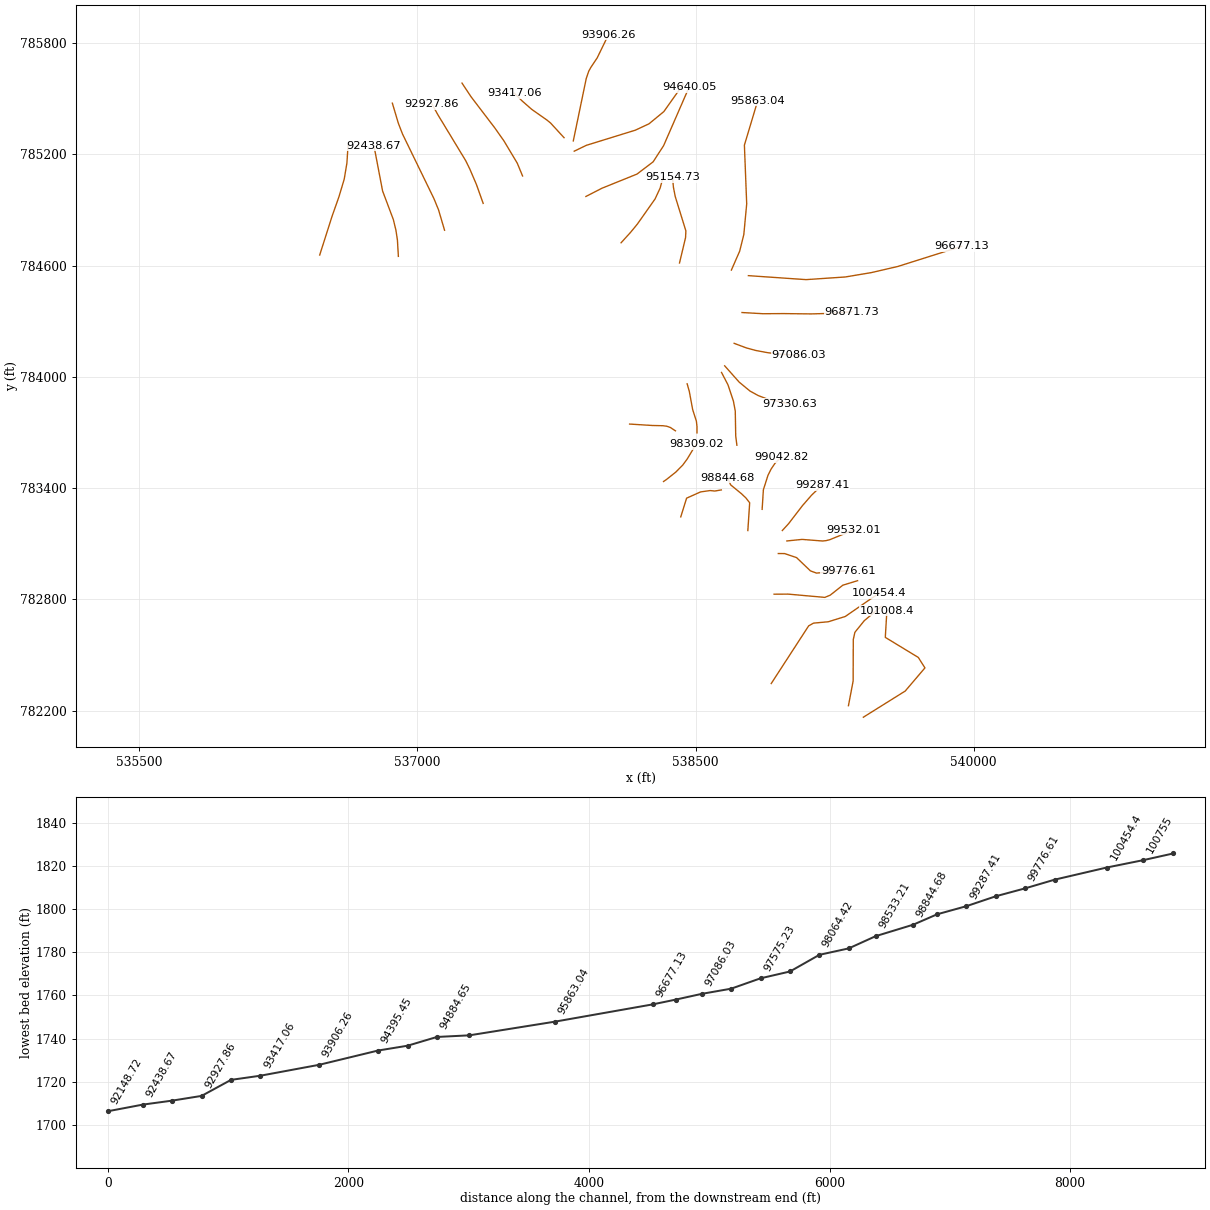
HEC-RAS study 5238_ras.prj: 5238

--- 5238_ras.g01 (geometry) --- (continued)

Type RM Length L Ch R = 3 ,  101037,,,
BEGIN DESCRIPTION:
END DESCRIPTION:
Bridge Culvert--1,0,-1,-1, 0
Deck Dist Width WeirC Skew NumUp NumDn MinLoCord MaxHiCord MaxSubmerge Is_Ogee
9.897150,33.792600,2.6,0, 35, 35, , , 0.95, 0, 0,0,,
 9842.04 9842.16 9851.51 9854.52 9866.89 9868.51 9879.25 9885.52 9889.27 9893.43
 9898.03 9909.26 9915.34 9920.50 9931.74 9937.26 9942.98 9950.03 9950.03 9954.22
 9959.17 9962.2710028.7710028.7710030.0010034.1110041.0810042.2010045.2410055.87
10066.5110071.5510077.1410087.7810088.38
 1842.10 1842.11 1842.46 1842.61 1843.22 1843.32 1843.64 1843.80 1843.94 1844.17
 1844.33 1844.54 1844.79 1844.97 1845.10 1845.29 1845.47 1845.61 1845.61 1845.69
 1845.91 1845.26 1845.30 1845.30 1845.30 1845.83 1846.10 1846.15 1846.12 1846.06
 1845.80 1845.73 1845.59 1845.31 1845.30
  842.10  842.11  842.46  842.61  843.22  843.32  843.64  843.80  843.94  844.17
  844.33  844.54  844.79  844.97  845.10  845.29  845.47  845.61 1841.11 1841.19
 1841.41 1840.76 1840.80  845.30  845.30  845.83  846.10  846.15  846.12  846.06
  845.80  845.73  845.59  845.31  845.30
 9842.04 9842.16 9851.51 9854.52 9866.89 9868.51 9879.25 9885.52 9889.27 9893.43
 9898.03 9909.26 9915.34 9920.50 9931.74 9937.26 9942.98 9954.22 9959.17 9960.45
 9960.45 9962.2710030.0010034.1110039.1910039.1910041.0810042.2010045.2410055.87
10066.5110071.5510077.1410087.7810088.38
 1842.10 1842.11 1842.46 1842.61 1843.22 1843.32 1843.64 1843.80 1843.94 1844.17
 1844.33 1844.54 1844.79 1844.97 1845.10 1845.29 1845.47 1845.69 1845.91 1845.64
 1845.64 1845.26 1845.30 1845.83 1846.03 1846.03 1846.10 1846.15 1846.12 1846.06
 1845.80 1845.73 1845.59 1845.31 1845.30
  842.10  842.11  842.46  842.61  843.22  843.32  843.64  843.80  843.94  844.17
  844.33  844.54  844.79  844.97  845.10  845.29  845.47  845.69  845.91  845.64
 1841.14 1840.76 1840.80 1841.33 1841.53  846.03  846.10  846.15  846.12  846.06
  845.80  845.73  845.59  845.31  845.30
Pier Skew, UpSta & Num, DnSta & Num=  ,9989.40, 2 ,9999.82, 2 , 0 , 0 , 0 ,,
    2.00    2.00
  845.28 1845.28
    2.00    2.00
  845.28 1845.28
BR Coef=-1 , 0 , 0 ,, 0 ,,,0.8,0,1,0,
WSPro=,,,, 1 ,,,, 0 ,,,, 0 ,,,,-1 ,-1 ,-1 , 0 , 0 , 0 , 0 , 0
BC Design=,, 0 ,, 0 ,,,,,,

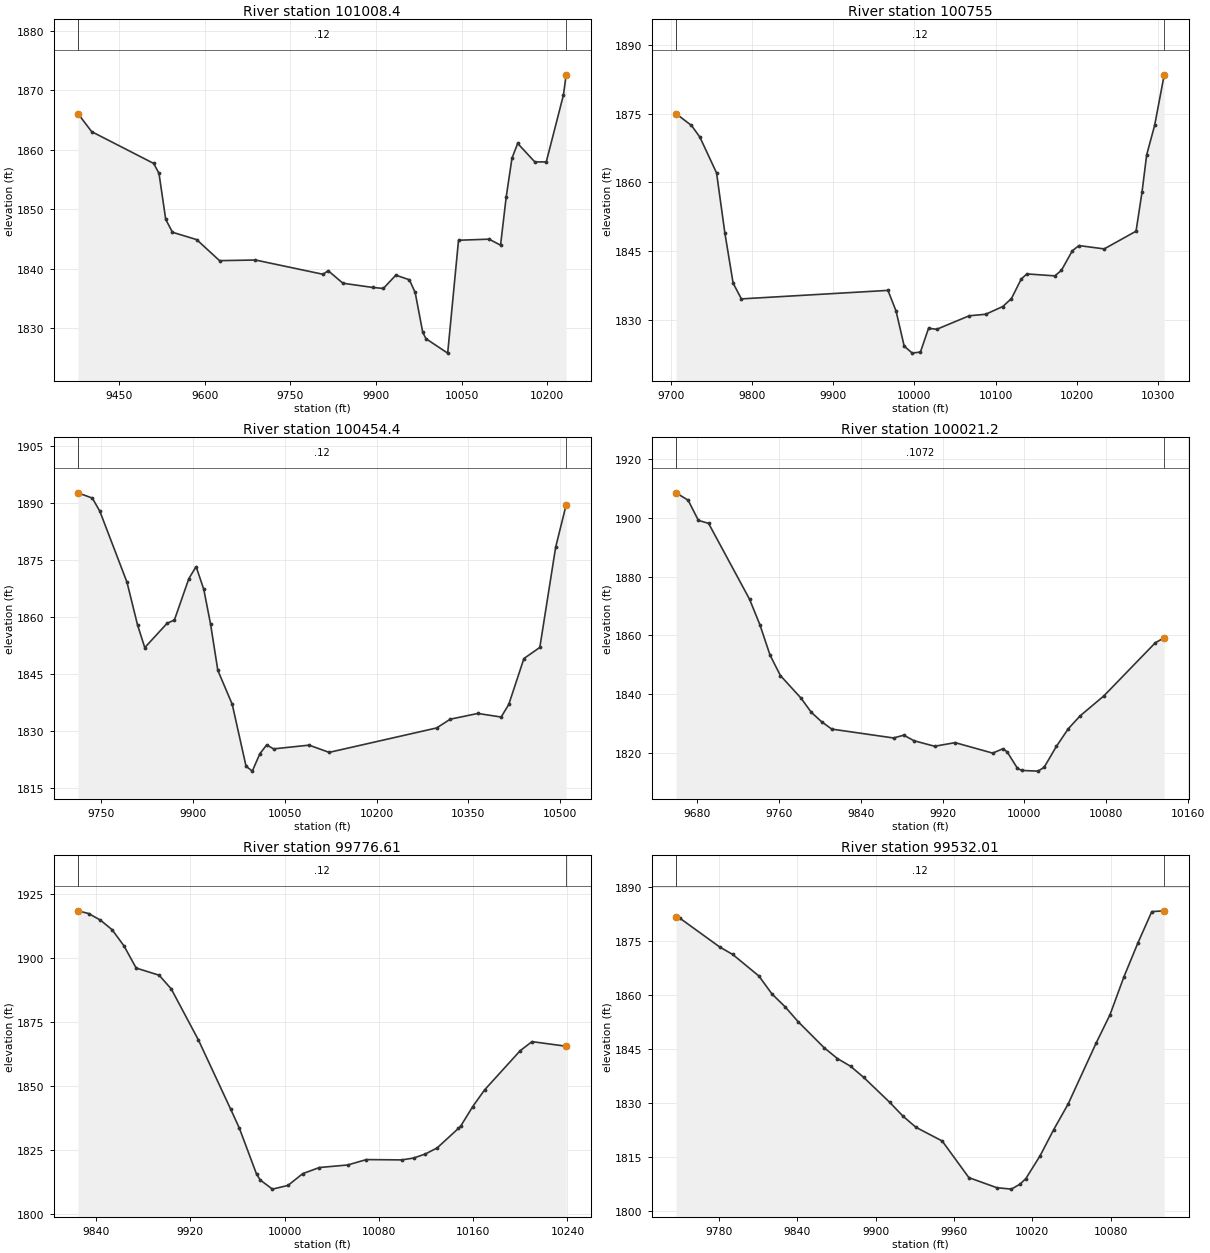
Type RM Length L Ch R = 1 ,101008.4,253.416300,253.416300,253.416300
XS GIS Cut Line= 6
539404.582388788782164.735622644539630.238843977782305.770907089
 539736.56257531782430.585579202 539700.94380942782486.990202889
 539522.91991657782595.199274376539531.499365002782739.767980665
#Sta/Elev= 30
9377.7521866.0999401.8291863.0619510.3271857.7329519.7541856.0679531.5471848.331
9543.3391846.1659585.7981844.9259625.8871841.3929688.8671841.4999807.3061839.099
9816.1641839.7069842.1121837.5979894.6351836.8859912.972 1836.729934.7591838.955
 9958.48 1838.189968.673 1836.059982.0041829.3339987.6661828.27710025.651825.856
10044.651844.82110098.251845.00310118.281843.992 10128.31852.14910138.321858.608
10148.341861.08710178.391857.97510198.421857.98210228.481869.21510233.25 1872.61
#Mann= 3 , 0 , 0
9377.752    0.12       09377.752    0.12       010233.25    0.12       0
#XS Ineff= 2 , 0
       09947.034                       0
Bank Sta=9377.752,10233.25
Exp/Cntr=0.3,0.1

Type RM Length L Ch R = 1 ,  100755,300.583700,300.583700,300.583700
XS GIS Cut Line= 6
539324.172970767782226.756270961539349.478307022782360.125717707
539350.286445182782583.828631558 539358.94440279782622.605086322
 539409.38962214782684.976225704539501.534964803782762.619498957
#Sta/Elev= 30
9706.3961874.9819725.4441872.4099735.7431869.8759756.3411862.0369766.5671848.909
9776.7231837.9759786.8781834.5459967.3851836.4029977.387 1831.879987.3891824.221
9997.3921822.70310007.391822.95110017.39 1828.14 10027.41827.90610067.431830.858
10087.681831.18710108.761832.87810119.411834.60710131.511838.88610138.431839.997
10172.851839.57310180.931840.75710194.421845.05610202.641846.18510233.651845.458
10272.881849.32310280.241857.84810285.961865.98310295.751872.41110307.581883.465
#Mann= 3 , 0 , 0
9706.396    0.12       09706.396    0.12       010307.58    0.12       0
#XS Ineff= 2 , 0
       09958.664                       0
Bank Sta=9706.396,10307.58
Exp/Cntr=0.3,0.1

Type RM Length L Ch R = 1 ,100454.4,433.210700,433.210700,433.210700
XS GIS Cut Line= 6
 538907.82087251782346.400294056539109.606630933782657.183903396
539135.660750882782672.026993093539215.684712935782679.454200601
539307.075830915782707.863208666539488.175949899 782833.05794101
#Sta/Elev= 30
9711.5221892.6879735.0161891.3029747.2981887.8449791.7331869.1369809.025 1857.86
9820.8431851.8839857.4691858.3019869.3161859.1519893.0091870.0959904.8561873.238
9917.4551867.208 9928.55 1858.039940.3971845.876 9963.941836.949 9986.54 1820.62
9996.7851819.32110009.141823.90610020.351826.23610031.591825.18510089.671826.172
10122.521824.26510298.31  1830.710320.791833.01710365.721834.52310403.981833.582
10416.371836.89110441.221849.011 10467.21851.92610493.171878.38510510.291889.519
#Mann= 3 , 0 , 0
9711.522    0.12       09711.522    0.12       010510.29    0.12       0
#XS Ineff= 2 , 0
       0                10311.02       0
Bank Sta=9711.522,10510.29
Exp/Cntr=0.3,0.1

Type RM Length L Ch R = 1 ,100021.2,244.598100,244.598100,244.598100
XS GIS Cut Line= 6
538923.231687308782828.057687753538999.330460482782828.492426533
539196.554905554 782810.81693259539225.497059216782822.588629145
539294.021384368782876.660665221539373.459524074782900.906620359
#Sta/Elev= 30
9659.7091908.577 9671.521906.0729681.5221899.2019691.523 1898.169731.5241872.297
 9741.55 1863.679751.5941853.2049761.639 1846.299781.7281838.6089791.7731833.773
9801.8171830.5519811.8621828.022 9872.131824.9989882.1741825.9489892.2191824.052
9912.3081822.1739932.3471823.4089968.9591819.8389978.9731821.3139983.1141820.281
9993.103  1814.79997.2691813.92910013.271813.69210019.271814.998 10031.21822.115
10042.851828.141 10054.41832.53310077.711839.37810127.861857.46210136.551859.161
#Mann= 3 , 0 , 0
9659.709  0.1072       09659.709  0.1072       010136.55  0.1072       0
#XS Ineff= 2 , 0
       0                               0
Bank Sta=9659.709,10136.55
Exp/Cntr=0.3,0.1

Type RM Length L Ch R = 1 ,99776.61,244.598100,244.598100,244.598100
XS GIS Cut Line= 6
 538946.05996332783047.344060663538980.020232784783047.033582953
539044.366537317783025.387229169539119.340343337782953.706376046
539151.735557471782941.967042704539323.792516557782954.712545151
#Sta/Elev= 30
9824.7311918.3659833.721 1917.329843.7261914.7519853.7321910.9929863.8621904.615
9874.1191896.0149893.613 1893.229903.8981887.8549927.0021867.8729954.2791840.926
9961.5521833.6219976.2511815.5559979.4161813.2299989.7181809.67810002.871811.112
10015.471815.735 10029.51818.11410053.551819.10810069.421821.21910099.441821.092
10109.471821.813 10119.51823.40910129.521825.79110147.571833.41910149.621834.415
10159.671841.93410169.731848.436 10199.91863.73110209.961867.28510238.921865.483
#Mann= 3 , 0 , 0
9824.731    0.12       09824.731    0.12       010238.92    0.12       0
#XS Ineff= 2 , 0
       0                               0
Bank Sta=9824.731,10238.92
Exp/Cntr=0.3,0.1

Type RM Length L Ch R = 1 ,99532.01,244.598200,244.598200,244.598200
XS GIS Cut Line= 6
538992.062230819783115.157850616539074.198330036 783123.50670527
539183.749944073783114.971222287539202.471923784783116.621155676
539223.420621827783121.860181855 539353.90517904783174.893659227
#Sta/Elev= 30
9747.1291881.7349750.1241881.3279780.5931873.3339790.6091871.244 9810.641865.256
9820.6551860.2629830.6721856.7099840.7021852.5499860.7631845.2639870.7931842.304
9880.8231840.1689890.8541837.0859910.914 1830.119920.9451826.3039930.9751823.178
9951.0451819.378 9971.461809.1999992.8951806.39210004.081805.99510010.651807.386
10015.151808.942 10026.1 1815.3210036.381822.49710047.481829.64210068.851846.534
10079.541854.45810090.221865.00510100.911874.424 10111.61883.17310121.121883.388
#Mann= 3 , 0 , 0
9747.129    0.12       09747.129    0.12       010121.12    0.12       0
#XS Ineff= 2 , 0
       0                               0
Bank Sta=9747.129,10121.12
Exp/Cntr=0.3,0.1

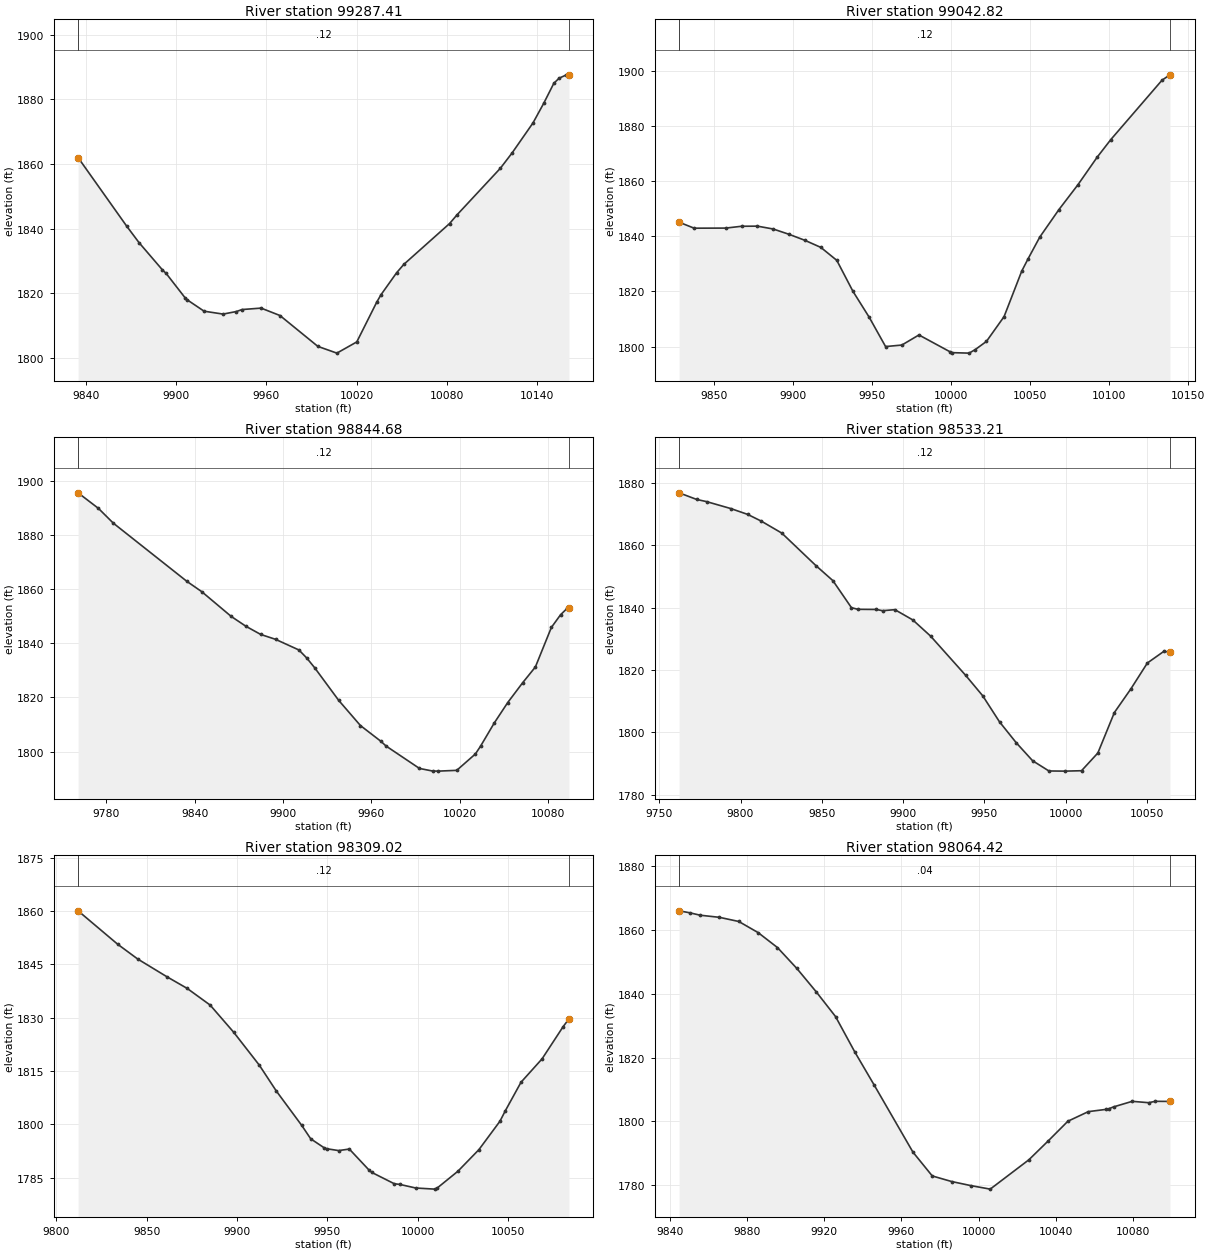
Type RM Length L Ch R = 1 ,99287.41,244.598100,244.598100,244.598100
XS GIS Cut Line= 6
538967.455415491783171.340413836539000.445149307783207.118741887
 539075.86090789783305.094283655539124.505962642783361.087809759
539177.525871742783412.101033791539182.672919925783416.151694903
#Sta/Elev= 30
9834.6981861.9829867.1211840.6889875.2191835.6579890.8551827.1719893.326 1826.08
9905.9421818.5199907.2591817.9329918.557 1814.399931.1721813.4999940.0661814.295
9943.7881814.9059956.469 1815.359969.0181813.0589994.249 1803.49 10006.91801.403
10020.151804.87710033.391817.16710036.21 1819.4610046.641826.29510051.451828.903
10081.881841.54210086.841844.23910115.691858.67610123.511863.43410137.391872.718
10144.531878.79810151.271885.00510154.771886.57510159.461887.57710161.32 1887.62
#Mann= 3 , 0 , 0
9834.698    0.12       09834.698    0.12       010161.32    0.12       0
#XS Ineff= 2 , 0
       0                               0
Bank Sta=9834.698,10161.32
Exp/Cntr=0.3,0.1

Type RM Length L Ch R = 1 ,99042.82,198.132800,198.132800,198.132800
XS GIS Cut Line= 6
538858.762974751783285.494880253538865.461973655783391.018923854
538890.090285756783468.596366929 538906.63792997783501.993356562
 538928.44325013783534.360493389 538961.40479127783567.705057371
#Sta/Elev= 30
 9827.89 1845.129837.4011842.9499857.4121842.9849867.4171843.6479877.423 1843.69
9887.4281842.6529897.434 1840.739907.4761838.5499917.5721835.9749927.6691831.274
 9937.861820.0639948.1931810.6089958.5271799.996 9968.811800.5459979.6391804.207
    99991798.19410000.741797.78610011.371797.61510015.191798.87510022.341801.865
 10033.51810.86810044.661827.36110048.771831.93310056.091839.72510068.151849.659
 10080.21858.69310092.371868.691   101011875.08210133.461896.66810138.451898.594
#Mann= 3 , 0 , 0
 9827.89    0.12       0 9827.89    0.12       010138.45    0.12       0
#XS Ineff= 2 , 0
       0                               0
Bank Sta=9827.89,10138.45
Exp/Cntr=0.3,0.1

Type RM Length L Ch R = 1 ,98844.68,311.474700,311.474700,311.474700
XS GIS Cut Line= 6
538781.712740034 783171.18968454538791.557712525783320.870852545
538771.095240951783347.250322849538747.155675173783369.938244984
538688.881057441783417.690236151538672.787851185783456.017974228
#Sta/Elev= 30
9760.7681895.4959774.6081889.7469784.6291884.3369834.7371862.7989844.7591859.028
9864.8021849.8779874.8241846.2379884.8451843.2359894.8671841.4449910.7721837.508
9915.9981834.5989921.4711830.9479937.7871818.9189952.5551809.6229966.3331803.862
9969.9611802.0669992.6421793.79910001.53 1792.84 10005.31792.80410017.961793.089
10030.63 1799.1310034.121801.98610043.471810.58510052.621818.11810062.641825.347
10071.391831.23810082.241845.81410088.471850.48810093.08 1852.9310094.191853.155
#Mann= 3 , 0 , 0
9760.768    0.12       09760.768    0.12       010094.19    0.12       0
#XS Ineff= 2 , 0
       0                               0
Bank Sta=9760.768,10094.19
Exp/Cntr=0.3,0.1

Type RM Length L Ch R = 1 ,98533.21,224.186900,224.186900,224.186900
XS GIS Cut Line= 6
538419.950050324783244.700106353538451.503275722  783345.8855021
538526.824009985783379.549447432538578.588624209783386.950993955
538602.961157769783384.251738429538638.704324096783390.329722047
#Sta/Elev= 30
9762.2181876.7939773.0071874.6739779.1811873.9639793.9571871.7569804.4311869.864
9812.7721867.7119825.3811863.8749846.3311853.4619856.8061848.6219868.2091839.951
9872.1861839.4179883.561 1839.379887.3351838.9759894.9351839.3069905.9421836.017
9916.9121830.8159938.3991818.2759948.9651811.6689959.294 1803.31 9969.571796.614
9979.6231790.8459989.6641787.5559999.7041787.50310009.731787.63510019.771793.318
10029.941806.31210040.081813.89410050.221822.19310060.371825.93610064.121825.691
#Mann= 3 , 0 , 0
9762.218    0.12       09762.218    0.12       010064.12    0.12       0
#XS Ineff= 2 , 0
       0                               0
Bank Sta=9762.218,10064.12
Exp/Cntr=0.3,0.1

Type RM Length L Ch R = 1 ,98309.02,244.598100,244.598100,244.598100
XS GIS Cut Line= 6
538327.034570445783435.590362972538344.120014511783447.426008913
538393.524013783783486.755622684538430.219083581783523.786628384
538454.072485113783556.099234061538503.408654321783637.525899056
#Sta/Elev= 30
9812.1011860.066 9834.011850.6689845.046 1846.539861.1021841.5699872.3551838.281
9885.1371833.5689898.1291825.9449912.3361816.6699921.7171809.4159935.7951799.728
 9940.75 1795.979948.1651793.4529949.6731793.1739956.215 1792.669962.1031793.091
9973.0521787.1579974.5321786.5219986.9621783.3419990.0821783.1459998.8151782.142
10009.281781.82510010.471782.04110022.12 1786.8410033.761792.924 10045.41800.912
10048.341803.82110057.041811.86910068.691818.44810080.361827.51710083.56 1829.69
#Mann= 3 , 0 , 0
9812.101    0.12       09812.101    0.12       010083.56    0.12       0
#XS Ineff= 2 , 0
       0                               0
Bank Sta=9812.101,10083.56
Exp/Cntr=0.3,0.1

Type RM Length L Ch R = 1 ,98064.42,244.598100,244.598100,244.598100
XS GIS Cut Line= 6
538144.146828443783745.438123965538266.619598086783737.777238065
  538322.8559115783736.528280906538344.366563301783733.838977173
 538363.84161116783727.018282151538391.337621318783708.934674462
#Sta/Elev= 28
9844.9081865.9259850.4051865.3189855.7741864.5589865.795 1863.899875.8151862.591
9885.8361859.1089895.8561854.4259905.877  1847.99915.8971840.5969925.918 1832.84
9935.9391821.7129945.9591811.376    99661790.4159976.0071782.959 9986.011781.216
9996.0141779.93110006.021778.83310026.041788.01710036.111793.95610046.221800.074
10056.821803.08710066.191803.80110067.571804.02210069.86 1804.5610079.541806.306
10088.061805.88210091.511806.314 10099.11806.278
#Mann= 3 , 0 , 0
9844.908    0.04       09844.908    0.04       0 10099.1    0.04       0
#XS Ineff= 2 , 0
       0                               0
Bank Sta=9844.908,10099.1
Exp/Cntr=0.3,0.1

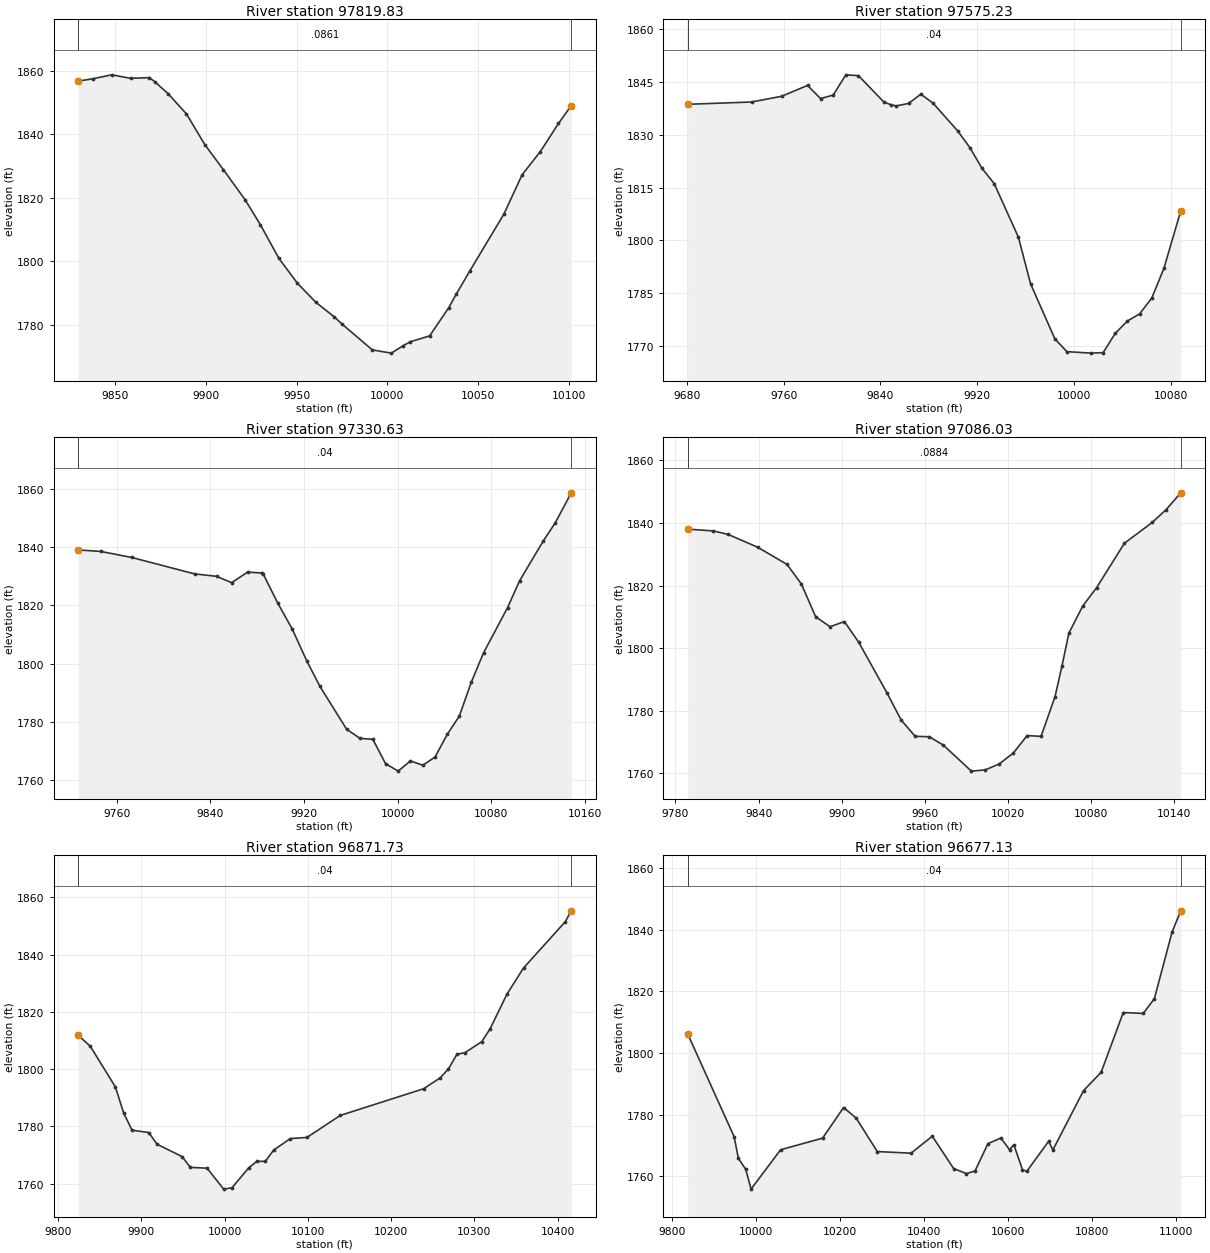
Type RM Length L Ch R = 1 ,97819.83,244.598200,244.598200,244.598200
XS GIS Cut Line= 6
538454.428522829783962.657171707538465.949829642783922.119287074
538484.183936472783823.520453206538504.135640789783761.163097062
538507.411819546 783732.95809044538507.362968948783697.983354341
#Sta/Elev= 30
9829.8821856.6769837.9621857.4149848.3271858.6519858.6911857.5529869.0561857.774
9872.0411856.4659879.2811852.7659889.4511846.354 9899.621836.631 9909.79  1828.8
9921.8091819.2729930.1291811.4989940.2991800.9259950.468 1793.119960.638  1787.1
9970.8071782.4919975.0291780.2599991.7291772.11210002.181771.10410008.441773.353
10012.71 1774.7110023.231776.51610033.75 1785.3910037.791789.56110045.281796.883
10064.131814.86310074.141827.22210084.14  1834.510094.141843.34710101.161848.999
#Mann= 3 , 0 , 0
9829.882  0.0861       09829.882  0.0861       010101.16  0.0861       0
#XS Ineff= 2 , 0
       0                               0
Bank Sta=9829.882,10101.16
Exp/Cntr=0.3,0.1

Type RM Length L Ch R = 1 ,97575.23,244.598100,244.598100,244.598100
XS GIS Cut Line= 6
538639.801772899784023.800581552538674.487197342783957.278742938
538703.866144069783869.411090296538713.912287896783815.455500694
538716.344365151783681.203820343538722.623934251783631.322790345
#Sta/Elev= 30
9680.7641838.6869733.4951839.3369758.3091840.9579779.7981844.0529790.5421840.309
9800.9841841.3069811.4251847.0629821.8661846.8299842.7491839.3679848.5841838.569
9853.071 1838.239863.2431838.9249873.4151841.5649883.5861838.9779903.9241831.083
9913.9491826.3459923.9751820.452    99341816.149 9954.031800.8959964.0321787.682
9984.0361772.0749994.0381768.37310014.041767.94610024.041768.08710034.041773.559
10044.081777.07810054.131779.09410064.191783.57410074.241792.03510088.171808.385
#Mann= 3 , 0 , 0
9680.764    0.04       09680.764    0.04       010088.17    0.04       0
#XS Ineff= 2 , 0
       0                               0
Bank Sta=9680.764,10088.17
Exp/Cntr=0.3,0.1

Type RM Length L Ch R = 1 ,97330.63,244.598100,244.598100,244.598100
XS GIS Cut Line= 6
538656.831473882 784059.45651799538735.454629383783971.171260349
538793.127399474783923.555950126538838.041670525783898.878370837
538889.305177979783879.618507947 539008.66137827783853.707586435
#Sta/Elev= 30
9726.9541839.074 9746.091838.5589772.5631836.4979826.3751830.8479845.1871830.009
9858.1361827.8349871.701 1831.449883.9841831.1599885.1141830.7849897.5461820.817
9909.9771811.8769922.2171801.0799933.6271792.1949956.4471777.4979967.8571774.392
9978.8451774.0499989.6471765.73710000.431763.136   100111766.62910021.561765.177
10032.011767.96510042.371775.71410052.731782.01810063.091793.76610073.451803.757
10094.051819.29510104.191828.42810124.461842.11910134.591848.25110148.421858.672
#Mann= 3 , 0 , 0
9726.954    0.04       09726.954    0.04       010148.42    0.04       0
#XS Ineff= 2 , 0
       0                               0
Bank Sta=9726.954,10148.42
Exp/Cntr=0.3,0.1

Type RM Length L Ch R = 1 ,97086.03,214.299700,214.299700,214.299700
XS GIS Cut Line= 6
538707.923897156784180.705107757538773.709607366784156.065526784
538824.878860145784142.165043711538891.689016343784129.792443638
538969.993077249784121.350238956539055.617200329784117.181921325
#Sta/Elev= 30
9788.8441838.0419807.3851837.4639818.112 1836.339839.3021832.2529860.4621826.786
9870.8241820.5369881.186 1810.039891.5491806.8699901.9111808.5149912.2711801.868
9932.611 1785.739942.7821777.0969952.9521771.8489963.122 1771.729973.2921769.037
9993.5241760.734 10003.61761.13410013.65 1763.05 10023.71766.47110033.75 1772.09
10043.791771.83810053.841784.49110058.861794.26510063.871804.81910073.89 1813.49
 10083.91819.35910103.921833.53110123.941840.16210133.961844.24110144.591849.636
#Mann= 3 , 0 , 0
9788.844  0.0884       09788.844  0.0884       010144.59  0.0884       0
#XS Ineff= 2 , 0
       0                               0
Bank Sta=9788.844,10144.59
Exp/Cntr=0.3,0.1

Type RM Length L Ch R = 1 ,96871.73,194.605200,194.605200,194.605200
XS GIS Cut Line= 6
538750.397775796784346.869835639538864.067574278784340.453397957
538973.384431186784341.163067682539123.458168373784339.394541735
539233.631576185784342.500187991539342.069507255784351.433562685
#Sta/Elev= 30
 9824.041811.8379838.6651807.9679868.7131793.7899878.7291784.6469888.7451778.679
9908.7771777.8619918.7931773.7829948.8231769.4629958.8231765.6989978.8231765.412
9998.8241758.09410008.821758.57410028.831765.52810038.831767.82310048.831767.789
10058.831771.71710078.831775.74910098.831776.14710138.831783.83610238.851793.147
10258.861796.95110268.871800.13610278.87 1805.1410288.871805.81210308.891809.608
10318.911814.11810338.971826.13410359.03 1835.36 10409.21851.53110416.331855.316
#Mann= 3 , 0 , 0
 9824.04    0.04       0 9824.04    0.04       010416.33    0.04       0
#XS Ineff= 2 , 0
       0                               0
Bank Sta=9824.04,10416.33
Exp/Cntr=0.3,0.1

Type RM Length L Ch R = 1 ,96677.13,814.085700,814.085700,814.085700
XS GIS Cut Line= 6
538784.790292827784545.747865178539095.959779652784524.293232599
539307.662722874784538.638674782 539448.45756654784562.304796707
539590.705510606784595.297941974539934.516255899784703.917105595
#Sta/Elev= 30
9836.6281806.1999947.2341772.8289957.2851765.8179974.844 1762.259987.4371755.843
10057.671768.60810157.751772.39110207.781782.323 10237.81778.88410287.981768.038
10368.441767.50810419.021773.02110469.771762.51810500.291760.88810520.731761.757
10551.431770.59510582.181772.42110602.781768.65210613.081770.24510633.671762.147
10643.971761.61710695.791771.35110706.161768.588 10779.11787.81410820.911793.746
10873.641813.15110921.151812.85610947.621817.614 10989.91839.29211010.521846.147
#Mann= 3 , 0 , 0
9836.628    0.04       09836.628    0.04       011010.52    0.04       0
#XS Ineff= 2 , 0
       09929.216        10108.62       0
Bank Sta=9836.628,11010.52
Exp/Cntr=0.3,0.1

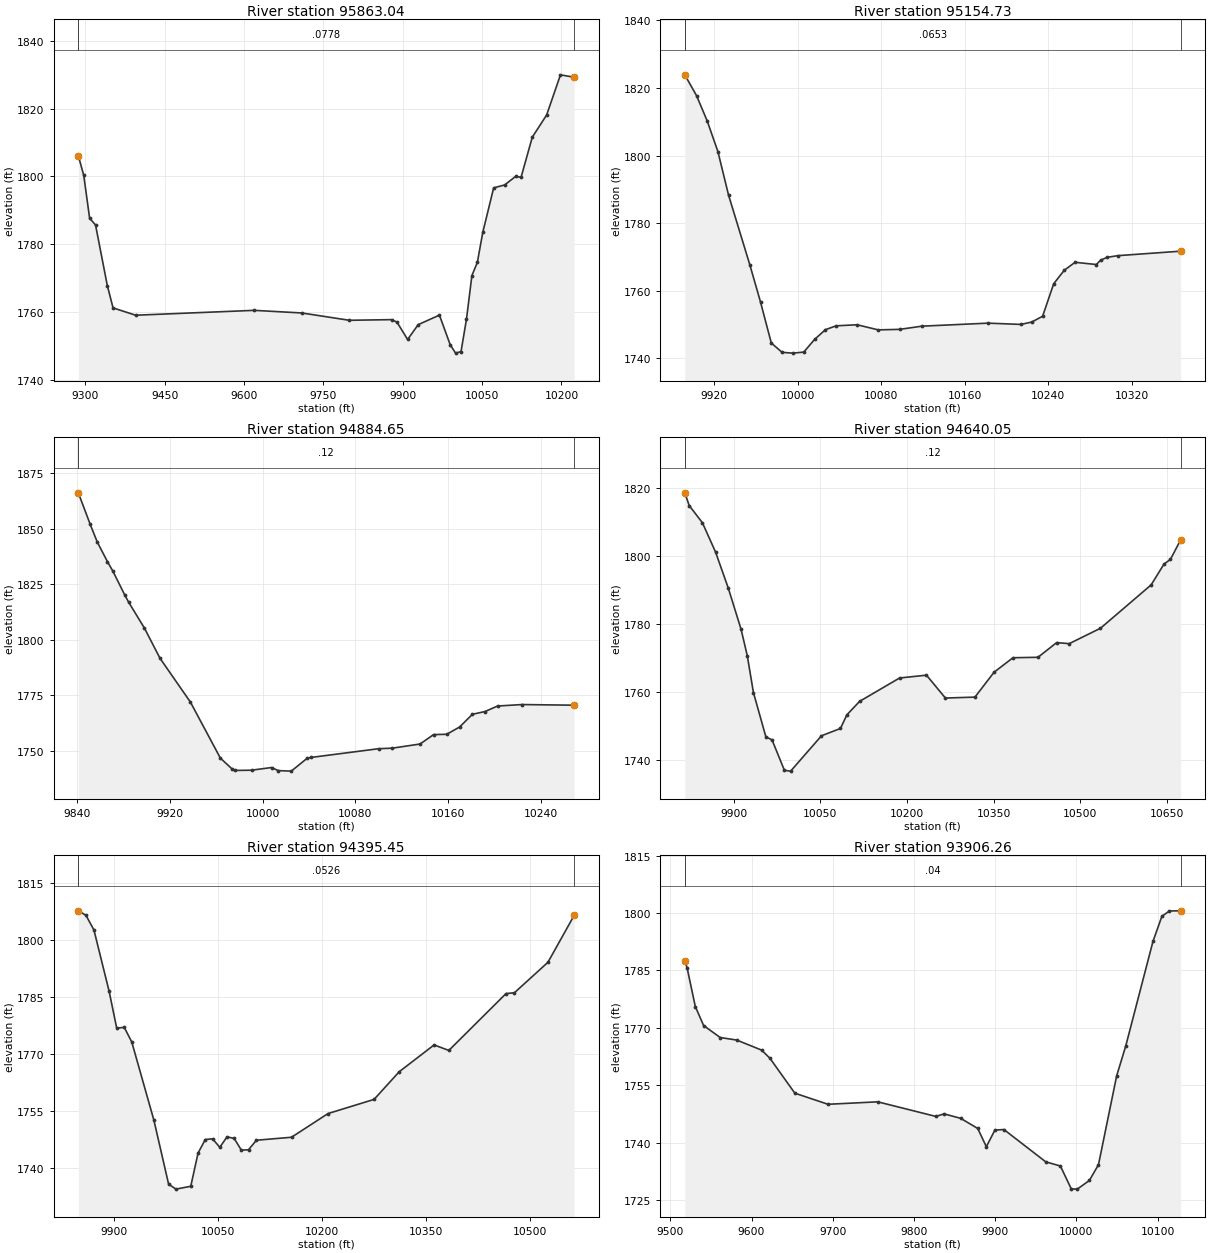
Type RM Length L Ch R = 1 ,95863.04,708.309200,708.309200,708.309200
XS GIS Cut Line= 6
538692.936091157784575.855267192538737.698957216784677.918946576
538760.011847391 784767.33376666538775.504746733784932.849733356
 538763.12843626785249.552891988538834.834653784785488.646622427
#Sta/Elev= 30
9286.5081806.1259296.7061800.3739307.8581787.663 9319.011785.7049341.3131767.783
 9352.161761.1879394.9591759.0219618.8481760.4619708.8941759.6919798.9361757.525
9879.0021757.7189889.0471756.9719909.1381751.8639929.2281756.2429969.3191759.051
9989.6391750.3219999.8671747.82610010.17 1748.2910020.441757.82210030.721770.726
   100411774.60810051.281783.48210071.831796.63610092.581797.49910113.361800.018
10123.751799.79110144.881811.60410172.051818.17310198.22 1830.0310224.081829.311
#Mann= 3 , 0 , 0
9286.508  0.0778       09286.508  0.0778       010224.08  0.0778       0
#XS Ineff= 2 , 0
       09724.127                       0
Bank Sta=9286.508,10224.08
Exp/Cntr=0.3,0.1

Type RM Length L Ch R = 1 ,95154.73,270.083300,270.083300,270.083300
XS GIS Cut Line= 6
538413.228406145784613.977503921 538445.86724234784750.704796955
538447.503803292784787.193945751538390.203089106784972.269679043
538380.250841393785023.346893206 538375.76803075785075.003058723
#Sta/Elev= 30
9891.8351823.8969903.0991817.7299913.3191810.2299923.539 1801.199933.758 1788.29
9954.1981767.6089964.4171756.6079974.7221744.5059985.0871741.7389995.453 1741.51
10005.821741.819 10016.21745.56110026.56 1748.45 10036.81749.59110056.951749.907
10077.191748.39410097.831748.54810118.981749.48910182.431750.38410213.931750.008
10224.321750.71410234.711752.42710245.361762.05910255.491766.04910265.821768.398
 10286.21767.74210290.251769.01510296.391769.85610306.571770.35910366.971771.691
#Mann= 3 , 0 , 0
9891.835  0.0653       09891.835  0.0653       010366.97  0.0653       0
#XS Ineff= 2 , 0
       0                               0
Bank Sta=9891.835,10366.97
Exp/Cntr=0.3,0.1

Type RM Length L Ch R = 1 ,94884.65,244.598200,244.598200,244.598200
XS GIS Cut Line= 6
538098.106606874 784722.90435575538150.192280305784780.236344001
538186.623940728784824.699512968538281.452330452784959.329394859
538308.820282937785018.106990165538325.080462073785078.560081085
#Sta/Elev= 30
9841.231 1866.289851.4831852.0329857.5731844.0459866.3541835.1999871.0841830.861
9881.2251820.2059884.5941816.9489898.1051805.3319911.6151791.6479937.7771771.915
9963.633 1746.61 9973.61 1741.789976.5421741.0579990.5481741.17610007.711742.381
10013.481740.98810024.721740.75510038.211746.47610041.731746.929 10099.91750.861
10111.841751.11910135.72 1752.9910147.311757.23310158.641757.36710169.741760.664
 10180.81766.39710191.621767.63210202.441770.11710223.551770.78310268.441770.491
#Mann= 3 , 0 , 0
9841.231    0.12       09841.231    0.12       010268.44    0.12       0
#XS Ineff= 2 , 0
       0                               0
Bank Sta=9841.231,10268.44
Exp/Cntr=0.3,0.1

Type RM Length L Ch R = 1 ,94640.05,244.598100,244.598100,244.598100
XS GIS Cut Line= 6
537908.418341826784972.660571409537995.129937582 785017.14725176
538183.807302856785093.353741762538270.814349603785159.282031595
 538327.52682247785246.714096649538464.415750066785560.852929264
#Sta/Elev= 30
9815.4931818.4479823.0911814.7229845.9791809.6489868.6341801.0859890.7511790.451
9912.8681778.3689923.5951770.6249934.3181759.7379955.7641746.7789966.4861745.857
9987.9321736.9089998.6541736.68910052.051747.07710084.851749.21710095.871753.201
10117.991757.18310187.161764.04810233.721764.88210266.481758.161 10317.61758.433
10350.721765.74610383.431769.99910426.721770.13310459.091774.45210480.671774.133
10534.841778.66210622.581791.40910644.811797.52510655.931798.88710673.551804.625
#Mann= 3 , 0 , 0
9815.493    0.12       09815.493    0.12       010673.55    0.12       0
#XS Ineff= 2 , 0
       0                10234.33       0
Bank Sta=9815.493,10673.55
Exp/Cntr=0.3,0.1

Type RM Length L Ch R = 1 ,94395.45,489.196300,489.196300,489.196300
XS GIS Cut Line= 6
537845.541689383785216.875144223537910.720801326785248.424095803
538175.200097342785330.164845416538248.624392525 785364.42998036
538328.524665624785430.120180175538432.906624803785577.334625558
#Sta/Elev= 30
9848.0651807.6759858.9881806.5099870.5371802.6639892.494 1786.499903.4131776.825
9914.3311777.0089925.1281773.1749957.0271752.6159978.2921735.7639988.9251734.463
10010.241735.21710020.771743.95510031.211747.51610041.661747.69510052.111745.461
10062.531748.22610072.871747.797 10083.21744.71810093.531744.81810104.961747.328
10155.541748.10910208.191754.34210274.661758.07110310.841765.33410361.191772.397
10382.481770.95110464.931785.90310477.041786.12510525.421794.13710563.231806.479
#Mann= 3 , 0 , 0
9848.065  0.0526       09848.065  0.0526       010563.23  0.0526       0
#XS Ineff= 2 , 0
       0                               0
Bank Sta=9848.065,10563.23
Exp/Cntr=0.3,0.1

Type RM Length L Ch R = 1 ,93906.26,489.196200,489.196200,489.196200
XS GIS Cut Line= 6
537840.514656812785272.317379326 537910.22325563785608.288664336
537923.872371263785648.567249329537935.526180993 785669.25851256
 537969.41344253785720.092949037538030.692308898785846.053876481
#Sta/Elev= 30
9517.8331787.5039520.5731785.7769530.7861775.5839540.9991770.6199561.4251767.485
9581.8511766.815 9612.491764.1859622.7031762.0539653.3421752.9349694.1941750.034
9755.4721750.6739826.9621746.8629837.1751747.5299857.6011746.3579878.6051743.712
9889.1631738.9339899.7221743.2939910.8711743.4289962.3451734.9849980.3731733.901
9993.7881727.91710001.191727.856 10016.1 1730.1310027.281734.24110049.66 1757.46
10060.851765.27110094.351792.58410105.331799.147 10114.61800.56610128.431800.597
#Mann= 3 , 0 , 0
9517.833    0.04       09517.833    0.04       010128.43    0.04       0
#XS Ineff= 2 , 0
       0                               0
Bank Sta=9517.833,10128.43
Exp/Cntr=0.3,0.1

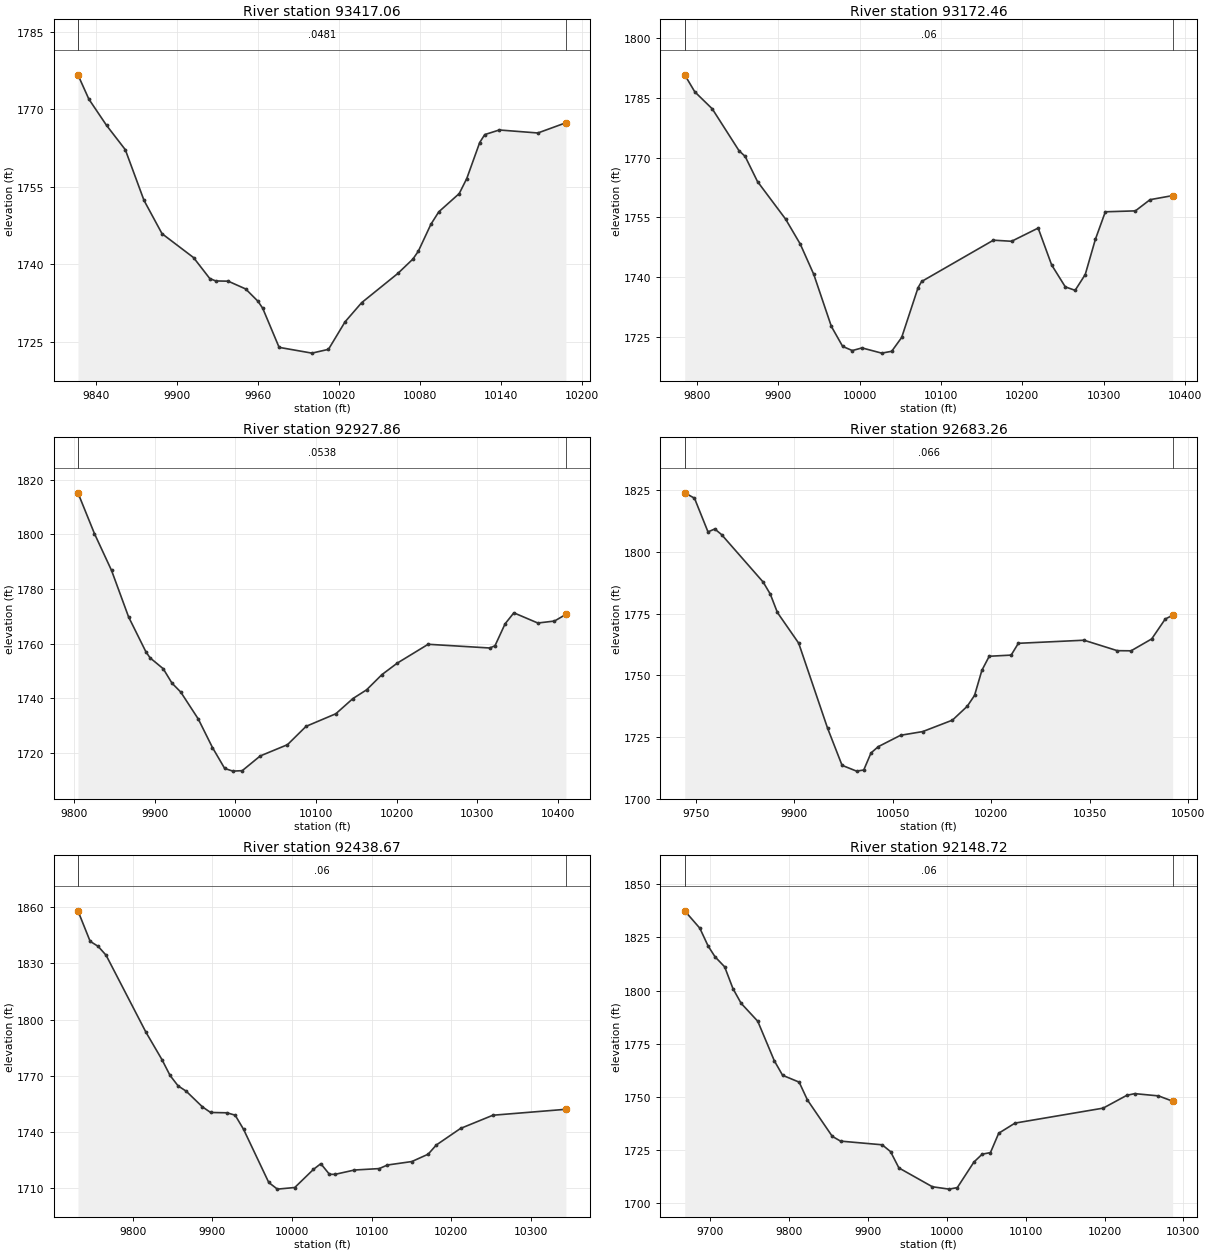
Type RM Length L Ch R = 1 ,93417.06,244.598100,244.598100,244.598100
XS GIS Cut Line= 6
537790.601462394785289.678490445537718.145647138785368.574285954
537699.010386527785384.248864681 537616.12182945785442.609644353
537564.238272578785488.127319381537522.448691776785529.916869037
#Sta/Elev= 30
9826.4791776.7189834.5691772.0099847.7141766.9099861.5741762.2119875.4341752.384
9888.7781745.935 9912.15  1741.39924.1681737.2389928.6291736.7799937.8131736.733
9950.7391735.2279959.8011732.859 9963.361731.4959975.524 1723.919999.8381722.792
10012.091723.52510024.381728.85510036.661732.56410063.48 1738.2310074.65 1741.02
10078.651742.53310087.961747.74710093.811750.16910108.971753.71110114.561756.627
10124.141763.60110127.871765.13910138.681766.03110167.22 1765.4510187.991767.431
#Mann= 3 , 0 , 0
9826.479  0.0481       09826.479  0.0481       010187.99  0.0481       0
#XS Ineff= 2 , 0
       0                               0
Bank Sta=9826.479,10187.99
Exp/Cntr=0.3,0.1

Type RM Length L Ch R = 1 ,93172.46,244.598200,244.598200,244.598200
XS GIS Cut Line= 6
537566.958673648785083.176565084537538.600171424785151.765709001
537466.851667145785271.799628709537417.132324541785342.401936129
537289.187342537785510.242975603 537240.28607319 785584.07227638
#Sta/Elev= 30
9784.798 1790.86 9797.211786.5819818.7251782.2989851.6251771.7699859.1181770.351
9874.3531764.0119908.8891754.572 9926.941748.2879943.5361740.6759965.1851727.581
 9979.091722.5479990.9411721.50510002.87 1722.1710027.091720.85810039.381721.316
10051.671724.79410071.831737.32510076.261738.88110164.511749.26610186.871748.994
10219.551752.31310236.121743.04710252.951737.51910265.041736.65310277.471740.634
 10289.9 1749.4610302.181756.40810339.181756.64110357.191759.45710384.991760.484
#Mann= 3 , 0 , 0
9784.798    0.06       09784.798    0.06       010384.99    0.06       0
#XS Ineff= 2 , 0
       0                               0
Bank Sta=9784.798,10384.99
Exp/Cntr=0.3,0.1

Type RM Length L Ch R = 1 ,92927.86,244.598100,244.598100,244.598100
XS GIS Cut Line= 6
537354.535335447784935.403808066537318.287721036785037.085595482
537282.016625138785121.630210268537259.781780676785166.626786305
537110.586583726785412.883422509537078.130166062785471.431251846
#Sta/Elev= 30
9804.7391815.1659825.2621800.2269846.3591786.8279867.5821769.7759889.0431757.033
9894.2281754.8299910.503 1750.869921.3591745.5929932.2481742.3249954.0271732.451
 9971.581722.0389986.6941714.4139996.8461713.427 10008.51713.59610030.811718.979
10064.581723.09610087.621729.79410124.511734.39310145.781739.96710162.681743.145
10181.771748.72810200.861752.94210239.031759.80110315.371758.44110321.881759.249
10334.461767.295 10345.31771.29510375.011767.57310395.631768.28810409.821770.715
#Mann= 3 , 0 , 0
9804.739  0.0538       09804.739  0.0538       010409.82  0.0538       0
#XS Ineff= 2 , 0
       0                               0
Bank Sta=9804.739,10409.82
Exp/Cntr=0.3,0.1

Type RM Length L Ch R = 1 ,92683.26,244.598100,244.598100,244.598100
XS GIS Cut Line= 6
537146.347036221 784790.57716514 537113.77921036784900.696861076
537089.548082285784960.027531904536919.560894663785309.426248403
536896.880460745785368.175669838536864.802537966785475.922359819
#Sta/Elev= 30
9733.2031824.0079748.0711821.8399768.6881808.1759778.9971809.364 9789.441807.058
9852.765 1787.829863.5671782.9529874.3691775.5179906.7741763.0899950.7761728.651
9972.8351713.5949994.8931711.23710005.891711.69910016.911718.59510027.971721.152
10061.871725.75710095.771727.26910140.961731.90210163.461737.50910174.631741.921
10185.791752.08110196.961757.78210230.371758.25210241.32 1763.0310341.321764.283
10392.021760.04510413.011759.98910444.421764.81110465.061772.88610476.331774.375
#Mann= 3 , 0 , 0
9733.203   0.066       09733.203   0.066       010476.33   0.066       0
#XS Ineff= 2 , 0
       0                               0
Bank Sta=9733.203,10476.33
Exp/Cntr=0.3,0.1

Type RM Length L Ch R = 1 ,92438.67,289.950500,289.950500,289.950500
XS GIS Cut Line= 6
536897.252171106 784649.67337419536892.171991647784737.596984359
536883.912145716 784791.39141693536870.277186792784847.838894509
536812.221127785785002.142778046536765.675012491785245.507823128
#Sta/Elev= 30
9730.8651858.1469746.2091841.8549756.2311839.1659766.254 1834.429816.3661793.262
9836.5761778.5639846.6931770.147 9856.811764.5699866.9281761.7559887.3941753.353
9897.6811750.3679918.257 1750.189928.5441748.9139939.0441741.4019970.7951712.928
9981.6181709.38510003.49 1710.2510027.011719.95510036.231722.97810047.081717.304
10054.091717.28610078.54  1719.6 10109.71720.36510119.951722.269 10150.71724.133
 10171.21728.05510181.381732.94910211.911741.82410252.621748.88410344.371752.057
#Mann= 3 , 0 , 0
9730.865    0.06       09730.865    0.06       010344.37    0.06       0
#XS Ineff= 2 , 0
       0                               0
Bank Sta=9730.865,10344.37
Exp/Cntr=0.3,0.1

Type RM Length L Ch R = 1 ,92148.72,443.843900,443.843900,443.843900
XS GIS Cut Line= 6
536473.027220566784656.844902686536539.728446862784865.961216309
536577.109621067  784971.9309234536605.228514179785066.008892242
536619.791067315785153.379673443536626.208444623785252.943552377
#Sta/Elev= 30
9667.846 1837.589687.0181829.3859697.5091820.9959706.2721815.909 9718.491811.162
 9728.981800.9139739.3591793.9669760.4521785.4989781.4341766.8519791.924 1760.01
9812.9051756.7839823.3961748.3689854.8681731.2259865.3591728.9629918.1411727.227
9928.7451724.0139939.3491716.3139981.7641707.43510002.911706.31710013.371707.035
10034.381719.06310044.891722.80410055.391723.54910065.851732.68210086.551737.462
10198.211744.51610228.27 1750.5710238.291751.35510268.351750.29710286.331747.787
#Mann= 3 , 0 , 0
9667.846    0.06       09667.846    0.06       010286.33    0.06       0
#XS Ineff= 2 , 0
       0                               0
Bank Sta=9667.846,10286.33
Exp/Cntr=0.3,0.1