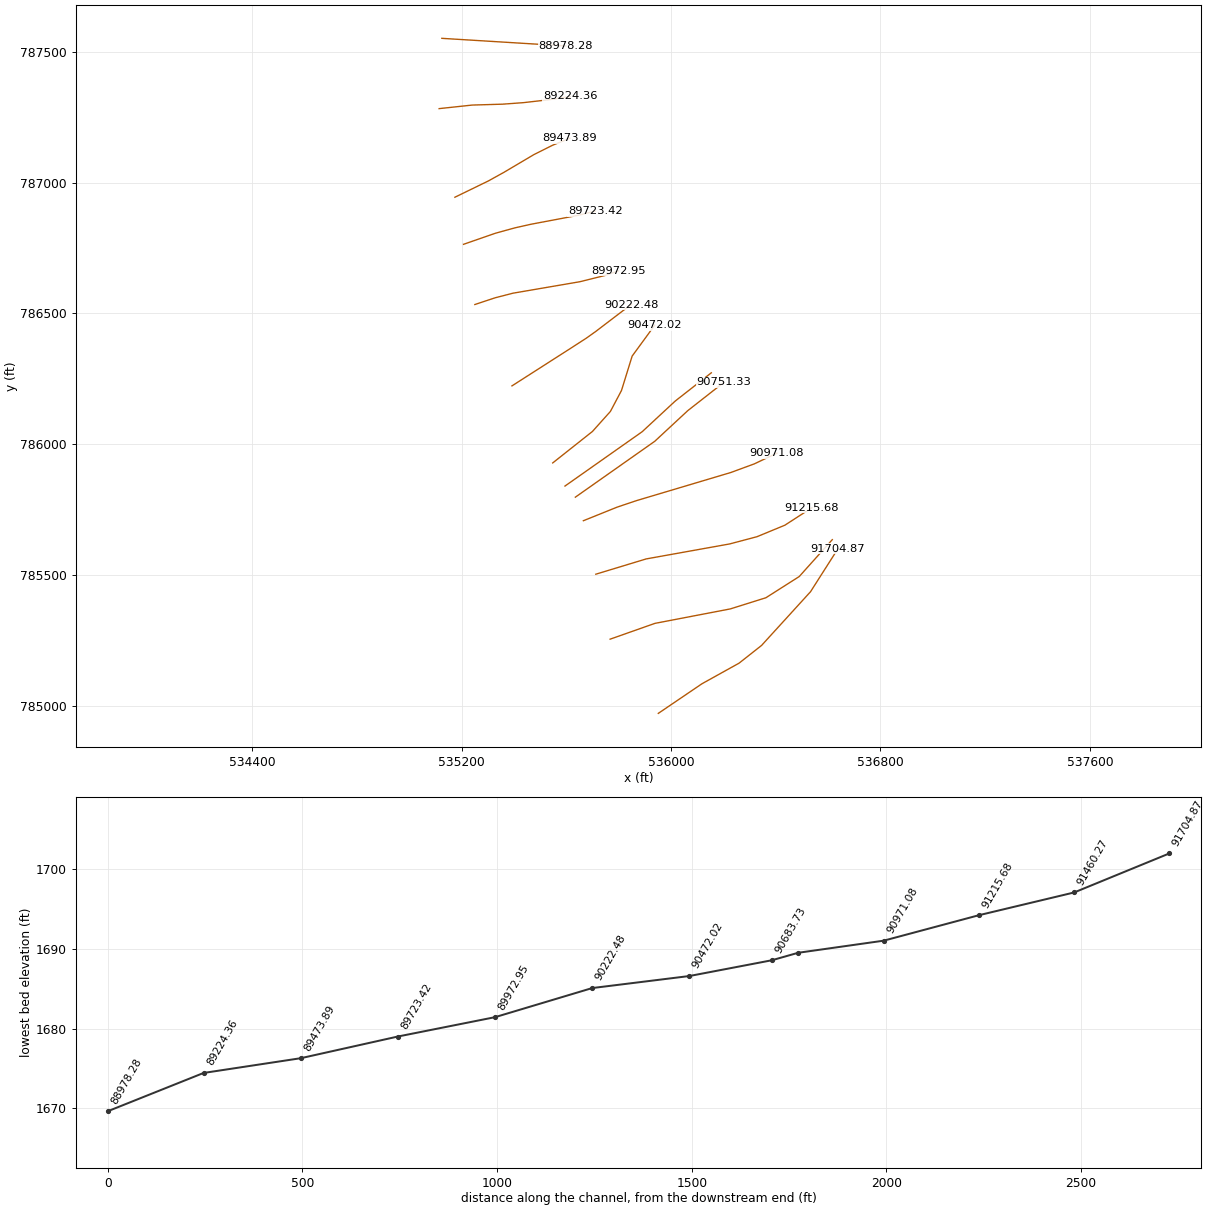
HEC-RAS study 5238_ras.prj: 5238

--- 5238_ras.g01 (geometry) --- (continued)

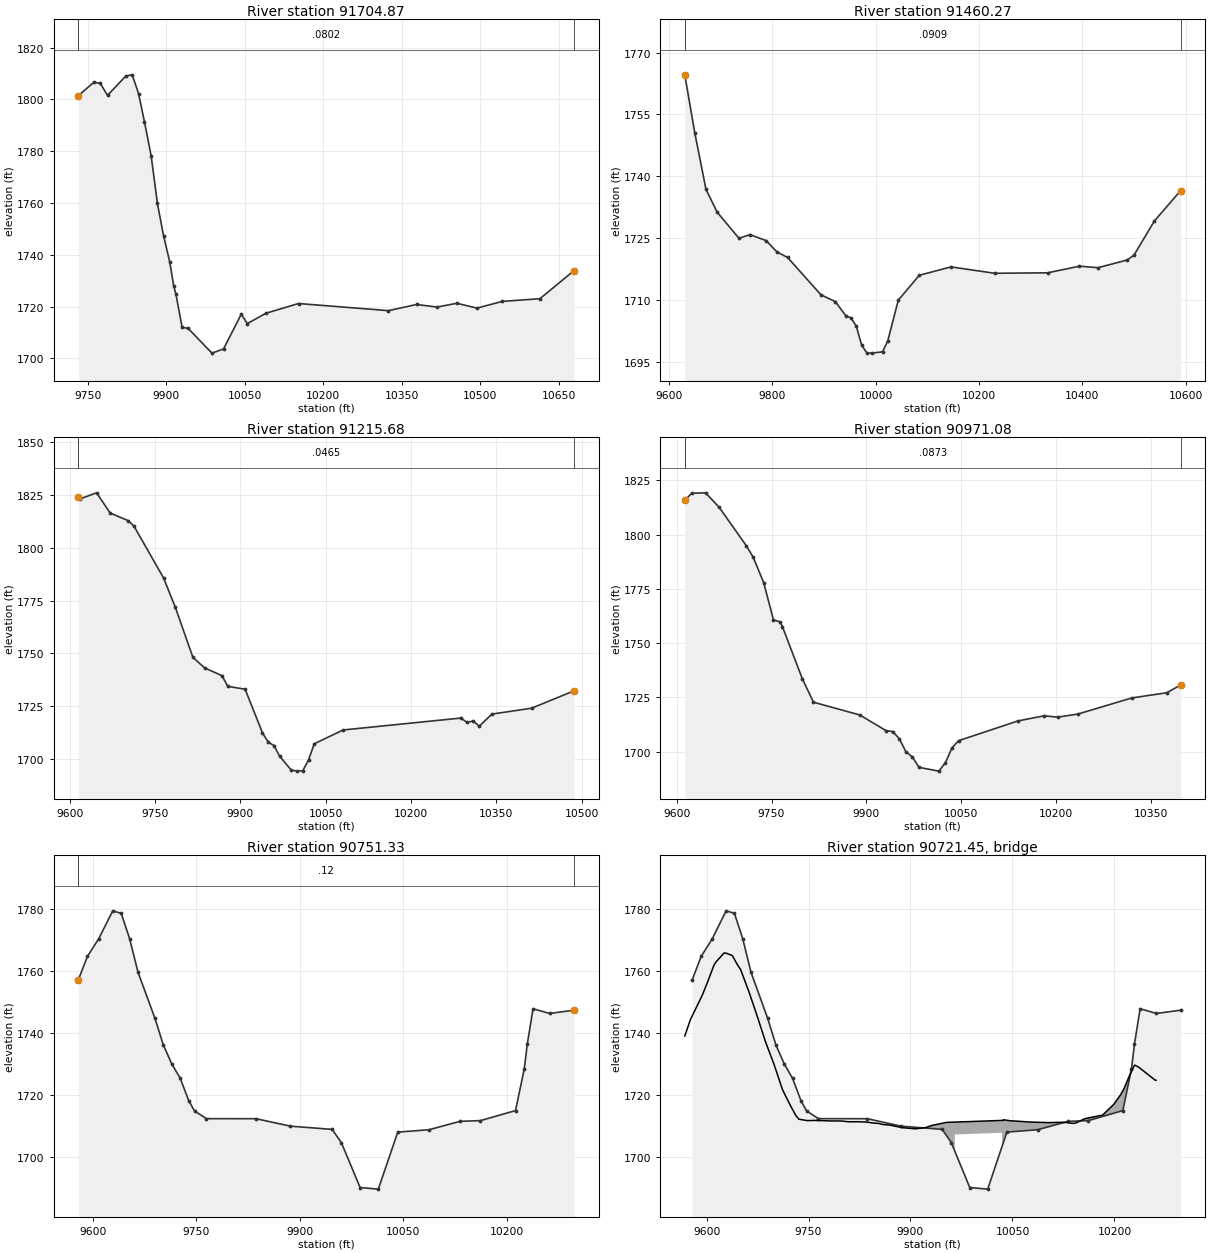
Type RM Length L Ch R = 1 ,91704.87,244.598100,244.598100,244.598100
XS GIS Cut Line= 6
535951.128130156784972.146341212536117.862619162785085.245794652
536259.892804457785164.111970098536345.662743864785231.710103842
536532.739646754785436.969816586536637.755634828785601.638628151
#Sta/Elev= 30
9732.3491801.4299761.8911806.5849774.2661806.1729788.1181801.553 9823.181809.045
9835.2851809.4859847.391 1802.229858.6991791.3069871.5211778.1249883.3221759.882
9895.1231747.3659906.9231737.2449914.6071727.8579918.7241724.8179930.5251711.989
9942.0761711.5519987.5031701.99410009.641703.599 10043.61717.04610055.141713.402
10090.721717.40110152.911721.15310324.671718.40110378.321720.78110417.591719.792
10455.421721.25210493.691719.37910542.251721.97610613.991723.018 10679.41733.905
#Mann= 3 , 0 , 0
9732.349  0.0802       09732.349  0.0802       0 10679.4  0.0802       0
#XS Ineff= 2 , 0
       0                               0
Bank Sta=9732.349,10679.4
Exp/Cntr=0.3,0.1

Type RM Length L Ch R = 1 ,91460.27,244.598200,244.598200,244.598200
XS GIS Cut Line= 6
 535767.10769291 785255.66585518 535938.06652934785315.940722058
536226.366543312785371.246744714 536362.26712438785413.922028115
536489.539657725785494.909847544536615.883434458785635.838795991
#Sta/Elev= 30
9630.9771764.5969650.3191750.4889671.9381736.8299693.4461731.301 9735.811724.935
9756.9921725.8419788.3141724.3839809.1031721.6419829.8431720.2939894.0951711.262
9922.1291709.5749942.5191706.1449952.6671705.5949962.796 1703.569972.9241699.083
9983.0531697.0999993.1811697.09110013.451697.41510023.591700.10310043.871709.934
10084.431715.972 10145.81718.00810230.181716.45910332.541716.571 10394.31718.183
10430.111717.815 10486.5 1719.6810499.681720.85110538.88  1729.110589.871736.518
#Mann= 3 , 0 , 0
9630.977  0.0909       09630.977  0.0909       010589.87  0.0909       0
#XS Ineff= 2 , 0
       09927.222                       0
Bank Sta=9630.977,10589.87
Exp/Cntr=0.3,0.1

Type RM Length L Ch R = 1 ,91215.68,244.598000,244.598000,244.598000
XS GIS Cut Line= 6
535712.368354806 785503.81752122535904.904315082785562.219359896
536224.080701904785619.529247252536328.380543048785647.168945793
536434.601252557785691.018953579536537.890455583785757.791453864
#Sta/Elev= 30
9615.2091824.3489618.6091823.3149647.3661826.131 9671.121816.5669702.5381812.989
 9713.01 1810.379764.9991785.8229785.6611771.9659816.6531748.1819837.1071743.186
9867.7881739.4899878.0151734.4099908.4841733.0619938.9041712.4339949.0431707.973
9959.1831706.3569969.3231701.2639989.6021694.718 9999.741694.23510009.861694.407
10019.981699.53710030.111707.20410080.761713.73910287.791719.38810298.431717.381
10309.341717.97610320.331715.54510342.311721.26210412.261724.06210487.031732.316
#Mann= 3 , 0 , 0
9615.209  0.0465       09615.209  0.0465       010487.03  0.0465       0
#XS Ineff= 2 , 0
       0                10273.33       0
Bank Sta=9615.209,10487.03
Exp/Cntr=0.3,0.1

Type RM Length L Ch R = 1 ,90971.08,219.748100,219.748100,219.748100
XS GIS Cut Line= 6
535664.893347689785708.134170563535793.636898099 785759.98464158
535867.668358994785784.888085928536228.106483751785892.338567964
536317.330114196785925.102288371536404.540626468785966.302095751
#Sta/Elev= 30
9612.781 1815.889623.7911818.995 9645.581819.2149667.3681812.4729710.261 1794.77
9720.9621789.6099737.6041777.8539753.045 1760.739763.5951759.7419767.3371757.561
9798.7011733.6069816.3481722.7879889.5271716.9219931.258 1709.699941.6911709.264
9952.1231706.0319962.5561700.0199972.9891697.5429983.4221692.76710014.721691.037
10025.161694.874 10035.61701.74410046.031705.05710139.961714.15310181.711716.529
10202.591715.88410234.481717.301 10320.21724.75110375.27 1727.1210397.381730.692
#Mann= 3 , 0 , 0
9612.781  0.0873       09612.781  0.0873       010397.38  0.0873       0
#XS Ineff= 2 , 0
       0                               0
Bank Sta=9612.781,10397.38
Exp/Cntr=0.3,0.1

Type RM Length L Ch R = 1 ,90751.33,67.596500,67.596500,67.596500
XS GIS Cut Line= 4
535634.212038577785798.090463325535937.597455263786011.632129997
536063.899538577786128.819629997 536201.92037192786236.892546639
#Sta/Elev= 30
9578.8261757.1839592.018 1764.789608.2041770.4179628.7041779.5219640.9331778.707
9653.1621770.5129665.3911759.6069689.8481744.7729702.0771736.0819714.3061729.999
9726.5341725.3289738.7631718.1759747.1941714.7919764.5681712.3079836.5931712.286
9886.1841709.8779946.652 1708.849959.9261704.5959987.2091690.03210013.591689.516
10041.771707.956 10087.11708.72710132.151711.44210161.621711.67410212.43 1714.91
10225.131728.40910229.471736.35610237.831747.85810261.91 1746.3310297.421747.385
#Mann= 3 , 0 , 0
9578.826    0.12       09578.826    0.12       010297.42    0.12       0
#XS Ineff= 2 , 0
       09925.968        10071.22       0
Bank Sta=9578.826,10297.42
Exp/Cntr=0.3,0.1

Type RM Length L Ch R = 3 ,90721.45,,,
BEGIN DESCRIPTION:
END DESCRIPTION:
Bridge Culvert--1,0,-1,-1, 0
Deck Dist Width WeirC Skew NumUp NumDn MinLoCord MaxHiCord MaxSubmerge Is_Ogee
25.268100,17.060300,2.6,0, 60, 60, , , 0.95, 0, 0,0,,
 9567.94 9576.19 9593.48 9601.06 9610.77 9613.31 9625.57 9628.06 9637.83 9645.36
 9650.09 9662.34 9674.60 9686.86 9699.12 9711.37 9714.52 9723.63 9731.82 9735.89
 9748.15 9760.40 9783.69 9797.18 9809.43 9821.69 9833.95 9846.21 9852.86 9858.46
 9870.72 9887.45 9907.49 9922.03 9932.01 9953.02 9965.22 9965.2210034.7810034.78
10036.8810037.0110046.0110077.1110103.1810122.8610129.6710138.1110142.9210156.16
10182.6610195.9010199.1110209.1510214.3510222.3910229.6010235.6410260.1010261.25
 1739.04 1744.33 1752.15 1756.27 1761.89 1762.85 1765.86 1765.87 1765.07 1762.09
 1760.52 1753.31 1745.38 1737.05 1729.94 1721.87 1720.40 1716.42 1713.14 1712.12
 1711.68 1711.74 1711.56 1711.57 1711.29 1711.32 1711.23 1710.87 1710.78 1710.45
 1710.19 1709.40 1709.02 1709.41 1710.15 1711.10 1711.19 1711.19 1711.74 1711.74
 1711.76 1711.95 1711.65 1711.20 1711.03 1711.13 1711.06 1710.78 1710.86 1712.28
 1713.47 1716.25 1716.96 1720.04 1722.09 1726.35 1729.63 1728.97 1724.74 1724.72
  739.04  744.33  752.15  756.27  761.89  762.85  765.86  765.87  765.07  762.09
  760.52  753.31  745.38  737.05  729.94  721.87  720.40  716.42  713.14  712.12
  711.68  711.74  711.56  711.57  711.29  711.32  711.23  710.87  710.78  710.45
  710.19  709.40  709.02  709.41  710.15  711.10  711.19 1707.19 1707.74  711.74
  711.76  711.95  711.65  711.20  711.03  711.13  711.06  710.78  710.86  712.28
  713.47  716.25  716.96  720.04  722.09  726.35  729.63  728.97  724.74  724.72
 9567.94 9576.19 9593.48 9601.06 9610.77 9613.31 9625.57 9628.06 9637.83 9645.36
 9650.09 9662.34 9674.60 9686.86 9699.12 9711.37 9714.52 9723.63 9731.82 9735.89
 9748.15 9760.40 9783.69 9797.18 9809.43 9821.69 9833.95 9846.21 9852.86 9858.46
 9870.72 9887.45 9907.49 9922.03 9932.01 9953.02 9965.22 9965.2210034.7810034.78
10036.8810037.0110046.0110077.1110103.1810122.8610129.6710138.1110142.9210156.16
10182.6610195.9010199.1110209.1510214.3510222.3910229.6010235.6410260.1010261.25
 1739.04 1744.33 1752.15 1756.27 1761.89 1762.85 1765.86 1765.87 1765.07 1762.09
 1760.52 1753.31 1745.38 1737.05 1729.94 1721.87 1720.40 1716.42 1713.14 1712.12
 1711.68 1711.74 1711.56 1711.57 1711.29 1711.32 1711.23 1710.87 1710.78 1710.45
 1710.19 1709.40 1709.02 1709.41 1710.15 1711.10 1711.19 1711.19 1711.74 1711.74
 1711.76 1711.95 1711.65 1711.20 1711.03 1711.13 1711.06 1710.78 1710.86 1712.28
 1713.47 1716.25 1716.96 1720.04 1722.09 1726.35 1729.63 1728.97 1724.74 1724.72
  739.04  744.33  752.15  756.27  761.89  762.85  765.86  765.87  765.07  762.09
  760.52  753.31  745.38  737.05  729.94  721.87  720.40  716.42  713.14  712.12
  711.68  711.74  711.56  711.57  711.29  711.32  711.23  710.87  710.78  710.45
  710.19  709.40  709.02  709.41  710.15  711.10  711.19 1707.19 1707.74  711.74
  711.76  711.95  711.65  711.20  711.03  711.13  711.06  710.78  710.86  712.28
  713.47  716.25  716.96  720.04  722.09  726.35  729.63  728.97  724.74  724.72
BR Coef=-1 , 0 , 0 ,, 0 ,,,0.8,0,1,0,
WSPro=,,,, 1 ,,,, 0 ,,,, 0 ,,,,-1 ,-1 ,-1 , 0 , 0 , 0 , 0 , 0
BC Design=,, 0 ,, 0 ,,,,,,

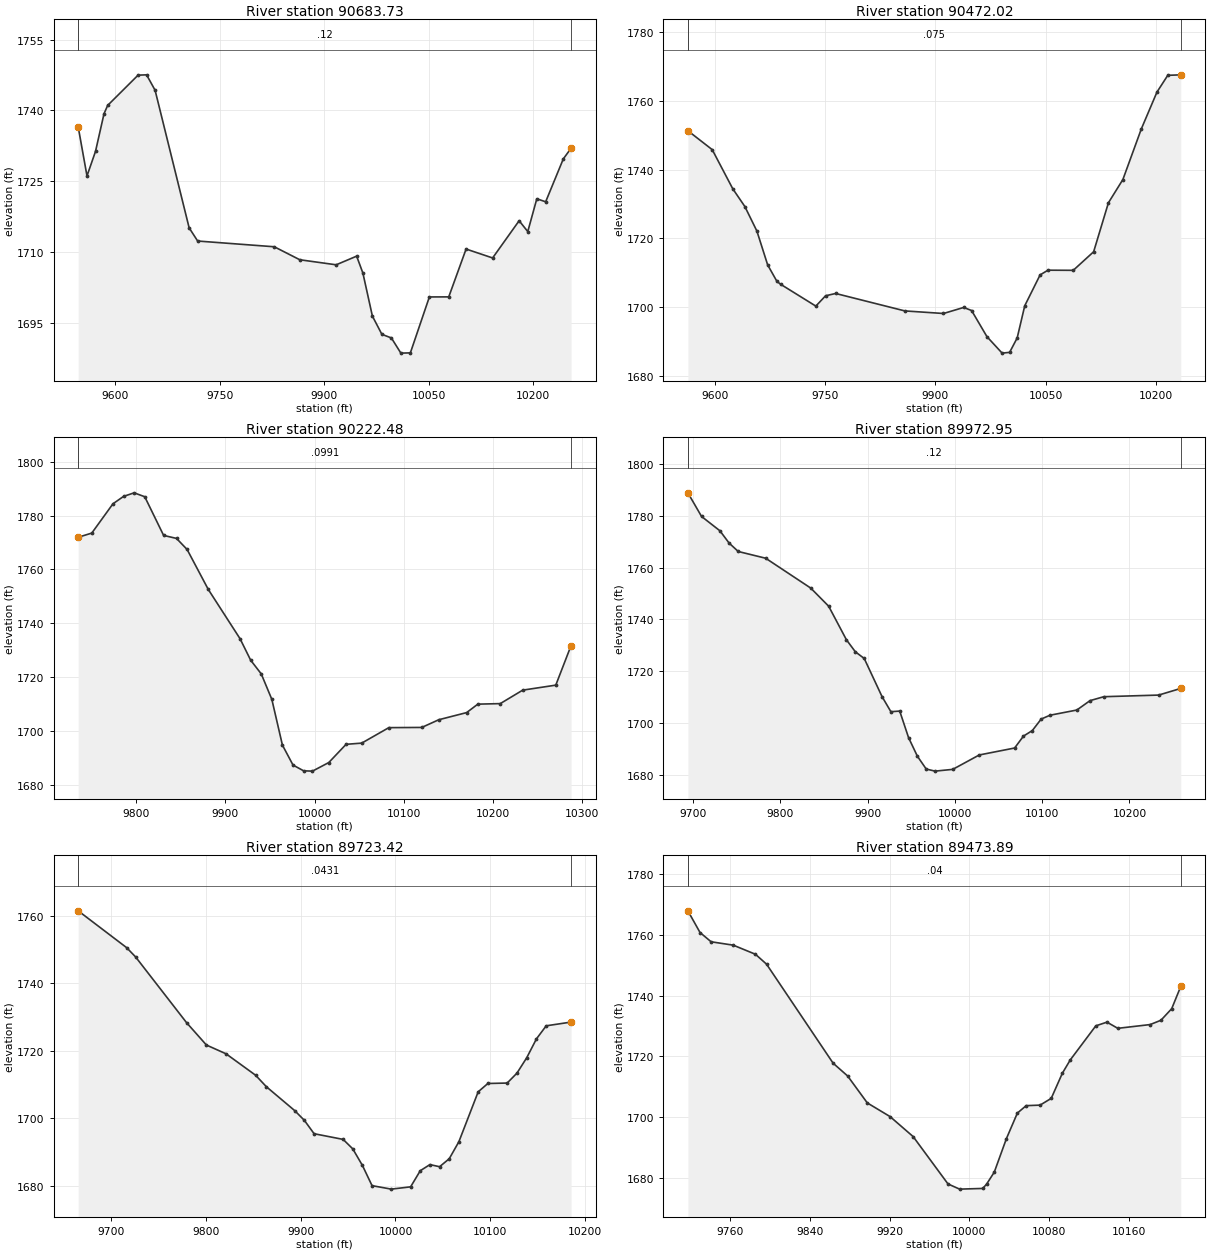
Type RM Length L Ch R = 1 ,90683.73,211.718400,211.718400,211.718400
XS GIS Cut Line= 4
535594.652260381785840.614195983 535889.42037193 786048.09046333
536015.722455243 786165.27796333536153.743288586786273.350879972
#Sta/Elev= 30
9546.7551736.5339559.4091726.1259571.6381731.3279583.8671739.3089589.1231741.073
9632.782 1747.489645.011 1747.559657.2391744.2799706.1541715.1219718.3831712.332
9828.4421711.1149865.1281708.3629917.3791707.2949946.7831709.1279955.7561705.536
9969.3971696.4259983.0381692.558 9996.681691.79310010.321688.57710023.961688.633
10051.251700.482 10079.11700.496   101041710.634 10142.11708.744 10180.21716.632
10192.611714.332 10205.61721.28610218.311720.64610243.711729.75310254.811731.985
#Mann= 3 , 0 , 0
9546.755    0.12       09546.755    0.12       010254.81    0.12       0
#XS Ineff= 2 , 0
       09900.653        10064.45       0
Bank Sta=9546.755,10254.81
Exp/Cntr=0.3,0.1

Type RM Length L Ch R = 1 ,90472.02,249.531500,249.531500,249.531500
XS GIS Cut Line= 6
535547.794822353785928.990882898535699.543530647786049.174997182
535768.148284181786125.676204033535810.510826873 786205.70308195
535851.199388661786337.101278444535937.288636388786454.875451803
#Sta/Elev= 30
9562.514 1751.37 9595.691745.8629623.7441734.4479640.1661729.3019656.5871722.146
9671.2751712.2849683.8821707.4969689.1231706.6279736.9311700.2949750.2131703.307
9763.9541703.9719858.2821698.8929910.9321698.1459938.421  1699.99949.2181699.013
9970.1541691.3989990.8411686.59910001.061686.82410011.371691.01910021.681700.394
10042.611709.38210053.351710.756 10087.81710.717 10115.61716.12910135.741730.392
10155.461737.16810180.671751.95410201.911762.63510216.62 1767.5110234.351767.657
#Mann= 3 , 0 , 0
9562.514   0.075       09562.514   0.075       010234.35   0.075       0
#XS Ineff= 2 , 0
       09837.378                       0
Bank Sta=9562.514,10234.35
Exp/Cntr=0.3,0.1

Type RM Length L Ch R = 1 ,90222.48,249.531500,249.531500,249.531500
XS GIS Cut Line= 6
 535392.14549163 786223.33692552535614.512524728 786365.73466428
535676.477179612 786405.78652089535712.151296681786431.247117497
535816.223491119786510.557834425535848.994686749786533.717974081
#Sta/Elev= 30
9734.947 1771.969750.2111773.519 9773.961784.4059785.8351787.147 9797.711788.471
9809.5841787.0179830.7471772.6489845.2081771.5359857.0831767.4239880.8321752.571
9916.4561734.2669928.3311726.3059940.2061721.207 9952.081711.7419963.9551694.741
 9975.831687.3439987.7041685.2049997.6381685.08810015.951688.28110035.341695.049
10052.871695.49310083.261701.24210120.191701.319 10139.31704.18510170.481706.831
10183.061709.971 10208.21710.16910233.351715.17110270.45 1717.0310287.591731.736
#Mann= 3 , 0 , 0
9734.947  0.0991       09734.947  0.0991       010287.59  0.0991       0
#XS Ineff= 2 , 0
       0                               0
Bank Sta=9734.947,10287.59
Exp/Cntr=0.3,0.1

Type RM Length L Ch R = 1 ,89972.95,249.531500,249.531500,249.531500
XS GIS Cut Line= 6
535250.266691777786534.119058547535327.741528109786559.821625928
535396.230684147786577.475075261535652.126116122786621.336565939
535748.840179187786645.467354419535798.991820875786662.710874464
#Sta/Elev= 30
9694.0791788.8829709.735 1779.769730.768 1774.239741.2851769.4919751.8021766.231
9783.2141763.6299834.8481752.1079855.384 1745.119875.769 1732.139885.9621727.505
9896.1551724.922 9916.54 1710.219926.6881704.3759936.8121704.6219946.9351694.372
9957.0591687.1839967.1821682.2379977.3061681.4349997.5531682.10910027.951687.673
10068.48 1690.3610078.621694.96210088.751697.09110098.88 1701.5310109.051703.019
10139.771705.02410154.891708.656 10170.71710.16910233.481710.79510258.85 1713.36
#Mann= 3 , 0 , 0
9694.079    0.12       09694.079    0.12       010258.85    0.12       0
#XS Ineff= 2 , 0
       0                               0
Bank Sta=9694.079,10258.85
Exp/Cntr=0.3,0.1

Type RM Length L Ch R = 1 ,89723.42,249.531500,249.531500,249.531500
XS GIS Cut Line= 6
535207.106931221786764.208640567535328.854557404 786806.44868889
535403.693721839786827.127052118535464.107790247786840.675918902
 535642.49110769786874.399709391  535710.4696969786891.072295722
#Sta/Elev= 30
 9665.27 1761.559716.3961750.625  9725.8 1747.899779.5861728.3879800.5521721.747
9821.3021719.1389852.426 1712.799863.8331709.3739893.6551702.3039903.9041699.401
9914.152 1695.449944.8051693.7549954.9681690.9469965.1311686.0359975.2951680.035
9995.6211679.00410015.991679.68210026.171684.46410036.36 1686.2810046.541685.652
10056.731688.01410066.911693.06910087.281707.87210097.471710.33410117.861710.468
10128.161713.40310138.461717.96110148.751723.57510159.051727.44610185.271728.551
#Mann= 3 , 0 , 0
 9665.27  0.0431       0 9665.27  0.0431       010185.27  0.0431       0
#XS Ineff= 2 , 0
       0                               0
Bank Sta=9665.27,10185.27
Exp/Cntr=0.3,0.1

Type RM Length L Ch R = 1 ,89473.89,249.531500,249.531500,249.531500
XS GIS Cut Line= 6
535174.028246374786944.020978702535301.291462599787005.896954331
 535360.88679965787038.869220808535475.464303519787106.646991424
535547.389092193787142.695477334535613.562272986787169.463381222
#Sta/Elev= 30
9717.5891767.9399729.789 1760.799740.9081757.7439763.1471756.6279785.3861753.634
9796.5051750.3799863.3361717.7539877.9011713.5449897.6211704.6759920.478 1700.17
 9943.651693.5779978.6061677.9869990.2571676.28110013.491676.50610017.371677.944
10025.061681.88810037.221692.91710048.221701.32810057.061703.774   100711703.946
10082.181706.16810093.371714.45810101.291718.83610126.931730.06110138.111731.276
10149.01 1729.2410181.45 1730.4810192.261731.89210203.081735.70810212.181743.052
#Mann= 3 , 0 , 0
9717.589    0.04       09717.589    0.04       010212.18    0.04       0
#XS Ineff= 2 , 0
       0                               0
Bank Sta=9717.589,10212.18
Exp/Cntr=0.3,0.1

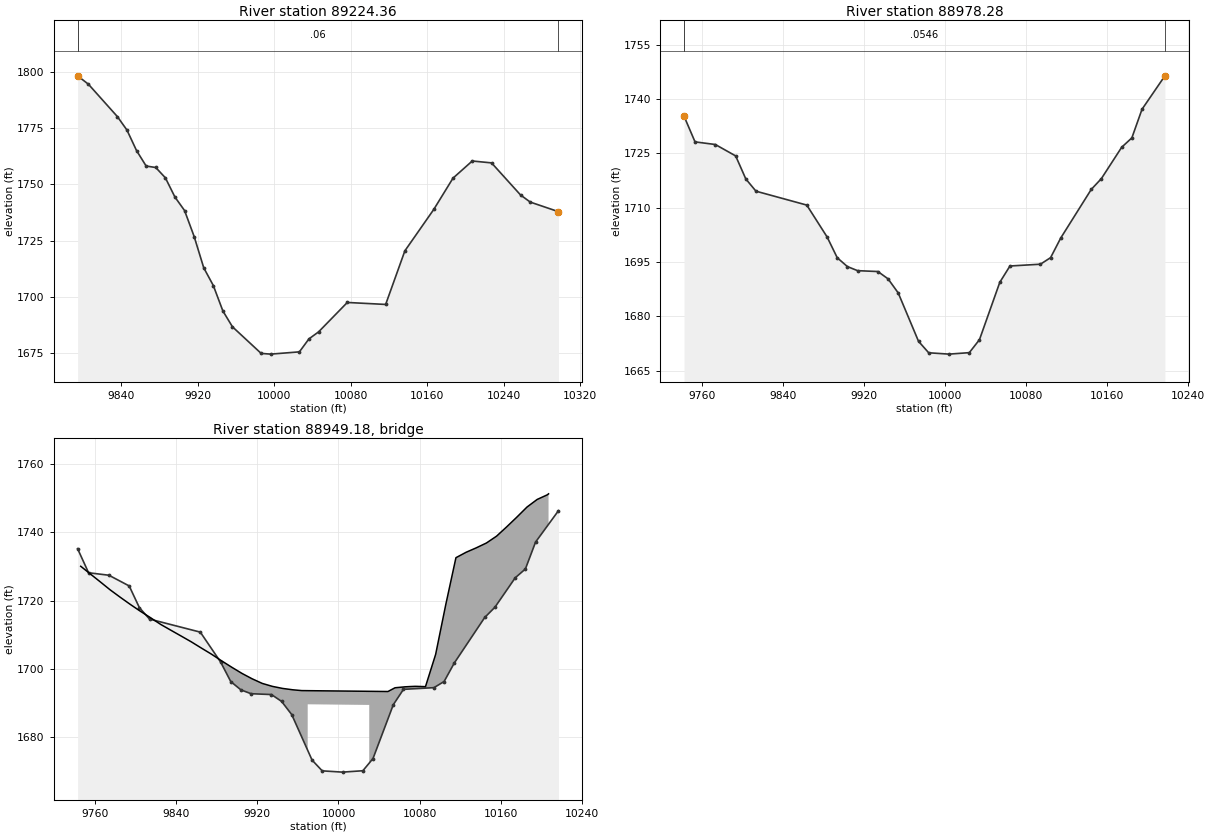
Type RM Length L Ch R = 1 ,89224.36,246.079100,246.079100,246.079100
XS GIS Cut Line= 6
535113.814785573787282.552200222535240.560101387  787296.1705872
535356.632080167787299.568929364535435.201003515787305.310887581
535535.674760237787316.770635339535614.161639115787328.894769458
#Sta/Elev= 30
 9794.191798.3759805.532 1794.639835.7721780.2359845.8161774.2299855.861 1765.08
9865.9061758.197 9875.951757.5489885.9951752.9639896.0391744.3699906.084 1738.38
9916.1291726.7939926.1561712.8649936.1621704.9819946.167 1693.659956.1731686.601
9986.1911674.7529996.1961674.429 10026.21675.44110036.211681.23210046.231684.321
10076.31 1697.4410116.421696.55910136.541720.44410166.741738.86710186.871752.806
   102071760.44310227.181759.60110257.531745.30410267.651742.14710297.161737.877
#Mann= 3 , 0 , 0
 9794.19    0.06       0 9794.19    0.06       010297.16    0.06       0
#XS Ineff= 2 , 0
       0                               0
Bank Sta=9794.19,10297.16
Exp/Cntr=0.3,0.1

Type RM Length L Ch R = 1 ,88978.28,57.396400,57.396400,57.396400
XS GIS Cut Line= 2
535124.192625839 787551.07881703535597.540711343787522.013583735
#Sta/Elev= 30
9742.7131735.231 9753.541728.1569773.578 1727.439793.6161724.2859803.6351717.928
9813.6531714.5589863.7481710.7249883.7851701.9369893.8041696.1989903.8231693.763
9913.8421692.6429933.8791692.3999943.8981690.3879953.9171686.5059973.955 1673.16
9983.9741669.99710004.011669.62310024.05 1670.0310034.071673.61410054.111689.429
10064.121693.92610094.181694.422 10104.21696.22910114.221701.65210144.271715.035
10154.291718.02810174.331726.67810184.35 1729.2610194.371737.15210216.951746.371
#Mann= 3 , 0 , 0
9742.713  0.0546       09742.713  0.0546       010216.95  0.0546       0
#XS Ineff= 2 , 0
       0                               0
Bank Sta=9742.713,10216.95
Exp/Cntr=0.3,0.1

Type RM Length L Ch R = 3 ,88949.18,,,
BEGIN DESCRIPTION:
END DESCRIPTION:
Bridge Culvert--1,0,-1,-1, 0
Deck Dist Width WeirC Skew NumUp NumDn MinLoCord MaxHiCord MaxSubmerge Is_Ogee
16.887200,23.622000,2.6,0, 48, 48, , , 0.95, 0, 0,0,,
 9745.82 9754.67 9764.68 9774.69 9784.70 9794.71 9804.72 9813.24 9814.73 9824.74
 9834.74 9844.75 9854.76 9864.77 9874.78 9884.79 9894.80 9904.81 9914.82 9924.83
 9934.84 9944.85 9954.86 9963.74 9963.83 9969.65 9969.6510030.3510030.3510048.80
10055.7810065.7910070.2910075.8010085.8110095.8310105.8410115.8510125.8610135.87
10145.8910155.9010165.9110175.9210185.9310195.9510205.9610207.19
 1730.06 1727.95 1725.58 1723.17 1720.98 1718.86 1716.84 1715.23 1714.94 1712.98
 1711.28 1709.59 1707.89 1706.05 1704.25 1702.29 1700.41 1698.61 1697.03 1695.67
 1694.80 1694.20 1693.80 1693.56 1693.56 1693.54 1693.54 1693.35 1693.35 1693.29
 1694.39 1694.67 1694.74 1694.81 1694.72 1704.19 1718.84 1732.58 1734.17 1735.47
 1736.89 1738.90 1741.64 1744.49 1747.45 1749.68 1751.04 1751.33
  730.06  727.95  725.58  723.17  720.98  718.86  716.84  715.23  714.94  712.98
  711.28  709.59  707.89  706.05  704.25  702.29  700.41  698.61  697.03  695.67
  694.80  694.20  693.80  693.56  693.56  693.54 1689.54 1689.35  693.35  693.29
  694.39  694.67  694.74  694.81  694.72  704.19  718.84  732.58  734.17  735.47
  736.89  738.90  741.64  744.49  747.45  749.68  751.04  751.33
 9745.82 9754.67 9764.68 9774.69 9784.70 9794.71 9804.72 9813.24 9814.73 9824.74
 9834.74 9844.75 9854.76 9864.77 9874.78 9884.79 9894.80 9904.81 9914.82 9924.83
 9934.84 9944.85 9954.86 9963.74 9963.83 9969.65 9969.6510030.3510030.3510048.80
10055.7810065.7910070.2910075.8010085.8110095.8310105.8410115.8510125.8610135.87
10145.8910155.9010165.9110175.9210185.9310195.9510205.9610207.19
 1730.06 1727.95 1725.58 1723.17 1720.98 1718.86 1716.84 1715.23 1714.94 1712.98
 1711.28 1709.59 1707.89 1706.05 1704.25 1702.29 1700.41 1698.61 1697.03 1695.67
 1694.80 1694.20 1693.80 1693.56 1693.56 1693.54 1693.54 1693.35 1693.35 1693.29
 1694.39 1694.67 1694.74 1694.81 1694.72 1704.19 1718.84 1732.58 1734.17 1735.47
 1736.89 1738.90 1741.64 1744.49 1747.45 1749.68 1751.04 1751.33
  730.06  727.95  725.58  723.17  720.98  718.86  716.84  715.23  714.94  712.98
  711.28  709.59  707.89  706.05  704.25  702.29  700.41  698.61  697.03  695.67
  694.80  694.20  693.80  693.56  693.56  693.54 1689.54 1689.35  693.35  693.29
  694.39  694.67  694.74  694.81  694.72  704.19  718.84  732.58  734.17  735.47
  736.89  738.90  741.64  744.49  747.45  749.68  751.04  751.33
BR Coef=-1 , 0 , 0 ,, 0 ,,,0.8,0,1,0,
WSPro=,,,, 1 ,,,, 0 ,,,, 0 ,,,,-1 ,-1 ,-1 , 0 , 0 , 0 , 0 , 0
BC Design=,, 0 ,, 0 ,,,,,,