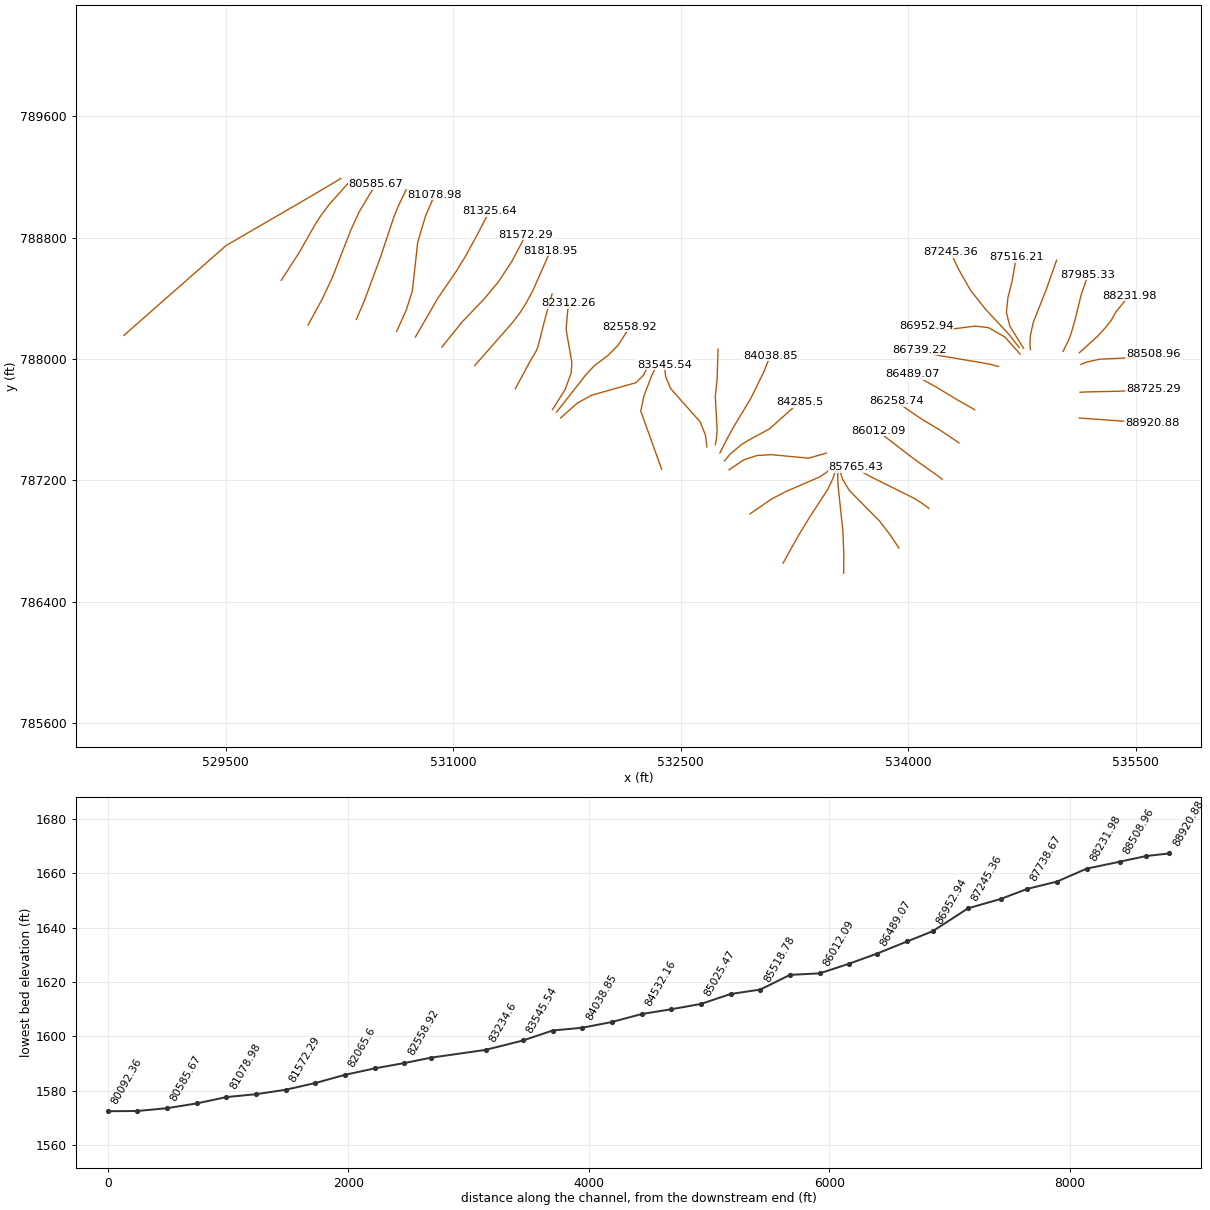
HEC-RAS study 5238_ras.prj: 5238

--- 5238_ras.g01 (geometry) --- (continued)

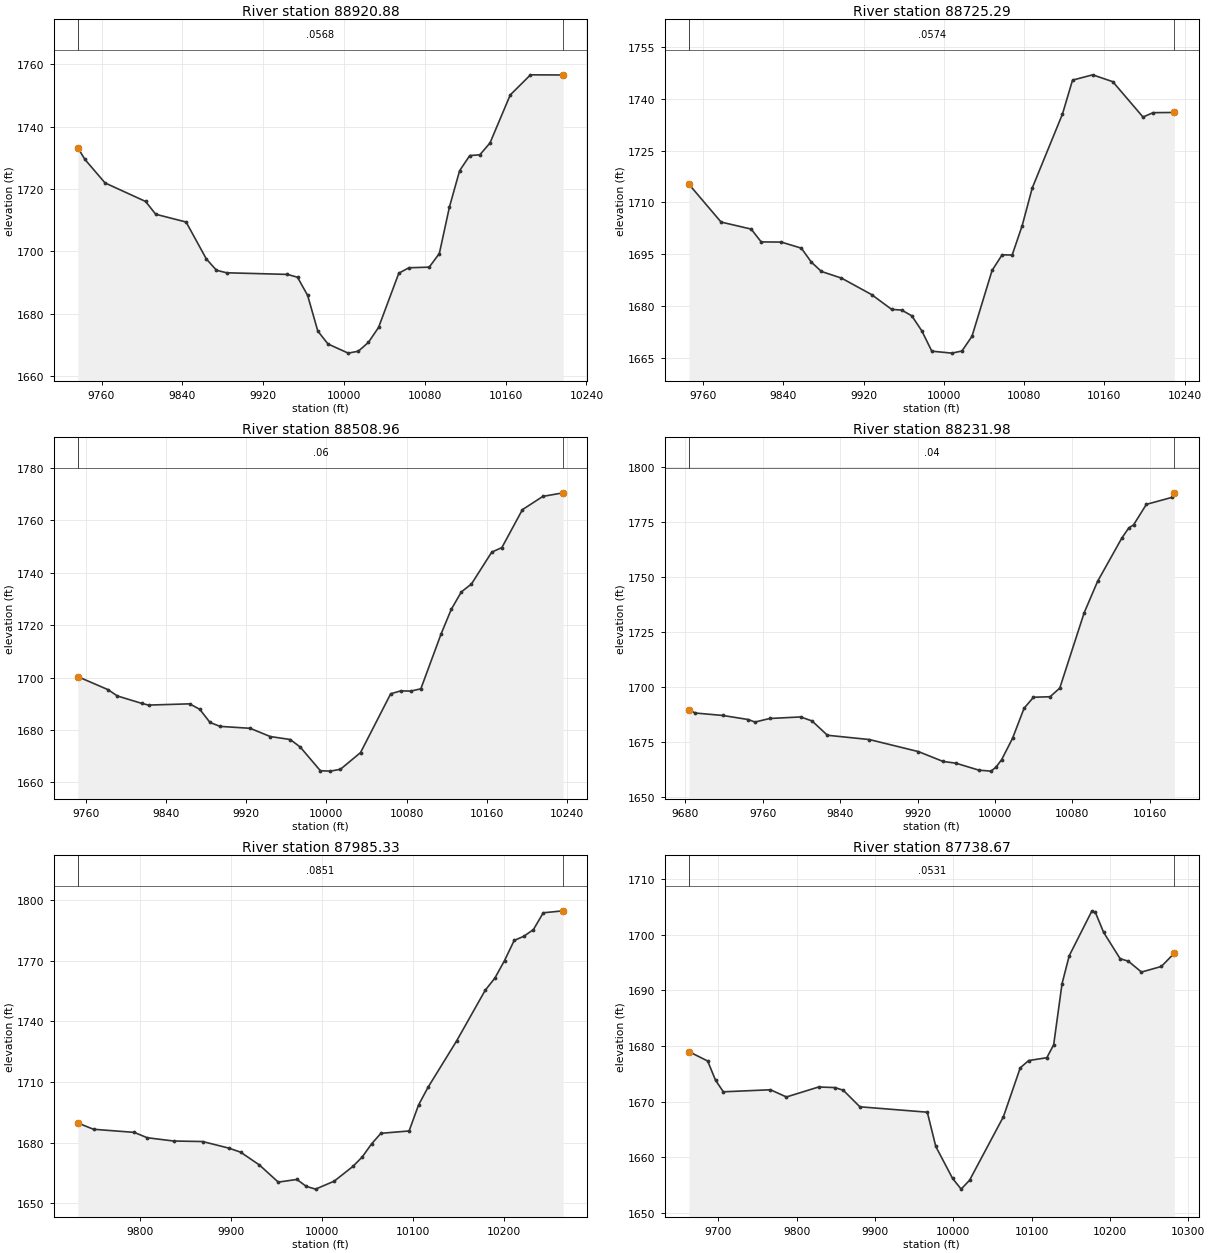
Type RM Length L Ch R = 1 ,88920.88,195.587500,195.587500,195.587500
XS GIS Cut Line= 2
535128.096266896787610.208028153535607.262933582787575.485805944
#Sta/Elev= 30
9736.4981733.243 9743.42  1729.59763.4721721.9139803.5771715.9799813.6031711.878
9843.6821709.3849863.7351697.5389873.7611693.9179883.787 1693.119943.9441692.589
9953.9711691.6829963.9971685.8389974.0231674.4449984.0491670.307 10004.1 1667.35
10014.131667.96110024.151670.79710034.181675.58910054.231692.98610064.261694.723
10084.311694.91210094.34 1699.2810104.361714.22710114.391725.82410124.421730.681
10134.441730.94310144.471734.71910164.521750.12710184.571756.57510216.921756.522
#Mann= 3 , 0 , 0
9736.498  0.0568       09736.498  0.0568       010216.92  0.0568       0
#XS Ineff= 2 , 0
       0                               0
Bank Sta=9736.498,10216.92
Exp/Cntr=0.3,0.1

Type RM Length L Ch R = 1 ,88725.29,216.336400,216.336400,216.336400
XS GIS Cut Line= 6
535133.037096273787779.929489362535181.196062748787782.267813538
 535387.97706106787786.719200188535472.095436146787791.211027622
535586.828504711787800.561183271 535615.94966549787804.509786807
#Sta/Elev= 30
9745.9481715.2469777.9491704.314 9807.971702.2769817.9711698.5659837.9751698.519
9857.9781696.7559867.9791692.7049877.9811690.0139897.9841688.0899927.9891683.323
9947.9921679.0419957.9931678.8329967.9961677.1929978.0041672.8529988.0121666.939
10008.031666.37510018.051666.98810028.061671.23710048.091690.314 10058.11694.832
10068.12 1694.7710078.131703.31310088.151714.19410118.251735.57510128.291745.391
10148.351746.92610168.42 1744.9410198.521734.713 10208.61735.97410229.741736.031
#Mann= 3 , 0 , 0
9745.948  0.0574       09745.948  0.0574       010229.74  0.0574       0
#XS Ineff= 2 , 0
       0                               0
Bank Sta=9745.948,10229.74
Exp/Cntr=0.3,0.1

Type RM Length L Ch R = 1 ,88508.96,276.973900,276.973900,276.973900
XS GIS Cut Line= 6
535138.519457252787963.693325643535175.051344189787978.451316129
535261.861935214787998.183686333535476.007225367788007.881129059
535550.452754547788018.116622229535614.748347863 788031.83430134
#Sta/Elev= 30
9752.1261700.3819782.3121695.3989791.526 1693.019815.845 1690.179822.6241689.513
 9863.621689.9969873.7461687.893 9883.841682.9159893.863 1681.399923.9341680.654
9943.9531677.5169963.9561676.3739973.9581673.4669993.9611664.45310003.961664.304
10013.971665.01810033.981671.37810064.041693.82810074.061694.93810084.081694.863
10094.111695.73310114.291716.66910124.381726.03310134.481732.72910144.571735.748
10164.761747.89710174.911749.66310195.35 1764.12 10215.81769.20510236.011770.555
#Mann= 3 , 0 , 0
9752.126    0.06       09752.126    0.06       010236.01    0.06       0
#XS Ineff= 2 , 0
       0                               0
Bank Sta=9752.126,10236.01
Exp/Cntr=0.3,0.1

Type RM Length L Ch R = 1 ,88231.98,246.655200,246.655200,246.655200
XS GIS Cut Line= 6
535128.252009212788040.716221182535248.293410057788148.760968912
535303.229756839788209.756769997535337.969832936788253.866621495
535369.132349713788309.459557827535455.771109654788416.864922544
#Sta/Elev= 30
9683.6151689.5079690.3441688.138 9718.651687.0339745.061 1685.189751.8131684.036
9767.1241685.6599799.0651686.3679810.8491684.542 9826.77 1678.049870.1491676.093
9920.8721670.6089946.2971666.1399959.4061665.3649983.4211662.1729995.908 1661.74
   100011663.53510006.921667.00410018.111676.64710030.051690.31310039.73 1695.31
10056.911695.55310066.931699.46410092.19 1733.7410106.021747.95510131.191767.738
10138.271772.25710143.241773.65410156.451782.96110182.881786.13910185.351788.209
#Mann= 3 , 0 , 0
9683.615    0.04       09683.615    0.04       010185.35    0.04       0
#XS Ineff= 2 , 0
       0                               0
Bank Sta=9683.615,10185.35
Exp/Cntr=0.3,0.1

Type RM Length L Ch R = 1 ,87985.33,246.655200,246.655200,246.655200
XS GIS Cut Line= 6
535020.846149718788049.780756531535057.077731929788122.492291733
535073.473330952788165.794046143535100.808477104788261.308284658
535141.152911319788426.103411759 535186.60292667 788555.41961612
#Sta/Elev= 30
9731.5181689.6759748.803 1686.579793.5731685.0379807.7961682.3939836.8681680.765
 9868.751680.507 9897.661677.2479910.5741675.2469931.2621668.9079951.9511660.448
9972.4881661.7579982.7221658.3519992.9561656.97410013.471660.90710034.011668.194
10044.271672.85410054.541679.32510064.811684.56410095.851685.73810106.251698.585
10116.651707.30710148.071730.23210179.621755.35710190.141761.28610200.791769.968
10211.451779.968 10222.11782.00910232.611785.32910243.411793.618 10265.31794.582
#Mann= 3 , 0 , 0
9731.518  0.0851       09731.518  0.0851       0 10265.3  0.0851       0
#XS Ineff= 2 , 0
       0                               0
Bank Sta=9731.518,10265.3
Exp/Cntr=0.3,0.1

Type RM Length L Ch R = 1 ,87738.67,222.468000,222.468000,222.468000
XS GIS Cut Line= 6
 534805.73172224 788061.22301328534802.478294288788097.932549275
 534804.52952685788149.907437038534824.833932067788241.499110533
534909.807934974788456.123775633 534978.25729472788650.663333583
#Sta/Elev= 30
9662.2811679.0029686.1831677.3289696.2111673.8749706.2241671.7899766.4091672.157
9786.773 1670.869827.9451672.656 9848.821672.5489859.4131672.0729880.5971669.095
9966.7541668.1249977.5571661.968    99991656.22710009.971654.29610020.771655.906
10063.981667.32110085.47  1676.110096.151677.40310119.45 1677.9210128.171680.248
10138.841691.21910148.051696.25510177.051704.31810181.431704.03610191.971700.445
10213.051695.71410223.591695.26110240.321693.31310265.751694.31910282.261696.715
#Mann= 3 , 0 , 0
9662.281  0.0531       09662.281  0.0531       010282.26  0.0531       0
#XS Ineff= 2 , 0
       0                               0
Bank Sta=9662.281,10282.26
Exp/Cntr=0.3,0.1

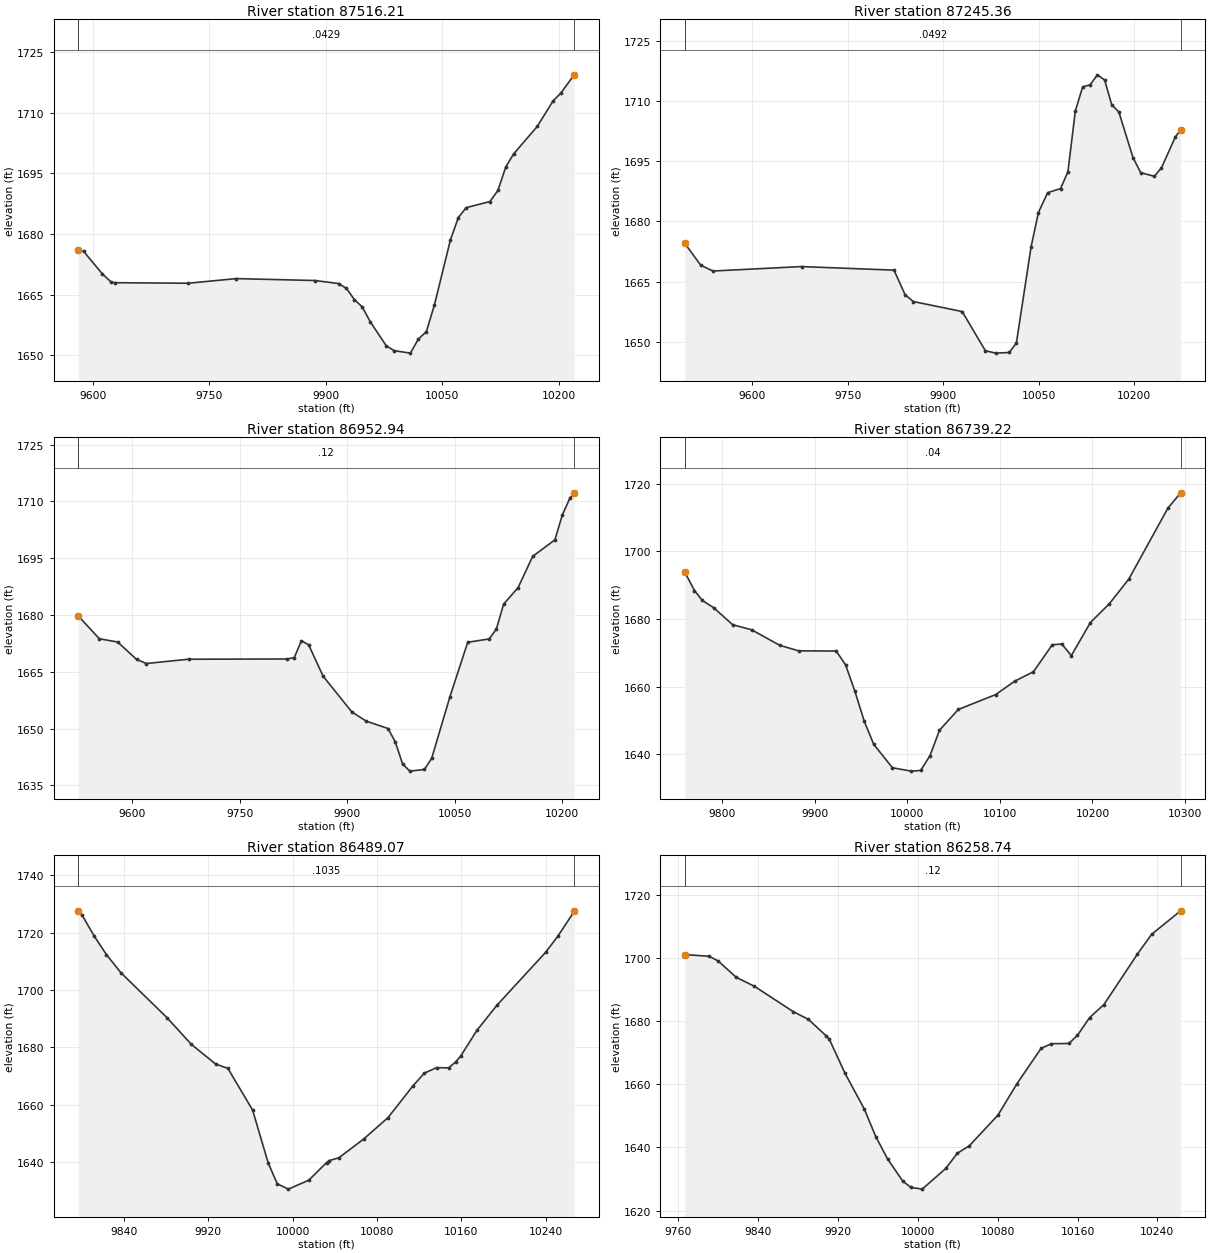
Type RM Length L Ch R = 1 ,87516.21,270.842400,270.842400,270.842400
XS GIS Cut Line= 6
534760.397979798788069.409132139534670.406125706 788215.60233929
534647.097573174788306.011695881534657.402949141788405.141103941
534684.097742881788509.111962639534712.333556693 788671.92132668
#Sta/Elev= 30
9581.6711676.0949588.3311675.7789612.1521670.2619624.0631668.1159628.4231667.989
    97231667.8569784.9561669.0019886.3581668.5279916.6561667.783  9926.81666.569
9936.9441663.8289947.0871662.0149957.4081658.3299978.056 1652.37 9988.38 1651.18
10009.041650.57510019.36 1654.0510029.681655.91310040.011662.49710060.571678.552
10070.761684.09910080.951686.54910111.52 1688.0610121.711690.789 10131.9 1696.63
10142.091699.86610172.421706.64410192.641712.91510202.75 1714.8810219.861719.388
#Mann= 3 , 0 , 0
9581.671  0.0429       09581.671  0.0429       010219.86  0.0429       0
#XS Ineff= 2 , 0
       0                               0
Bank Sta=9581.671,10219.86
Exp/Cntr=0.3,0.1

Type RM Length L Ch R = 1 ,87245.36,292.421300,292.421300,292.421300
XS GIS Cut Line= 6
534731.281920287788074.748368361534666.709155205788158.776497193
534510.148121107788327.044549971534411.376901877788451.088088692
534333.463077368 788588.37809384534278.626214453788702.702624761
#Sta/Elev= 30
9493.8951674.5239518.7531669.1049537.9591667.6219677.4411668.734 9822.711667.842
9840.0861661.7029853.0671660.0089929.8721657.5129966.1961647.7449982.4491647.139
10003.831647.29610015.011649.68510038.041673.63110049.631682.22110064.091687.163
 10084.4  1688.210095.991692.37810107.581707.52910119.171713.57710130.761714.069
10142.341716.57110153.651715.27310164.811709.09710175.961707.32610198.281695.905
10210.421692.16210231.751691.25610242.911693.34110264.731701.05510273.091702.871
#Mann= 3 , 0 , 0
9493.895  0.0492       09493.895  0.0492       010273.09  0.0492       0
#XS Ineff= 2 , 0
       0                               0
Bank Sta=9493.895,10273.09
Exp/Cntr=0.3,0.1

Type RM Length L Ch R = 1 ,86952.94,213.721200,213.721200,213.721200
XS GIS Cut Line= 6
 534737.56403417788031.802436618534636.815274432788144.562498705
534529.105939002788206.152610548534440.815169707788216.416721612
534251.293022436788191.961179917534119.311548928788215.797036623
#Sta/Elev= 30
9525.0251679.7299554.2811673.722    95801672.847 9606.251668.2549619.9831667.179
9678.8511668.3089816.0621668.3729826.2441668.7269836.3481673.2029846.453 1672.08
9866.522 1663.849906.5671654.398 9926.611651.9599957.0871650.006 9967.251646.464
9977.4121640.6419987.5751638.746 10007.9 1639.1810018.02 1642.1210043.231658.232
10068.311672.78310098.361673.67410108.371676.32610118.421682.867 10138.61687.227
10158.941695.47910189.891699.83210200.321706.40210210.751710.81210216.821712.269
#Mann= 3 , 0 , 0
9525.025    0.12       09525.025    0.12       010216.82    0.12       0
#XS Ineff= 2 , 0
       0                               0
Bank Sta=9525.025,10216.82
Exp/Cntr=0.3,0.1

Type RM Length L Ch R = 1 ,86739.22,250.150700,250.150700,250.150700
XS GIS Cut Line= 6
534595.091579493787950.222824098534547.162610173787962.673212347
534489.237238908 787973.89666694534210.392675692788020.986733609
534144.301996884788036.837671294534072.084966386788060.950051137
#Sta/Elev= 30
9759.799 1693.879770.2261688.414  9778.81685.469 9790.891683.3429811.5221678.288
9831.894  1676.89862.4521672.189 9882.751670.5589923.2861670.509 9933.421666.425
9943.5541658.5329953.688 1649.659963.8231642.8749984.0911635.94210004.371634.954
10014.521635.14810024.671639.57810034.811647.04210055.111653.206 10095.71657.632
10115.921661.55510136.291664.37610156.661672.35910166.951672.57810177.231669.146
 10197.81678.94610218.361684.52410239.371691.84110281.411712.76910295.241717.337
#Mann= 3 , 0 , 0
9759.799    0.04       09759.799    0.04       010295.24    0.04       0
#XS Ineff= 2 , 0
       0                               0
Bank Sta=9759.799,10295.24
Exp/Cntr=0.3,0.1

Type RM Length L Ch R = 1 ,86489.07,230.327500,230.327500,230.327500
XS GIS Cut Line= 6
 534438.15996242787664.941510911534323.214458808787730.172839341
534267.437270954 787764.05015704534265.792886572787765.188576999
534191.326121297787809.904829417534031.407660484787900.294742359
#Sta/Elev= 30
9796.8761727.6649800.5091726.1229812.0071718.7869823.5051712.3889837.5161705.934
9880.9951690.3429903.9911681.0479926.9881674.1799938.6521672.6519962.0521658.103
9976.8661639.6159985.4511632.3449995.9691630.49710015.361633.62810032.221639.783
10034.781640.47210043.881641.45110067.211647.94710090.431655.46310113.841666.459
10124.891670.99710136.381672.90410147.861672.83610154.481674.87610159.351676.986
10174.811685.98310193.811694.75310239.761713.16210251.241718.70510266.861727.445
#Mann= 3 , 0 , 0
9796.876  0.1035       09796.876  0.1035       010266.86  0.1035       0
#XS Ineff= 2 , 0
       0                               0
Bank Sta=9796.876,10266.86
Exp/Cntr=0.3,0.1

Type RM Length L Ch R = 1 ,86258.74,246.655200,246.655200,246.655200
XS GIS Cut Line= 6
534335.221183789787446.179429139 534207.53349685787531.409749995
534106.495756342787591.982010299534057.134244467787623.774049672
533982.618077433787675.403455077533921.785071154787721.138060183
#Sta/Elev= 30
9766.5091701.1039790.9921700.552 9800.071699.0359818.1341693.8719836.1991691.068
9875.0461683.0439890.3921680.5679908.4561675.2759911.0691674.454 9926.971663.548
9946.2871652.2119958.0611643.3199969.7491636.3379984.9191629.3339993.1251627.338
10004.391626.80210027.971633.34510039.621638.17910051.511640.50810080.351650.268
10099.151660.10910123.48 1671.3810133.821672.86210151.381672.93510159.981675.534
10172.151681.147 10186.51685.26810219.821701.15210234.271707.51810263.321714.954
#Mann= 3 , 0 , 0
9766.509    0.12       09766.509    0.12       010263.32    0.12       0
#XS Ineff= 2 , 0
       0                               0
Bank Sta=9766.509,10263.32
Exp/Cntr=0.3,0.1

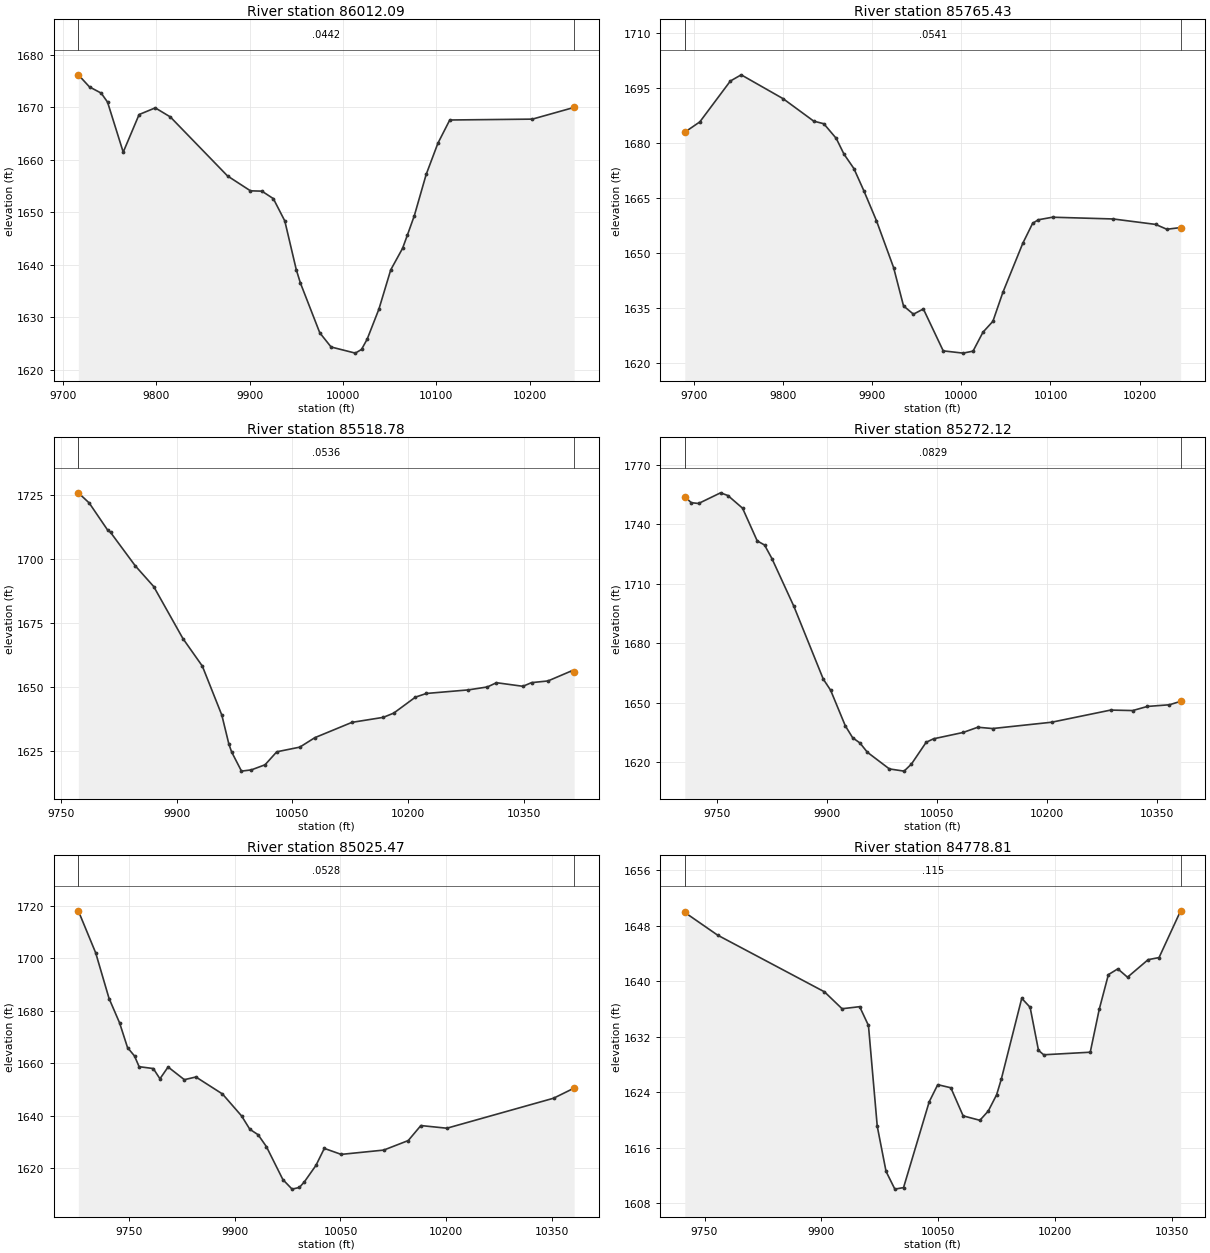
Type RM Length L Ch R = 1 ,86012.09,246.655200,246.655200,246.655200
XS GIS Cut Line= 6
 534224.62202886787206.400461287534178.047686571787240.899090616
534031.408465181787344.779440774533994.705936813787373.451804965
533816.406587196787511.180232317533800.487169014787525.195295213
#Sta/Elev= 30
 9716.761676.1679728.7341673.8639741.1781672.6939748.0081670.9889764.8081661.455
9781.8141668.6139799.113 1669.889815.2191668.1599876.4941656.9259901.0041654.099
9913.2591654.0359925.5141652.6129937.7691648.3699950.0241639.1189954.425 1636.58
9975.2311627.0799987.3111624.38510013.261623.21710019.891623.919 10025.91625.858
10038.541631.60710051.171639.05910063.811643.14710068.97 1645.6610076.441649.378
10089.081657.20510101.68 1663.1610114.351667.573 10202.81667.73910247.511669.972
#Mann= 3 , 0 , 0
 9716.76  0.0442       0 9716.76  0.0442       010247.51  0.0442       0
#XS Ineff= 2 , 0
       0                               0
Bank Sta=9716.76,10247.51
Exp/Cntr=0.3,0.1

Type RM Length L Ch R = 1 ,85765.43,246.655200,246.655200,246.655200
XS GIS Cut Line= 6
534136.127328505787014.543950894534082.430035891787053.551663189
534036.158666933787081.890568046533751.790467149787223.459992342
533700.315448748 787252.31329088533653.426596534787287.635908943
#Sta/Elev= 30
9689.8411683.0319706.7071685.8519740.9151697.0049753.1051698.7039800.1291692.185
9834.4631686.052 9845.791685.3379859.7061681.3429868.3861677.0429879.5171673.095
9890.6481667.0489904.8631658.8289924.0431646.0539935.1741635.5759946.3061633.314
9957.437 1634.74  9979.71623.294   100021622.67410013.141623.21910024.291628.393
10035.431631.36710046.581639.25210068.871652.63110080.021658.15210086.391659.106
10102.311659.80410170.361659.32610217.96 1657.84 10230.51656.51410245.991656.973
#Mann= 3 , 0 , 0
9689.841  0.0541       09689.841  0.0541       010245.99  0.0541       0
#XS Ineff= 2 , 0
       0                               0
Bank Sta=9689.841,10245.99
Exp/Cntr=0.3,0.1

Type RM Length L Ch R = 1 ,85518.78,246.655200,246.655200,246.655200
XS GIS Cut Line= 6
 533937.66087493786753.130083724533884.597607059786834.707116432
533811.215239801786930.148247756533612.286556723787131.346071212
533565.830867374787208.434654574533551.575198928 787257.72579487
#Sta/Elev= 30
9772.5351725.8199786.6071721.8739810.4931711.3069814.2491710.4129846.3211697.352
9870.2271689.2699908.0691668.9929933.2981658.2229958.5261639.1249967.6331627.864
 9971.14  1624.89984.0391617.2589996.8251617.74710014.561619.73210029.771624.801
 10059.61626.61710079.161630.31610127.271636.28610167.871638.23710181.411639.897
10209.521646.12510223.711647.55310278.111648.94810302.811650.09610314.591651.751
10348.871650.348   103601651.78110381.311652.43410412.491656.43710415.261656.003
#Mann= 3 , 0 , 0
9772.535  0.0536       09772.535  0.0536       010415.26  0.0536       0
#XS Ineff= 2 , 0
       0                               0
Bank Sta=9772.535,10415.26
Exp/Cntr=0.3,0.1

Type RM Length L Ch R = 1 ,85272.12,246.655200,246.655200,246.655200
XS GIS Cut Line= 6
533574.327920342 786586.27738058533575.337797083786704.172484227
533568.911096511786867.623399215533538.585232049787152.363687418
533534.882075058787209.490584975533536.029192202787260.233215291
#Sta/Elev= 30
9705.7631754.0419714.4891750.9829724.4931750.5629754.4981755.9379764.4981754.579
9784.4981748.1969804.4981731.6969814.4981729.6289824.4991722.8219854.5091698.674
9894.5241662.0319904.527 1656.449924.5521638.4949934.5661632.4779944.579 1629.81
9954.5931625.1669984.6341616.74910004.691615.63610014.731619.209 10034.81630.184
10044.841631.93410085.071635.116 10105.2 1637.7610125.331637.10610205.841640.289
 10286.31646.41310316.361646.17310336.391648.249 10366.41649.08810381.67 1650.82
#Mann= 3 , 0 , 0
9705.763  0.0829       09705.763  0.0829       010381.67  0.0829       0
#XS Ineff= 2 , 0
       0                               0
Bank Sta=9705.763,10381.67
Exp/Cntr=0.3,0.1

Type RM Length L Ch R = 1 ,85025.47,246.655100,246.655100,246.655100
XS GIS Cut Line= 6
533174.734923056786653.261631597533273.732647899786831.894266912
533352.821984532786961.262094502 533469.91345444787140.744141646
533504.923740345787214.868749174533520.009179615787262.817088302
#Sta/Elev= 30
  9678.61718.0239703.1581702.0349722.1611684.6099737.0491675.3289748.3461665.892
 9758.211662.7189764.7061658.6399784.8241657.9269794.2451654.026 9805.771658.523
9828.8191653.6849845.1771654.7129882.8631648.2299909.9131639.871 9921.621634.783
9933.3271632.7099945.0341628.1989968.4481615.6079981.4611611.9829991.8621612.625
    9999  1614.810015.351621.05810027.12  1627.510051.04 1625.2210111.271626.857
10146.011630.48310163.941636.20510200.771635.19210351.97 1646.6210381.131650.485
#Mann= 3 , 0 , 0
  9678.6  0.0528       0  9678.6  0.0528       010381.13  0.0528       0
#XS Ineff= 2 , 0
       0                               0
Bank Sta=9678.6,10381.13
Exp/Cntr=0.3,0.1

Type RM Length L Ch R = 1 ,84778.81,246.655200,246.655200,246.655200
XS GIS Cut Line= 6
 532956.96218102 786978.49199463533096.323939692787074.587692972
533193.186140731787125.327271501533418.175621522787222.608476872
533461.232799496787251.773456755533502.472383681787295.787556819
#Sta/Elev= 30
9724.6561649.9479766.7771646.6719904.0061638.4899926.598 1636.059949.1891636.348
9960.4851633.6369971.7811619.0869983.0771612.5819994.3721610.02210005.551610.244
10038.481622.62310049.461625.09410066.261624.64810082.061620.59410103.571619.952
10114.32 1621.2910125.071623.64110131.051625.88110157.321637.55610168.071636.257
10178.821630.04610185.521629.40710245.281629.77810256.821635.96210268.571640.971
 10280.71641.80610293.12  1640.610319.611643.13210333.631643.43310361.331650.178
#Mann= 3 , 0 , 0
9724.656   0.115       09724.656   0.115       010361.33   0.115       0
#XS Ineff= 2 , 0
       0                10161.77       0
Bank Sta=9724.656,10361.33
Exp/Cntr=0.3,0.1

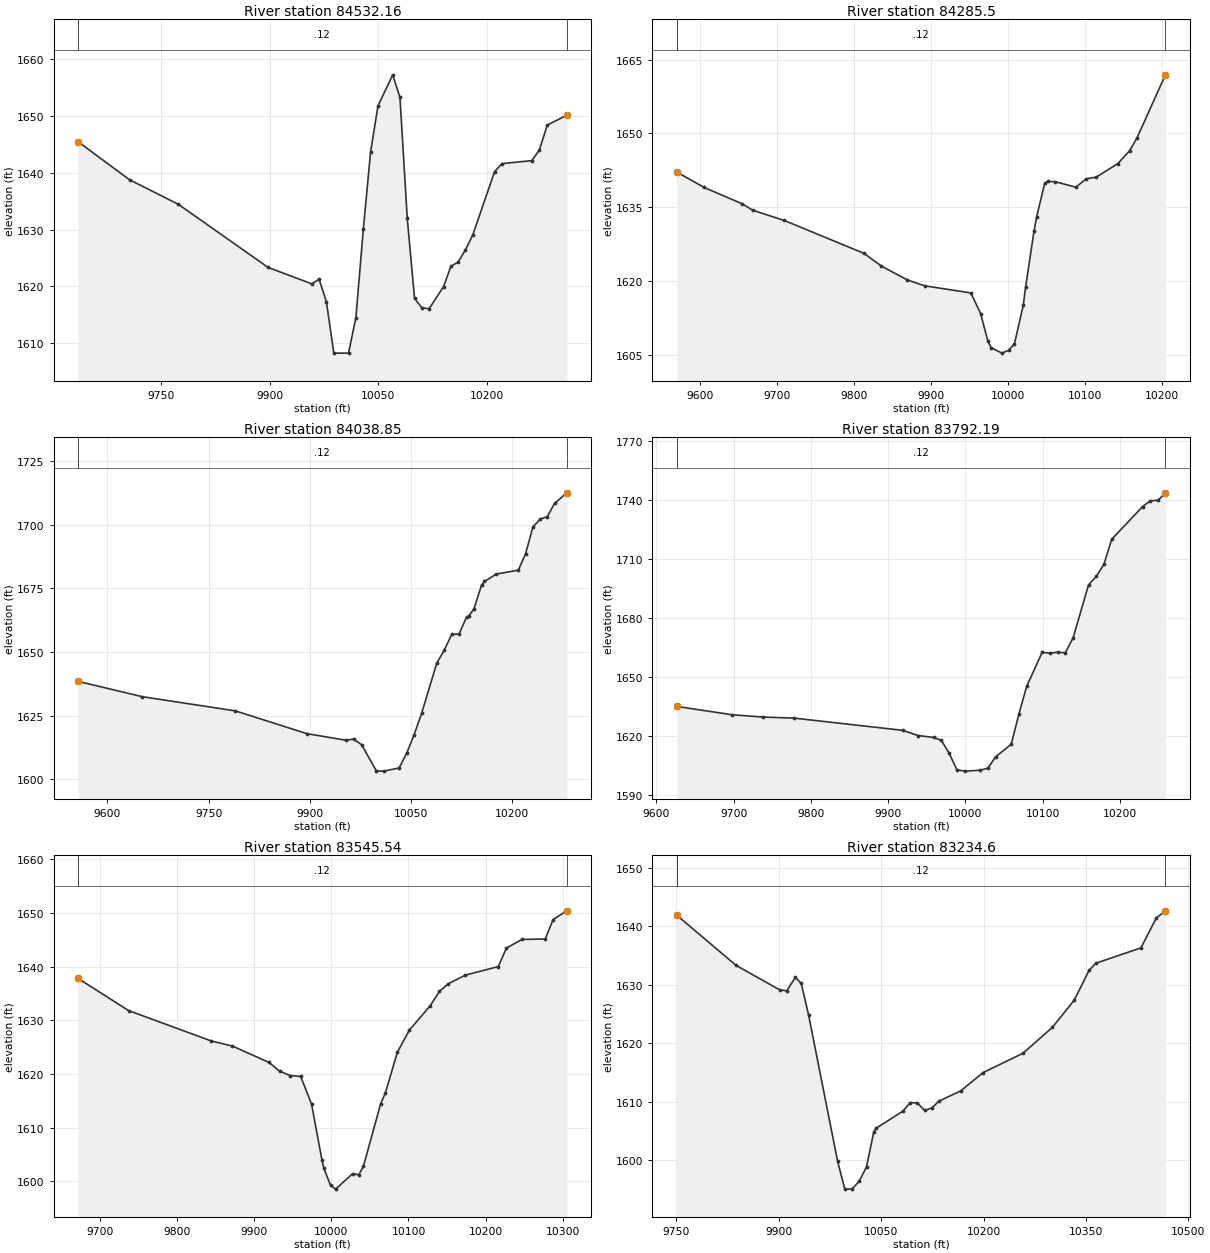
Type RM Length L Ch R = 1 ,84532.16,246.655200,246.655200,246.655200
XS GIS Cut Line= 6
532818.422071969787268.611281801532913.524532643 787333.20271777
533002.380461564787362.976676674533096.497823758787368.573386089
533342.087618317787345.220118041 533459.24601413 787378.36100633
#Sta/Elev= 30
9635.9431645.4549707.0551638.7479774.5221634.4179898.1771623.3249958.3071620.445
9968.3771621.2389978.4671617.2889988.6261608.26510008.951608.267 10019.11614.529
10029.331630.059 10039.41643.69210049.551651.73710069.82  1657.210079.851653.229
10089.891631.96710099.931617.90910109.961616.256   10120 1616.0610140.031619.972
10150.041623.52110160.04 1624.2910170.051626.40310180.051628.99410210.291640.169
 10220.41641.58810261.621642.11510272.091644.002 10282.91648.36310309.761650.082
#Mann= 3 , 0 , 0
9635.943    0.12       09635.943    0.12       010309.76    0.12       0
#XS Ineff= 2 , 0
       0                               0
Bank Sta=9635.943,10309.76
Exp/Cntr=0.3,0.1

Type RM Length L Ch R = 1 , 84285.5,246.655200,246.655200,246.655200
XS GIS Cut Line= 6
532787.558038845787327.091454676  532830.8177913787377.335630522
532899.805003788787434.740874327532939.849649672787459.929738828
 533085.58185999787539.086251716533282.823968113787715.372350676
#Sta/Elev= 30
9570.2491642.1689605.9921639.0119655.5051635.6819668.8251634.3949709.9271632.306
9813.3061625.6199835.8141623.0459869.5751620.2149892.0821619.0229951.8991617.582
9964.6931613.3469973.838 1607.87 9978.141606.455 9992.121605.341   100011605.922
10008.461607.20810019.991615.13110022.871618.69710033.881630.13210037.281633.058
10047.761639.86110051.691640.24110061.651640.17410088.231639.07110101.461640.767
10114.681641.12710142.631643.86810157.921646.48310167.561649.11910204.351661.915
#Mann= 3 , 0 , 0
9570.249    0.12       09570.249    0.12       010204.35    0.12       0
#XS Ineff= 2 , 0
       0                               0
Bank Sta=9570.249,10204.35
Exp/Cntr=0.3,0.1

Type RM Length L Ch R = 1 ,84038.85,246.655200,246.655200,246.655200
XS GIS Cut Line= 6
532758.193156581787379.703535425532808.980943046 787480.39598856
532860.377938953787571.454373027 532961.25730368787738.145679332
533046.699334358787912.478595895 533090.85590323 788021.90053369
#Sta/Elev= 30
9556.3481638.4929651.8711632.452 9789.61 1626.899895.4021617.9619953.4351615.366
9964.935 1615.819976.7331613.6059998.5911603.30610009.941603.22610032.261604.466
10043.541610.27410054.581617.53710065.741625.93410088.041645.60710099.111650.672
10110.171656.90810121.241657.112 10132.31663.78610135.391664.03810143.371667.051
10154.441676.25610158.741677.71310176.32 1680.6310208.931682.15410219.811688.662
10230.681699.17510241.431702.18910252.091703.24310262.741708.38810280.741712.542
#Mann= 3 , 0 , 0
9556.348    0.12       09556.348    0.12       010280.74    0.12       0
#XS Ineff= 2 , 0
       0                               0
Bank Sta=9556.348,10280.74
Exp/Cntr=0.3,0.1

Type RM Length L Ch R = 1 ,83792.19,246.655200,246.655200,246.655200
XS GIS Cut Line= 6
532728.092960067787433.633054189532735.486476384787476.040160677
532739.695710335787533.124458535532727.811486896787751.340953593
532739.787007551787868.276321952532745.916511087 788064.51894044
#Sta/Elev= 30
9626.1391635.0599698.2241630.8229738.3011629.6559778.318 1629.129918.7431622.921
9938.7471620.2929958.8141619.2949968.8621617.824 9978.911611.3089988.9581602.921
9999.007  1602.210019.121602.64910029.181603.75110039.231609.51410059.341615.835
10069.371631.36610079.371645.25810099.381662.55910109.381662.15410119.391662.588
10129.391662.345 10139.41669.86110159.411696.79410169.411701.07410179.421707.299
10189.421719.96210229.441736.58510239.451739.51710249.451739.75110258.981743.565
#Mann= 3 , 0 , 0
9626.139    0.12       09626.139    0.12       010258.98    0.12       0
#XS Ineff= 2 , 0
       0                               0
Bank Sta=9626.139,10258.98
Exp/Cntr=0.3,0.1

Type RM Length L Ch R = 1 ,83545.54,310.937600,310.937600,310.937600
XS GIS Cut Line= 6
532672.539375394 787419.97409349532662.611828244787498.671532479
532627.546557813787585.514315886 532432.11389971787805.615204956
532400.058811149787884.399818041 532392.33407632  787962.7300577
#Sta/Elev= 30
9671.8251637.8099737.4051631.8069844.5851626.142 9871.861625.1979919.3091622.148
9932.9361620.5329946.5621619.7059960.3671619.5419974.4661614.3719987.8481604.003
9990.4641602.384    99991599.26110005.641598.53910027.671601.42410035.631601.205
10041.681602.80510064.051614.48910070.181616.49110085.641624.05410101.09 1628.15
   101281632.67710140.121635.37610151.35 1636.7910173.681638.40810216.371640.009
10226.811643.43610247.021645.065 10277.31645.14310287.311648.74810305.051650.394
#Mann= 3 , 0 , 0
9671.825    0.12       09671.825    0.12       010305.05    0.12       0
#XS Ineff= 2 , 0
       0                               0
Bank Sta=9671.825,10305.05
Exp/Cntr=0.3,0.1

Type RM Length L Ch R = 1 , 83234.6,452.628400,452.628400,452.628400
XS GIS Cut Line= 5
532373.934795707787273.185434878532236.364573836787655.000000015
532256.747295707787754.956268221532311.000767946787896.015295997
532337.309122056787946.889540583
#Sta/Elev= 30
9750.3031641.8819837.2671633.2959901.0421629.1299911.6721628.9439924.1651631.244
 9932.931630.207 9943.561624.8549986.0771599.8799996.7061595.06910007.341595.083
10017.961596.44310028.591598.90310039.221604.87410042.17 1605.4410081.741608.376
10092.371609.838   101031609.81110113.631608.50610124.261608.93910134.891610.118
10166.351611.83610199.361614.97710258.211618.30210301.061622.723 10333.21627.397
10354.631632.43110364.721633.66510430.661636.27610453.181641.37910466.571642.611
#Mann= 3 , 0 , 0
9750.303    0.12       09750.303    0.12       010466.57    0.12       0
#XS Ineff= 2 , 0
       0                               0
Bank Sta=9750.303,10466.57
Exp/Cntr=0.3,0.1

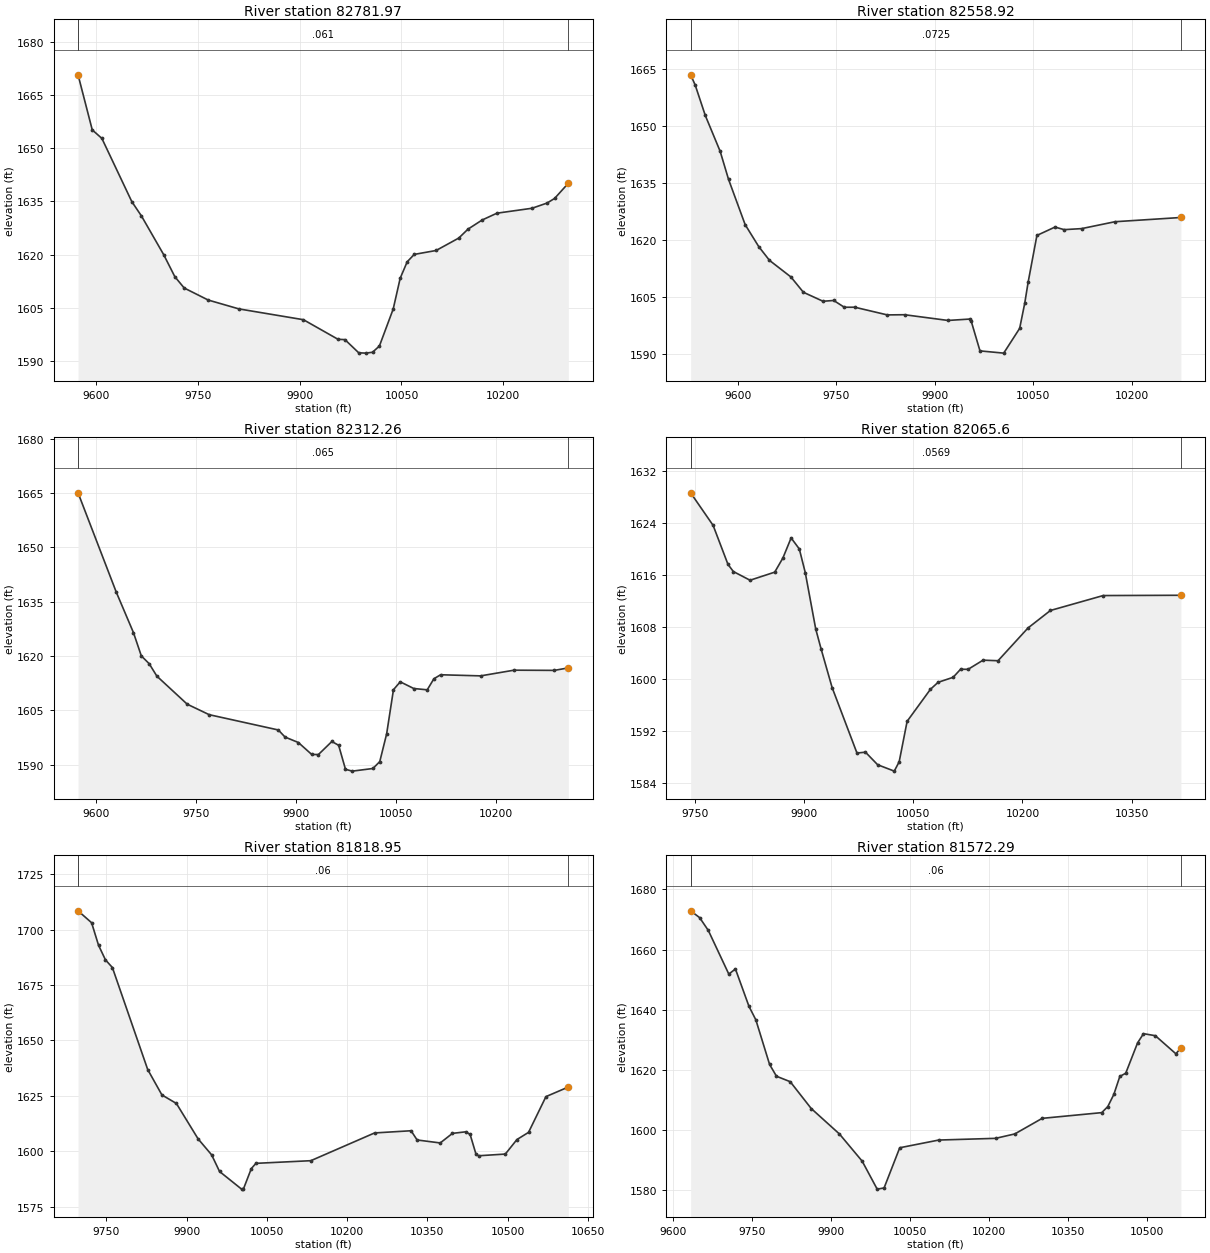
Type RM Length L Ch R = 1 ,82781.97,223.054700,223.054700,223.054700
XS GIS Cut Line= 6
531707.088323698787610.212155404531817.461073585787708.019307284
531909.964689097787759.665945947532204.438165123787842.998240412
532254.681605873787893.202574781532294.933035988787973.715258021
#Sta/Elev= 30
9573.0511670.6669593.9991655.1419608.1651652.7549652.343 1634.929666.5831630.874
9699.4371619.9469715.779 1613.779729.6161610.5749765.0411607.1859810.2571604.691
9905.4421601.645 9956.461596.1239966.6111596.0339986.9271592.3299997.1031592.227
10007.281592.46810017.461594.22910037.811604.65710048.12 1613.3410058.461617.974
10068.851620.05310101.061621.155 10134.51624.65610148.091627.16910168.981629.749
10190.811631.66910242.521633.05810264.731634.52810275.831635.82710296.051640.104
#Mann= 3 , 0 , 0
9573.051   0.061       09573.051   0.061       010296.05   0.061       0
#XS Ineff= 2 , 0
       0                               0
Bank Sta=9573.051,10296.05
Exp/Cntr=0.3,0.1

Type RM Length L Ch R = 1 ,82558.92,246.655200,246.655200,246.655200
XS GIS Cut Line= 6
531681.333314466787649.497541855531877.056218801787898.591028447
531928.259294809787953.251655117532021.224401085788023.628006418
 532087.96733415788091.760135178 532164.63307299 788211.13649269
#Sta/Elev= 30
9528.381 1663.49 9535.351660.7829550.6481652.804 9573.351643.3329586.0161635.996
9611.3491624.0569632.1121618.2539648.4051614.6479680.9911610.2839700.0141606.248
 9729.871603.8859746.1631604.0919762.2641602.3089778.1921602.3179827.7191600.292
9853.9621600.3419920.0771598.8359953.1861599.1999955.5421598.5929968.804 1590.82
10004.921590.232 10029.2 1596.7510036.961603.40510042.031608.83510055.451621.215
10082.961623.41510096.911622.73710123.521623.00910174.211624.82110274.631625.937
#Mann= 3 , 0 , 0
9528.381  0.0725       09528.381  0.0725       010274.63  0.0725       0
#XS Ineff= 2 , 0
       0                               0
Bank Sta=9528.381,10274.63
Exp/Cntr=0.3,0.1

Type RM Length L Ch R = 1 ,82312.26,246.655200,246.655200,246.655200
XS GIS Cut Line= 6
531654.435081676 787665.85378889531738.230098714787799.516126851
531777.257156992787907.149574094531782.138068227787973.844981841
531743.849130773788194.930306867531758.862976511788365.680063657
#Sta/Elev= 30
9572.4811665.078 9629.791637.7079655.6671626.5039667.4921620.0749679.3161617.913
9690.8531614.4789736.3941606.7439769.4441603.8449873.2541599.6259883.331 1597.67
9903.3321596.163 9923.421592.8649933.4981592.8469953.6551596.446 9963.841595.392
9974.1231588.7629984.4071588.266 10015.31588.99210025.611590.90110035.921598.554
10046.171610.74210056.341612.91410076.681611.06810096.881610.70710106.921613.764
10116.961614.86510177.041614.55610227.181616.12810287.711616.07210308.751616.759
#Mann= 3 , 0 , 0
9572.481   0.065       09572.481   0.065       010308.75   0.065       0
#XS Ineff= 2 , 0
       0                               0
Bank Sta=9572.481,10308.75
Exp/Cntr=0.3,0.1

Type RM Length L Ch R = 1 , 82065.6,246.655200,246.655200,246.655200
XS GIS Cut Line= 6
531409.501166481787804.021638476531513.386890386787996.909206372
531544.948271523 788048.81998759531557.393440726788077.261413255
531609.793108722788282.732110108531651.324140407788427.673039755
#Sta/Elev= 30
9743.9811628.6429774.8781623.6389795.3131617.6469802.6921616.5549825.6251615.218
9859.5271616.4599870.7971618.6369882.0671621.7139893.3371620.0219901.5531616.377
9915.8771607.7429923.2371604.6829938.4171598.7399972.576 1588.689984.277 1588.81
   100011586.88110023.86  1585.910030.611587.34310041.521593.55210073.551598.465
10084.07 1599.5410104.721600.30710115.011601.54910125.311601.53410145.891602.942
10166.471602.85510207.631607.883 10238.51610.57410310.961612.86510417.821612.908
#Mann= 3 , 0 , 0
9743.981  0.0569       09743.981  0.0569       010417.82  0.0569       0
#XS Ineff= 2 , 0
       0                               0
Bank Sta=9743.981,10417.82
Exp/Cntr=0.3,0.1

Type RM Length L Ch R = 1 ,81818.95,246.655200,246.655200,246.655200
XS GIS Cut Line= 6
531141.065359691787955.446965367 531393.45192992788243.198590606
531438.705469998788302.889973053531477.319677795788362.958889879
531526.947898848788454.978882904531640.885849008788713.533532511
#Sta/Elev= 30
9697.1451708.5119722.4571703.1379735.403 1692.999748.3481686.3789761.2931682.924
9827.3421636.8569853.8851625.4039880.9531621.5539921.5541605.5549946.781 1598.36
9961.6211590.84510002.761582.88610006.15  1582.910021.021592.17610029.591594.525
10132.191595.72110251.331608.246 10319.5 1609.2410330.861605.07110374.061603.731
10396.891608.05210421.961608.76710429.911607.56610440.911598.64910445.911597.949
10495.721598.71610517.41 1605.27 10539.11608.50810571.631624.64610613.421628.972
#Mann= 3 , 0 , 0
9697.145    0.06       09697.145    0.06       010613.42    0.06       0
#XS Ineff= 2 , 0
       0                10296.64       0
Bank Sta=9697.145,10613.42
Exp/Cntr=0.3,0.1

Type RM Length L Ch R = 1 ,81572.29,246.655100,246.655100,246.655100
XS GIS Cut Line= 6
 530924.60727615788077.551525327531056.989771378788242.140021816
 531201.98837148788393.566262836 531298.51741901788509.434164852
531385.302756802788641.440348807531479.363912656788818.155695832
#Sta/Elev= 30
9633.9821672.8999651.0681670.6299667.5071666.3789706.3611651.878 9718.961653.567
9744.6391641.1519757.6821636.6649783.7681621.8349796.8111617.9219822.897 1616.11
9862.697  1607.29916.3051598.7249959.4051589.6999987.8571580.40310000.961580.792
10030.661594.15310104.681596.71510212.571597.28310248.961598.74910300.871603.926
10413.881605.82910425.371607.83610436.861611.88610448.171617.854 10459.41618.929
10481.871629.00710493.111632.07310515.581631.395 10554.5 1625.3910564.071627.306
#Mann= 3 , 0 , 0
9633.982    0.06       09633.982    0.06       010564.07    0.06       0
#XS Ineff= 2 , 0
       0                               0
Bank Sta=9633.982,10564.07
Exp/Cntr=0.3,0.1

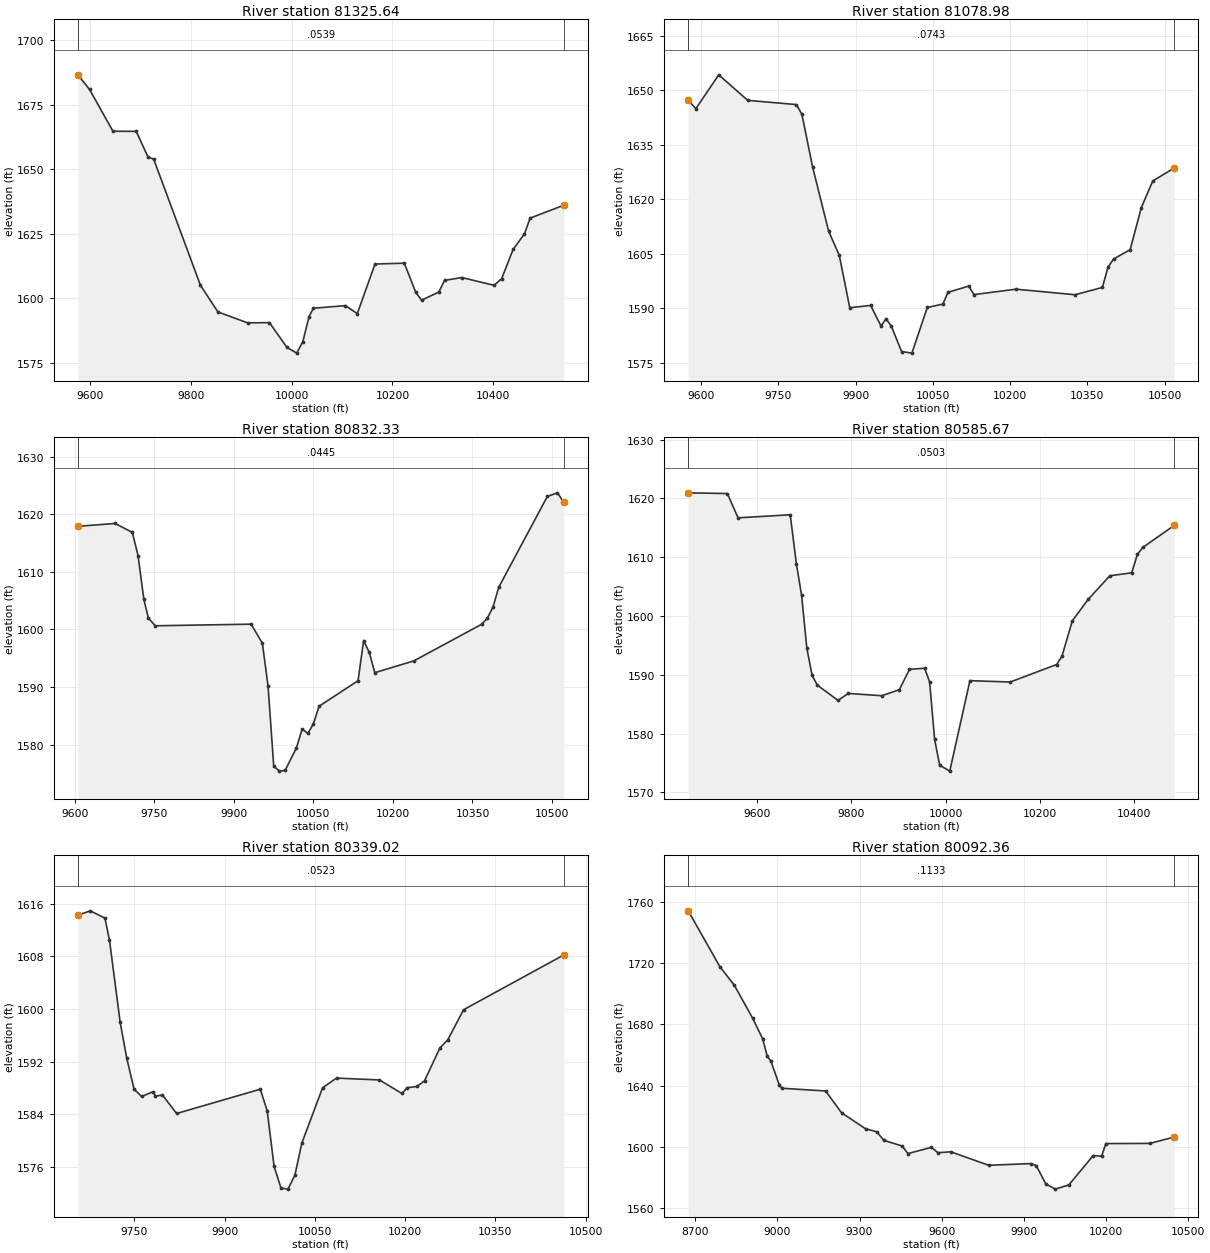
Type RM Length L Ch R = 1 ,81325.64,246.655200,246.655200,246.655200
XS GIS Cut Line= 6
530750.249892736788144.843531138530898.577058603788400.517022202
531020.169148727788578.414905016531080.283362932788676.734276202
531155.010665097788813.141983606531238.526074265788974.152932092
#Sta/Elev= 30
9576.2351686.5939599.5381680.9119645.7821664.7489692.0261664.6859715.1481654.816
9726.7091653.8679819.1971605.109 9853.881594.7419912.9131590.4999956.1281590.595
9990.7181580.99510010.151578.77810022.321583.26510034.491592.89310043.181596.168
10106.771597.18710130.211594.08310165.381613.297 10223.41613.627 10246.21602.281
10257.611599.29410291.81 1602.4110303.221606.96110337.421608.06210401.521605.035
10416.531607.66810439.061618.93110461.591624.97310472.851631.08510539.491636.076
#Mann= 3 , 0 , 0
9576.235  0.0539       09576.235  0.0539       010539.49  0.0539       0
#XS Ineff= 2 , 0
       0                10164.76       0
Bank Sta=9576.235,10539.49
Exp/Cntr=0.3,0.1

Type RM Length L Ch R = 1 ,81078.98,246.655200,246.655200,246.655200
XS GIS Cut Line= 6
530626.932473873788181.576379324 530689.97545886788322.263684261
530729.742716546788446.140100191530765.938849605  788771.4301545
530816.638461758788940.533186633 530877.65707291 789082.83050699
#Sta/Elev= 30
9574.7431647.2299589.6321644.936    96341654.2269690.3821647.2039784.9751646.046
9795.5731643.3879816.3641628.8979847.5511611.2239868.1721604.6089888.5791590.188
9929.0861590.824 9949.181585.1729959.1871587.1239969.1941585.1679989.2091578.155
10009.221577.70810039.231590.27110069.311591.17910079.361594.42510119.61 1596.14
10129.781593.80310211.551595.28910326.33 1593.7610379.381595.78210390.151601.324
10400.911603.576 10433.21606.14110455.061617.73410477.061625.02710518.691628.585
#Mann= 3 , 0 , 0
9574.743  0.0743       09574.743  0.0743       010518.69  0.0743       0
#XS Ineff= 2 , 0
       0                10213.09       0
Bank Sta=9574.743,10518.69
Exp/Cntr=0.3,0.1

Type RM Length L Ch R = 1 ,80832.33,246.655200,246.655200,246.655200
XS GIS Cut Line= 6
530361.066947341788260.770365949530413.591603658788382.932554211
530518.759013888788666.933564959530610.339513517788941.387819176
530636.373285937789005.584381207530689.258663848789115.466451846
#Sta/Elev= 30
9605.6661617.895 9675.991618.3929708.4451616.8419719.2631612.8039730.081 1605.26
9738.6631601.9869751.5061600.6239932.4371600.9049953.7231597.5949964.4141590.154
9975.1441576.2439985.8741575.3839996.6041575.50610018.041579.43910028.751582.702
10039.451581.93910050.011583.58910060.531586.64510134.161591.08410144.671598.051
10155.191596.03410165.711592.48110239.341594.52610367.151600.87810377.941601.919
10388.731603.88610399.521607.31610491.211623.08210510.331623.71110522.131622.048
#Mann= 3 , 0 , 0
9605.666  0.0445       09605.666  0.0445       010522.13  0.0445       0
#XS Ineff= 2 , 0
       0                               0
Bank Sta=9605.666,10522.13
Exp/Cntr=0.3,0.1

Type RM Length L Ch R = 1 ,80585.67,246.655200,246.655200,246.655200
XS GIS Cut Line= 6
530042.184594287788222.754147611530135.026078016788392.763848661
530202.675199525788536.954649626530324.002865516788848.301452335
 530379.11296868788969.016485018530487.805617681789150.363829922
#Sta/Elev= 30
9453.6931620.9569536.8051620.8319559.5561616.7049670.2151617.2239683.2831608.908
9694.4061603.5099705.5281594.513 9716.651589.9229727.7611588.2469771.6531585.654
  9793.61586.8339864.7061586.4449901.9171587.4729923.315 1590.939955.4111591.119
 9966.111588.8099976.8091579.0099987.5081574.621 10008.91573.61810051.721589.006
10137.361588.77610235.891591.75210246.981593.14210269.171599.19510303.051602.863
10348.761606.84810395.141607.35110407.351610.52110418.921611.67810485.211615.403
#Mann= 3 , 0 , 0
9453.693  0.0503       09453.693  0.0503       010485.21  0.0503       0
#XS Ineff= 2 , 0
       0                               0
Bank Sta=9453.693,10485.21
Exp/Cntr=0.3,0.1

Type RM Length L Ch R = 1 ,80339.02,246.655100,246.655100,246.655100
XS GIS Cut Line= 6
529865.351411627788517.812078568529986.549005949788705.448095098
530085.399107588788880.025716652530125.732820155788943.150000892
530182.100299886 789018.29523049530324.922250665789178.579846265
#Sta/Elev= 30
 9655.911614.2429676.7191614.9079700.9331613.7979708.5071610.4599726.2471597.967
9737.2531592.493 9749.36 1587.799761.935 1586.699781.0111587.4079784.8771586.751
 9796.621586.8889820.1061584.0959959.1681587.7879970.6441584.4959982.1211576.062
9993.5971572.75710005.161572.59710016.671574.71310028.171579.57910062.681588.006
10085.871589.47710157.191589.197 10194.71587.13710203.651588.024 10219.7  1588.2
 10232.21589.06910257.631594.05110270.781595.29510297.071599.87110463.571608.196
#Mann= 3 , 0 , 0
 9655.91  0.0523       0 9655.91  0.0523       010463.57  0.0523       0
#XS Ineff= 2 , 0
       0                               0
Bank Sta=9655.91,10463.57
Exp/Cntr=0.3,0.1

Type RM Length L Ch R = 1 ,80092.36,109.601100,109.601100,109.601100
XS GIS Cut Line= 4
528828.309260802788155.468935551529501.920371936788747.482824447
530081.781483041789084.288380014530259.203714214789190.059325483
#Sta/Elev= 30
8674.6941753.9718790.1071717.612 8843.361705.3648909.9261683.951 8946.65 1670.46
8963.1781659.1828976.4911655.9569007.2421640.3859016.4311638.2819176.189 1636.51
9234.4641622.2729322.6341611.8219362.5731609.925  9389.21604.2999455.7661600.611
9476.8341595.6869562.2711599.742 9586.61 1596.259632.8681596.8639771.6421588.065
9924.9211589.1489945.1091587.8999979.8031575.995 10014.51572.50310064.291575.254
10153.271594.40510183.751593.99910199.531602.21410360.63 1602.3110448.621606.478
#Mann= 3 , 0 , 0
8674.694  0.1133       08674.694  0.1133       010448.62  0.1133       0
#XS Ineff= 2 , 0
       09893.776                       0
Bank Sta=8674.694,10448.62
Exp/Cntr=0.3,0.1