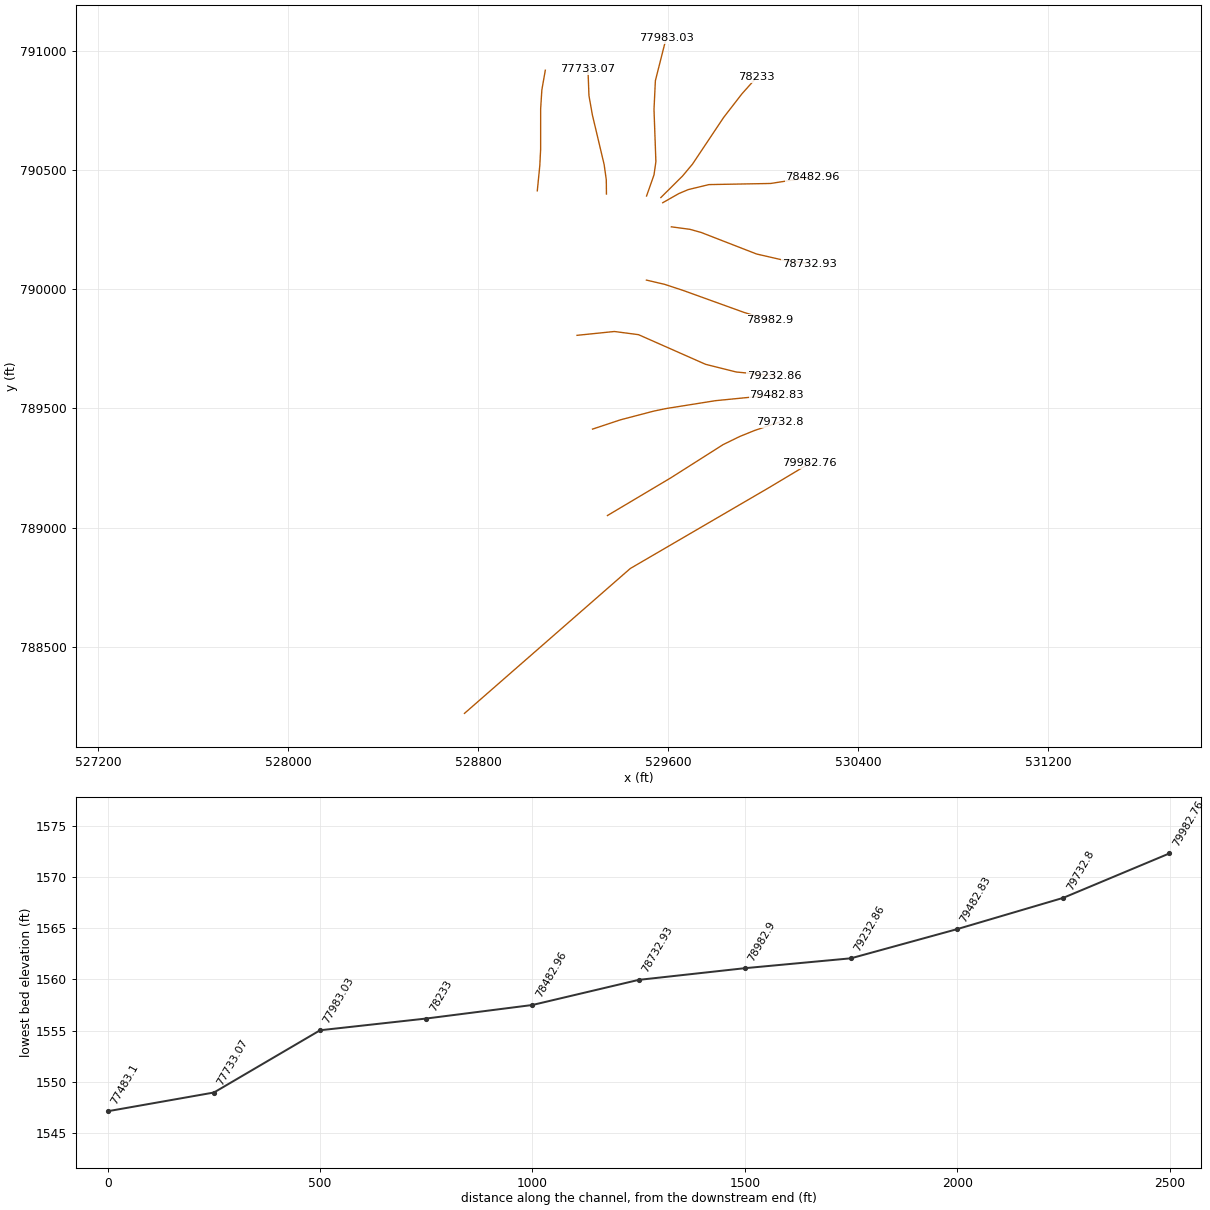
HEC-RAS study 5238_ras.prj: 5238

--- 5238_ras.g01 (geometry) --- (continued)

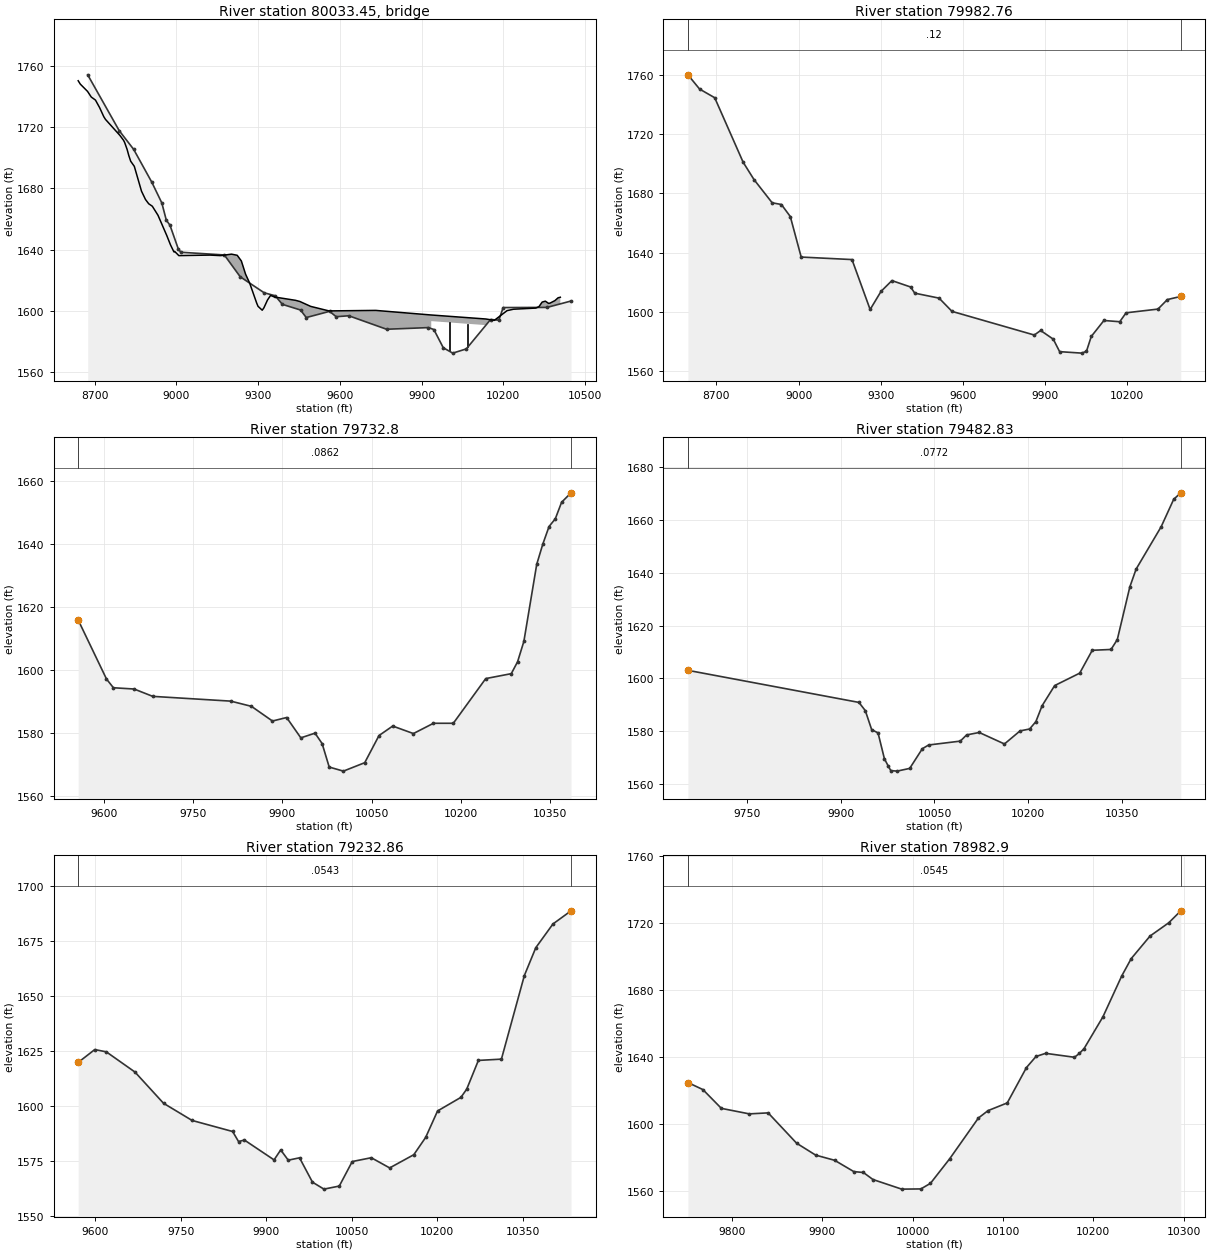
Type RM Length L Ch R = 3 ,80033.45,,,
BEGIN DESCRIPTION:
END DESCRIPTION:
Bridge Culvert--1,0,-1,-1, 0
Deck Dist Width WeirC Skew NumUp NumDn MinLoCord MaxHiCord MaxSubmerge Is_Ogee
34.787450,40.026200,2.6,0, 60, 60, , , 0.95, 0, 0,0,,
 8639.71 8647.53 8673.96 8687.80 8703.10 8718.40 8733.70 8740.01 8792.86 8806.07
 8810.21 8819.28 8825.51 8832.49 8845.71 8872.13 8886.72 8898.55 8911.76 8932.63
 8964.61 8978.54 8991.03 8993.84 9009.14 9123.15 9162.78 9202.41 9223.37 9238.67
 9253.97 9269.28 9294.89 9299.88 9315.18 9321.32 9334.53 9345.79 9360.95 9437.60
 9453.43 9493.06 9560.02 9731.70 9935.63 9935.6310136.0910136.0910167.0210213.86
10237.2810319.2510330.9610342.6710354.3810366.0910371.8510389.5110401.2310409.42
 1750.11 1747.90 1743.19 1739.47 1737.51 1732.58 1726.66 1724.89 1714.46 1711.32
 1709.87 1705.35 1701.33 1697.62 1694.30 1678.09 1672.69 1669.89 1668.30 1662.40
 1649.29 1643.10 1638.53 1638.82 1636.08 1636.43 1636.08 1637.05 1636.30 1632.58
 1624.04 1618.08 1605.12 1603.01 1600.49 1602.02 1607.13 1610.12 1609.08 1606.93
 1606.17 1602.98 1600.04 1600.36 1597.37 1597.37 1594.76 1594.76 1593.87 1600.21
 1601.13 1601.87 1602.82 1605.79 1606.38 1604.95 1605.14 1606.75 1608.60 1608.94
  750.11  747.90  743.19  739.47  737.51  732.58  726.66  724.89  714.46  711.32
  709.87  705.35  701.33  697.62  694.30  678.09  672.69  669.89  668.30  662.40
  649.29  643.10  638.53  638.82  636.08  636.43  636.08  637.05  636.30  632.58
  624.04  618.08  605.12  603.01  600.49  602.02  607.13  610.12  609.08  606.93
  606.17  602.98  600.04  600.36  597.37 1593.37 1590.76  594.76  593.87  600.21
  601.13  601.87  602.82  605.79  606.38  604.95  605.14  606.75  608.60  608.94
 8639.71 8647.53 8673.96 8687.80 8703.10 8718.40 8733.70 8740.01 8792.86 8806.07
 8810.21 8819.28 8825.51 8832.49 8845.71 8872.13 8886.72 8898.55 8911.76 8932.63
 8964.61 8978.54 8991.03 8993.84 9009.14 9123.15 9162.78 9202.41 9223.37 9238.67
 9253.97 9269.28 9294.89 9299.88 9315.18 9321.32 9334.53 9345.79 9360.95 9437.60
 9453.43 9493.06 9560.02 9731.70 9894.83 9894.8310095.2910095.2910167.0210213.86
10237.2810319.2510330.9610342.6710354.3810366.0910371.8510389.5110401.2310409.42
 1750.11 1747.90 1743.19 1739.47 1737.51 1732.58 1726.66 1724.89 1714.46 1711.32
 1709.87 1705.35 1701.33 1697.62 1694.30 1678.09 1672.69 1669.89 1668.30 1662.40
 1649.29 1643.10 1638.53 1638.82 1636.08 1636.43 1636.08 1637.05 1636.30 1632.58
 1624.04 1618.08 1605.12 1603.01 1600.49 1602.02 1607.13 1610.12 1609.08 1606.93
 1606.17 1602.98 1600.04 1600.36 1597.92 1597.92 1595.20 1595.20 1593.87 1600.21
 1601.13 1601.87 1602.82 1605.79 1606.38 1604.95 1605.14 1606.75 1608.60 1608.94
  750.11  747.90  743.19  739.47  737.51  732.58  726.66  724.89  714.46  711.32
  709.87  705.35  701.33  697.62  694.30  678.09  672.69  669.89  668.30  662.40
  649.29  643.10  638.53  638.82  636.08  636.43  636.08  637.05  636.30  632.58
  624.04  618.08  605.12  603.01  600.49  602.02  607.13  610.12  609.08  606.93
  606.17  602.98  600.04  600.36  597.92 1593.92 1591.20  595.20  593.87  600.21
  601.13  601.87  602.82  605.79  606.38  604.95  605.14  606.75  608.60  608.94
Pier Skew, UpSta & Num, DnSta & Num=  ,10001.79, 2 ,9960.98, 2 , 0 , 0 , 0 ,,
    4.00    4.00
  596.47 1596.47
    4.00    4.00
  597.02 1597.02
Pier Skew, UpSta & Num, DnSta & Num=  ,10069.94, 2 ,10029.14, 2 , 0 , 0 , 0 ,,
    4.00    4.00
  595.55 1595.55
    4.00    4.00
  596.10 1596.10
BR Coef=-1 , 0 , 0 ,, 0 ,,,0.8,0,1,0,
WSPro=,,,, 1 ,,,, 0 ,,,, 0 ,,,,-1 ,-1 ,-1 , 0 , 0 , 0 , 0 , 0
BC Design=,, 0 ,, 0 ,,,,,,

Type RM Length L Ch R = 1 ,79982.76,249.966200,249.966200,249.966200
XS GIS Cut Line= 4
528742.892594159 788220.74671331529440.809260815788828.385602206
 530020.67037192789165.191157773530196.589689106 789270.06613532
#Sta/Elev= 30
8595.7321759.9768638.3041750.3888693.5831744.5318797.4121701.0728837.1891689.344
8903.4851673.7078937.2471672.555 8969.781664.4329009.5571637.1239195.184 1635.43
9261.4791601.7719301.2561613.9729341.034 1621.259409.3451616.9439424.5741612.774
9513.4011609.4329560.6441600.496 9861.321584.5569884.4491587.6159930.7071581.753
9953.8361573.35210034.791572.35610051.931573.61210069.48  1583.610115.741594.361
10173.561593.52110196.721599.53910313.151602.04210347.541608.46110396.491610.585
#Mann= 3 , 0 , 0
8595.732    0.12       08595.732    0.12       010396.49    0.12       0
#XS Ineff= 2 , 0
       0 9858.31                       0
Bank Sta=8595.732,10396.49
Exp/Cntr=0.3,0.1

Type RM Length L Ch R = 1 , 79732.8,249.966200,249.966200,249.966200
XS GIS Cut Line= 6
529344.586670547789050.550668865529611.377436084789208.672745467
 529831.87813112789348.226055175529901.681979375789382.194671057
529964.549826867789407.564729112530070.159840658789443.007495776
#Sta/Elev= 30
9557.0271615.9339604.5971597.2129616.1961594.4439650.9931594.0439682.2811591.714
9813.3761590.2019848.1731588.5469883.4061583.8919907.2441585.0039931.0811578.555
9954.919 1580.059966.8381576.7439978.7571569.29210002.591568.00210038.431570.676
10062.441579.29510085.431582.297 10120.21579.91810153.891583.17610187.251583.177
10241.731597.35210284.641598.91410295.211602.67810305.791609.14110327.411633.604
 10337.51639.93310348.071645.57310358.641648.04510369.151653.26410385.011656.265
#Mann= 3 , 0 , 0
9557.027  0.0862       09557.027  0.0862       010385.01  0.0862       0
#XS Ineff= 2 , 0
       0                               0
Bank Sta=9557.027,10385.01
Exp/Cntr=0.3,0.1

Type RM Length L Ch R = 1 ,79482.83,249.966200,249.966200,249.966200
XS GIS Cut Line= 6
529281.866916757789413.101440839529399.802553672789452.154991894
529539.864612003789488.639532007529591.309518691789499.308478799
529799.760474635789532.411857179530056.296811169 789557.60853962
#Sta/Elev= 30
9654.5741603.056 9928.831590.9239939.0431587.8149949.2561580.6159959.4681579.391
9969.6811569.6179976.1251566.7179979.8611565.1469989.9831564.93410010.241565.966
10030.531573.42410040.671574.82210091.391576.28610101.531578.629 10121.81579.552
 10162.21575.20610187.211580.14610202.521580.86610212.571583.64610222.611589.687
10242.711597.288 10282.9 1601.9910302.99 1610.6410333.14 1610.9510343.181614.685
10363.281634.60310373.331641.33910413.521657.36410433.611667.73810444.981670.194
#Mann= 3 , 0 , 0
9654.574  0.0772       09654.574  0.0772       010444.98  0.0772       0
#XS Ineff= 2 , 0
       0                               0
Bank Sta=9654.574,10444.98
Exp/Cntr=0.3,0.1

Type RM Length L Ch R = 1 ,79232.86,249.966200,249.966200,249.966200
XS GIS Cut Line= 6
529216.581932499789806.460562124529373.938471574789822.559235738
529475.447006665789809.243968715529757.672340494789684.941411794
529886.310810584789652.768213137 530046.67274255789637.167506904
#Sta/Elev= 30
9569.9831619.7939599.0521625.6459619.3281624.6179669.6811615.3979719.6941601.196
9769.8291593.3669841.0031588.3289851.3511583.7539861.6981584.4369913.6961575.397
9925.3591579.9319938.6041575.2639958.4181576.3429981.1291565.24110001.271562.076
10028.151563.47110050.891574.644 10084.3 1576.3810116.571571.73810158.921577.759
10179.761585.652 10200.61597.68110241.571603.87610251.791607.63610272.231620.712
10312.651621.28910352.921659.385   103731672.065 10403.1 1682.87 10434.81688.854
#Mann= 3 , 0 , 0
9569.983  0.0543       09569.983  0.0543       0 10434.8  0.0543       0
#XS Ineff= 2 , 0
       09901.485                       0
Bank Sta=9569.983,10434.8
Exp/Cntr=0.3,0.1

Type RM Length L Ch R = 1 , 78982.9,249.966200,249.966200,249.966200
XS GIS Cut Line= 6
529508.726693132790038.161579171529585.365271565790020.301940396
 529663.67148438 789994.63190837529920.091513094789902.458297891
530000.982330227789877.602037384530028.008033221789871.378155773
#Sta/Elev= 30
9750.9961624.7179767.6071620.5169788.0261609.3119818.9931606.0239839.8611606.624
9871.4321588.4949892.4791581.4169913.5371578.3119934.7521571.568 9945.361571.034
9955.968 1566.84 9987.791561.10610009.021561.22410019.661564.55410040.931579.196
10072.841603.58810083.481607.96610104.751612.56610126.021633.68310136.65 1640.31
10147.291642.155 10179.21639.81210184.611642.09410189.751644.91310210.671663.895
10231.591688.37810242.061698.70210262.981712.19910283.621720.06810296.971727.225
#Mann= 3 , 0 , 0
9750.996  0.0545       09750.996  0.0545       010296.97  0.0545       0
#XS Ineff= 2 , 0
       0                               0
Bank Sta=9750.996,10296.97
Exp/Cntr=0.3,0.1

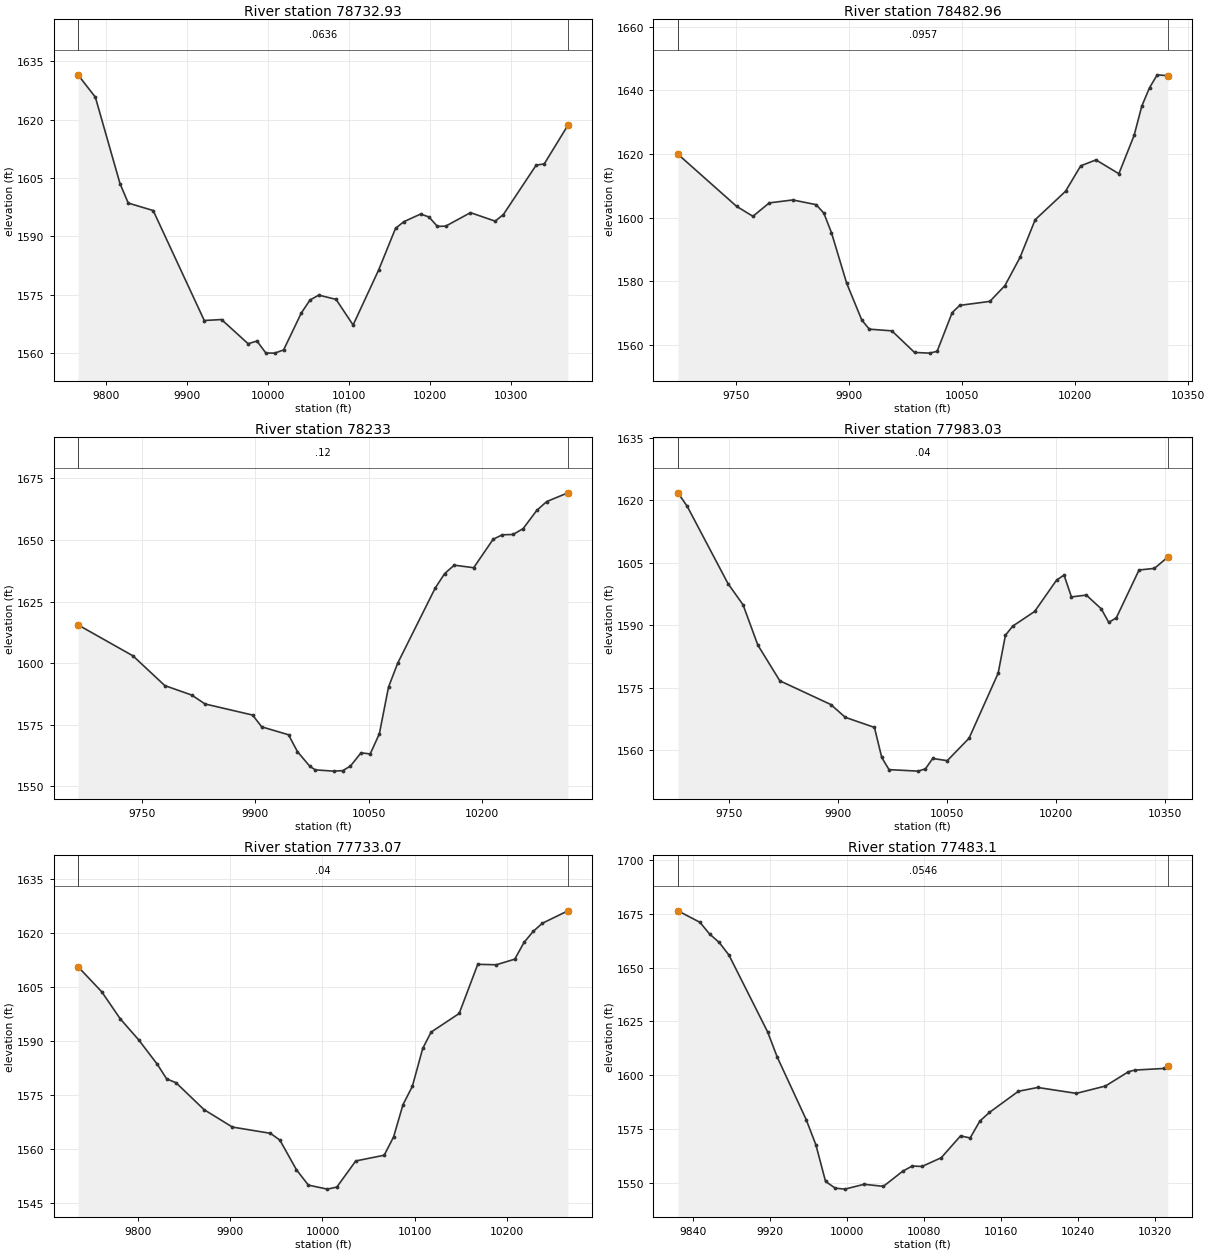
Type RM Length L Ch R = 1 ,78732.93,249.966200,249.966200,249.966200
XS GIS Cut Line= 6
 529613.65610623790261.565916235529692.371094766790251.046019009
529739.331540567790237.881628065529972.803981574 790147.50918401
530092.125195686790120.227733087530193.957853378790107.402792988
#Sta/Elev= 30
9765.588 1631.529786.9671625.7669817.3331603.5489827.4891598.5489858.2461596.627
9921.2411568.3499942.5441568.5959975.2911562.3819986.2291563.0639997.1681559.994
10008.13 1559.9610019.091560.78710040.88 1570.2810051.631573.62210062.371574.874
10083.741573.78210104.761567.19210136.28 1581.3510157.07 1592.05 10167.41593.767
10188.051595.72810198.371594.96210208.661592.55610218.861592.60410249.46 1596.08
10279.921593.89710290.021595.58810330.411608.276 10340.51608.635 10369.61618.545
#Mann= 3 , 0 , 0
9765.588  0.0636       09765.588  0.0636       0 10369.6  0.0636       0
#XS Ineff= 2 , 0
       0                               0
Bank Sta=9765.588,10369.6
Exp/Cntr=0.3,0.1

Type RM Length L Ch R = 1 ,78482.96,249.966200,249.966200,249.966200
XS GIS Cut Line= 6
529577.383977187790362.609704225529645.514388124790401.275141262
529685.210308402790417.817646359529771.747924012790438.725556675
530031.577780492790443.458486957 530208.77333519790471.025707448
#Sta/Elev= 30
9672.8311619.946 9750.65 1603.599772.3421600.4529794.0091604.6659825.288 1605.59
9856.258 1604.119866.4081601.4619876.557 1595.339896.7071579.4759916.7651567.912
9926.7651565.0279956.7671564.4929986.7691557.71810006.771557.50110016.771558.068
10036.771570.22910046.771572.49110086.781573.74710106.821578.72710126.851587.579
 10146.91599.38310187.151608.30110207.321616.29710227.57 1618.1610257.951613.821
10278.211625.87110288.391635.05710298.611640.80810308.831644.871 10322.91644.593
#Mann= 3 , 0 , 0
9672.831  0.0957       09672.831  0.0957       0 10322.9  0.0957       0
#XS Ineff= 2 , 0
       0                               0
Bank Sta=9672.831,10322.9
Exp/Cntr=0.3,0.1

Type RM Length L Ch R = 1 ,   78233,249.966200,249.966200,249.966200
XS GIS Cut Line= 6
529569.546765587790384.441936484529660.905486648 790474.81158888
529702.629163642 790524.53885735529833.682464865790720.203056179
529910.736677943790819.379908351529973.027529448790888.740510462
#Sta/Elev= 30
9665.6561615.5569738.3391602.9699780.4271590.8979816.1211587.047  9833.61583.445
9896.5181578.9429908.5951574.1529944.0311570.9389955.8441564.0779972.262 1558.13
9979.468 1556.6810003.671556.17410015.77 1556.3710025.951558.24510039.971563.619
10052.071563.14910064.171571.34910076.271590.28210088.371599.96710138.02 1630.49
10150.481636.35110163.15  1639.810188.891638.75710214.641650.30810226.75 1652.12
10241.051652.26210254.351654.63710272.271661.99910285.481665.61610313.521669.164
#Mann= 3 , 0 , 0
9665.656    0.12       09665.656    0.12       010313.52    0.12       0
#XS Ineff= 2 , 0
       0                               0
Bank Sta=9665.656,10313.52
Exp/Cntr=0.3,0.1

Type RM Length L Ch R = 1 ,77983.03,249.966100,249.966100,249.966100
XS GIS Cut Line= 6
529509.328628597790390.815352397529540.617357295790479.422074939
529548.596601438790534.854228894529540.638694272790753.780774386
529546.466355792790874.696932795529591.581697114791052.218928412
#Sta/Elev= 30
  9679.51621.8249692.3821618.5569748.3881600.0449769.1431594.948 9789.471585.288
 9819.781576.7029889.9271571.0149909.9371567.9329950.004 1565.529960.0371558.311
9970.0711555.38510010.191555.02410020.211555.57710030.23 1558.0610050.271557.539
10080.271562.92310120.311578.52310130.321587.64110140.371589.83110170.531593.345
10200.931600.91910211.061602.066 10221.21596.84210241.681597.279 10262.21593.994
10272.521590.73510282.951591.80510314.24  1603.310335.421603.68810353.861606.394
#Mann= 3 , 0 , 0
  9679.5    0.04       0  9679.5    0.04       010353.86    0.04       0
#XS Ineff= 2 , 0
       0                               0
Bank Sta=9679.5,10353.86
Exp/Cntr=0.3,0.1

Type RM Length L Ch R = 1 ,77733.07,249.966200,249.966200,249.966200
XS GIS Cut Line= 6
 529340.44123939 790399.25972184529339.812364038 790458.51421781
529330.771490923790522.787018283529281.311009987790730.662191398
529266.902697427790811.465842848529262.569491036790922.583795369
#Sta/Elev= 30
 9734.861610.7169760.649 1603.739780.6661596.2349800.7411590.3699820.9381583.573
9831.0361579.5379841.1351578.4929871.5941571.0049902.2911566.1689943.4571564.436
9953.767 1562.569971.8331554.2919984.6971550.039 10005.31548.92310015.581549.495
10036.141556.75410066.971558.341 10077.21563.45210087.361572.39310097.51 1577.48
10108.741587.99510117.831592.541 10148.31597.72110168.461611.38210188.551611.259
10208.621612.81810218.621617.44510228.621620.54210238.621622.80410266.241626.244
#Mann= 3 , 0 , 0
 9734.86    0.04       0 9734.86    0.04       010266.24    0.04       0
#XS Ineff= 2 , 0
       0                               0
Bank Sta=9734.86,10266.24
Exp/Cntr=0.3,0.1

Type RM Length L Ch R = 1 , 77483.1,249.966200,249.966200,249.966200
XS GIS Cut Line= 6
529049.359379238790412.493487842529059.877736445790518.150584176
529063.417856781790586.171777146529063.559159492 790757.42840308
529068.540984315 790835.81033944529083.155217807790918.552013951
#Sta/Elev= 30
 9824.661676.3849847.427 1671.079857.4641665.6399867.5011661.6739877.5391655.863
9917.6871620.1579927.7241608.3919957.7731579.3349967.7861567.662  9977.81550.683
9987.8131547.5489997.8271547.08810017.841549.33910037.85 1548.3810057.85 1555.42
10067.851557.83910077.851557.60910097.851561.68310117.851571.81610127.851570.873
10137.851578.69210147.851582.73410177.871592.54710197.911594.31510237.991591.576
10268.23 1594.9910292.041601.61910298.571602.39110329.221603.15910332.89 1604.21
#Mann= 3 , 0 , 0
 9824.66  0.0546       0 9824.66  0.0546       010332.89  0.0546       0
#XS Ineff= 2 , 0
       0                               0
Bank Sta=9824.66,10332.89
Exp/Cntr=0.3,0.1