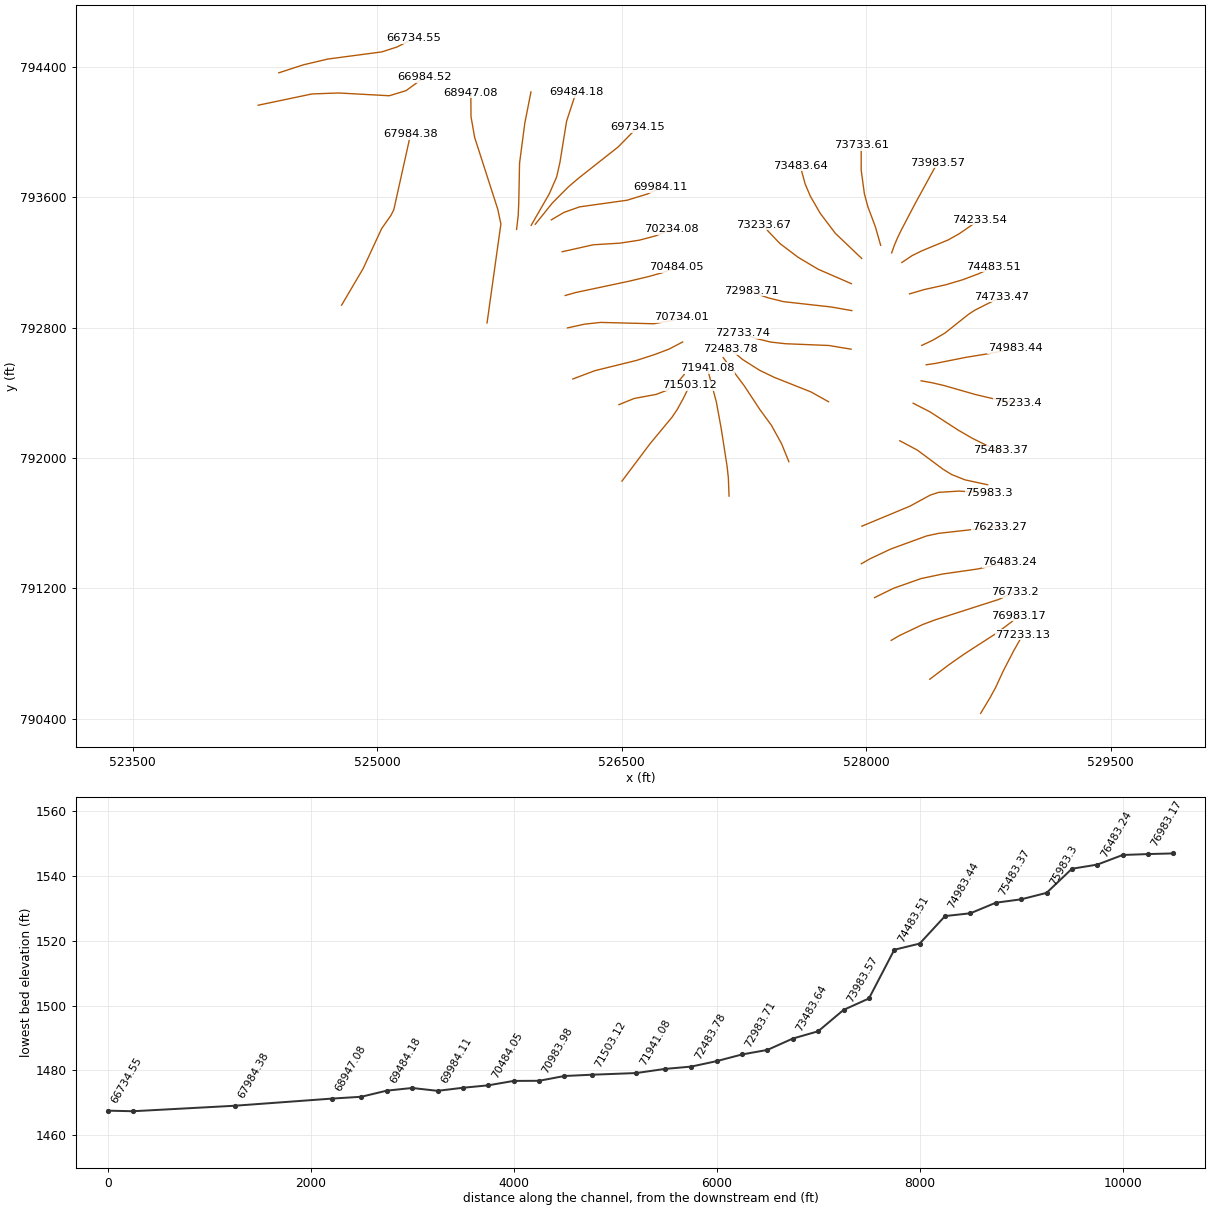
HEC-RAS study 5238_ras.prj: 5238

--- 5238_ras.g01 (geometry) --- (continued)

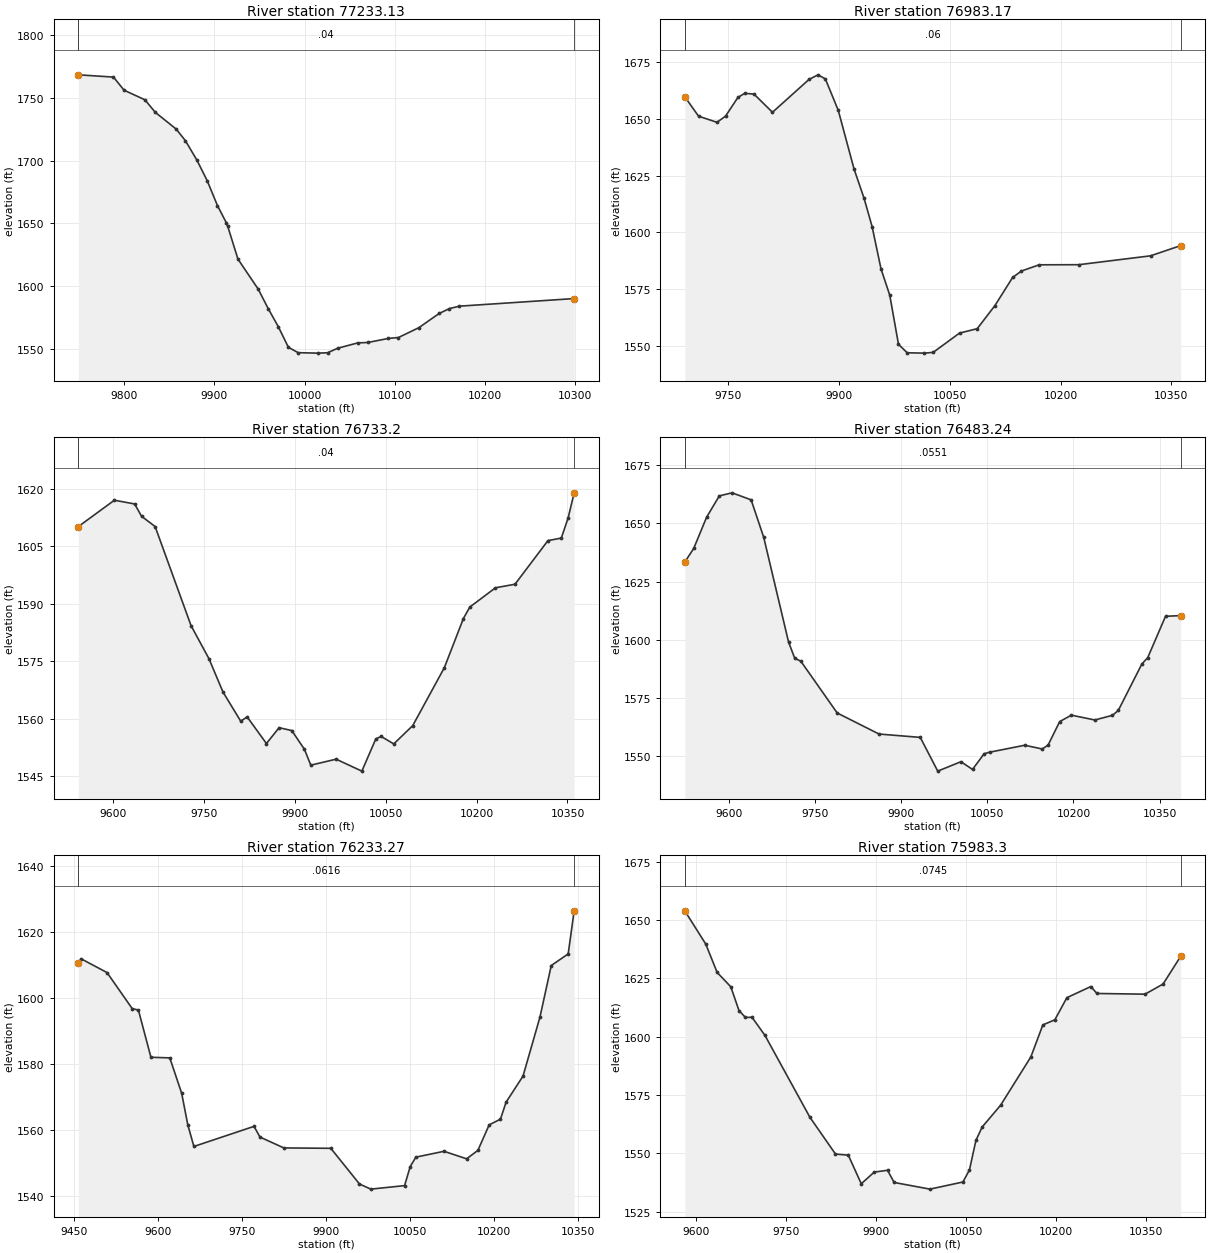
Type RM Length L Ch R = 1 ,77233.13,249.966200,249.966200,249.966200
XS GIS Cut Line= 6
528702.431709647790432.044412462528763.470859236790533.804193646
 528795.73143694 790593.45185345528841.702668768790693.270151181
528907.031050049790818.933770755528961.990441878790915.829210001
#Sta/Elev= 30
9749.1021768.1779788.0451766.3849799.7271755.9829822.8731748.3159834.4461738.315
9857.5921725.0069867.7811715.8039880.5091700.3429891.8781684.0759903.247 1664.26
9913.0361650.6629914.6161647.8839925.9851621.6539948.4791597.7429959.6381582.131
9970.7961567.8299981.9011551.5249992.6931547.24510014.231546.88210025.311547.155
 10036.41550.73510058.791555.01910070.061555.351 10092.61558.56210103.871559.296
10126.411567.08810148.961578.39410160.231582.269 10171.51584.228 10298.61590.266
#Mann= 3 , 0 , 0
9749.102    0.04       09749.102    0.04       0 10298.6    0.04       0
#XS Ineff= 2 , 0
       0                               0
Bank Sta=9749.102,10298.6
Exp/Cntr=0.3,0.1

Type RM Length L Ch R = 1 ,76983.17,249.966200,249.966200,249.966200
XS GIS Cut Line= 6
528390.292221255790641.514355724528505.685633094790728.777013144
528603.836358493790797.486880691528798.462063038790923.135235509
528889.496952021790991.182328703528936.012747342791031.818411548
#Sta/Elev= 30
9691.0321659.872 9709.661651.2959734.698 1648.599746.326 1651.369762.947 1659.56
9772.2561661.3969784.7751661.0399809.814 1653.029859.2871667.5219871.4941669.557
9881.4361667.7489898.8731653.9099920.3211627.9399933.7481615.1669944.735 1602.57
9956.8931583.7829968.6811572.247 9980.471550.5859992.2581546.831 10015.71546.678
10027.421547.00910063.141555.51710087.131557.47310111.111567.66610135.091580.084
10147.081582.93710171.071585.67610224.711585.72210321.89 1589.6410362.66 1594.14
#Mann= 3 , 0 , 0
9691.032    0.06       09691.032    0.06       010362.66    0.06       0
#XS Ineff= 2 , 0
       0                               0
Bank Sta=9691.032,10362.66
Exp/Cntr=0.3,0.1

Type RM Length L Ch R = 1 , 76733.2,249.966200,249.966200,249.966200
XS GIS Cut Line= 6
  528153.5724068790879.948907827528204.230088101790909.591263123
528345.831149283790976.791650102528423.375267327791005.906683649
528811.677871236791130.603855273528913.927463357791176.599717717
#Sta/Elev= 30
9542.5911610.1139602.1461616.9859635.5641616.0049646.9241612.8059669.3141610.128
9728.7211584.2759758.0761575.7319781.4281566.9879810.5961559.4189821.2781560.522
9853.0661553.5889873.9881557.716 9894.911556.9689915.8321552.0759926.2931547.951
9968.1371549.51110010.571546.398 10033.61554.78910042.341555.44310063.261553.493
10094.561558.25710146.741573.35110178.171586.15410188.771589.14510231.161594.169
10263.33 1595.0910317.721606.45910339.761607.11410350.981612.325   103611618.908
#Mann= 3 , 0 , 0
9542.591    0.04       09542.591    0.04       0   10361    0.04       0
#XS Ineff= 2 , 0
       0 9858.73                       0
Bank Sta=9542.591,10361
Exp/Cntr=0.3,0.1

Type RM Length L Ch R = 1 ,76483.24,249.966200,249.966200,249.966200
XS GIS Cut Line= 6
528051.449024443791142.551891035528167.876502167791199.564652126
528337.471266294791259.430704912  528469.5608413791287.306152474
528685.961408931791318.331962334528880.509216833791361.282514849
#Sta/Elev= 30
9523.8291633.3899539.3781639.2549561.7611652.6759583.9021661.8649606.0431663.175
9639.2551660.1539661.1951643.9739704.3451598.9889715.0751591.9989725.7051590.732
9789.0241568.4349861.7921559.3899933.4971557.9449963.926 1543.4310004.261547.488
10024.421544.16210044.581550.90310054.66  1551.610115.281554.56610145.691552.965
10155.831554.605 10176.11564.74710196.43 1567.5110237.211565.43610267.811567.433
   102781569.52410318.981589.48310329.291592.28110360.211610.04810386.491610.348
#Mann= 3 , 0 , 0
9523.829  0.0551       09523.829  0.0551       010386.49  0.0551       0
#XS Ineff= 2 , 0
       0                               0
Bank Sta=9523.829,10386.49
Exp/Cntr=0.3,0.1

Type RM Length L Ch R = 1 ,76233.27,249.966200,249.966200,249.966200
XS GIS Cut Line= 6
527970.696605557791350.200968195528024.449471454791381.034617651
528151.870620277791441.007984188528371.109029821791520.894705482
528444.009770578791536.695183483528815.577157271791578.729412084
#Sta/Elev= 30
9457.6241610.6219462.7061611.8159508.8211607.6729553.7091596.783 9564.871596.302
9587.1911582.0379620.8421581.8569642.0351571.1659652.966 1561.639663.8481555.059
9771.1841561.1419781.827  1557.99824.4011554.6179908.2411554.5029959.4111543.703
  9979.61542.15310039.861543.21710049.911548.94410059.951551.82910110.251553.597
10150.551551.32610170.691553.86210190.841561.59810210.991563.31610221.061568.468
10251.281576.353 10281.51594.20110301.651609.79810331.871613.30910342.521626.343
#Mann= 3 , 0 , 0
9457.624  0.0616       09457.624  0.0616       010342.52  0.0616       0
#XS Ineff= 2 , 0
       0                               0
Bank Sta=9457.624,10342.52
Exp/Cntr=0.3,0.1

Type RM Length L Ch R = 1 , 75983.3,249.966200,249.966200,249.966200
XS GIS Cut Line= 6
527973.871433204 791580.88246524528268.079465109791703.335761751
528391.752799169791770.717823325528443.763977215791788.240086823
528568.426424701791796.165938244 528754.15690259791784.415846393
#Sta/Elev= 30
9581.619 1653.999616.5321639.7479635.4991627.5849658.2551621.4439671.8851611.263
9682.7191608.2769693.5541608.3969715.2231600.5919790.0121565.5419832.7141549.744
9854.0651549.2669875.6491537.021 9897.251542.0139919.3641542.7959930.467 1537.57
9990.1111534.71710045.031537.77210055.871542.91210066.691555.59810077.061561.323
10107.881570.69810158.221591.37510178.221605.09510198.221607.28410218.231616.768
10258.26 1621.5510268.271618.56610348.461618.27310378.541622.61310407.77 1634.46
#Mann= 3 , 0 , 0
9581.619  0.0745       09581.619  0.0745       010407.77  0.0745       0
#XS Ineff= 2 , 0
       0                               0
Bank Sta=9581.619,10407.77
Exp/Cntr=0.3,0.1

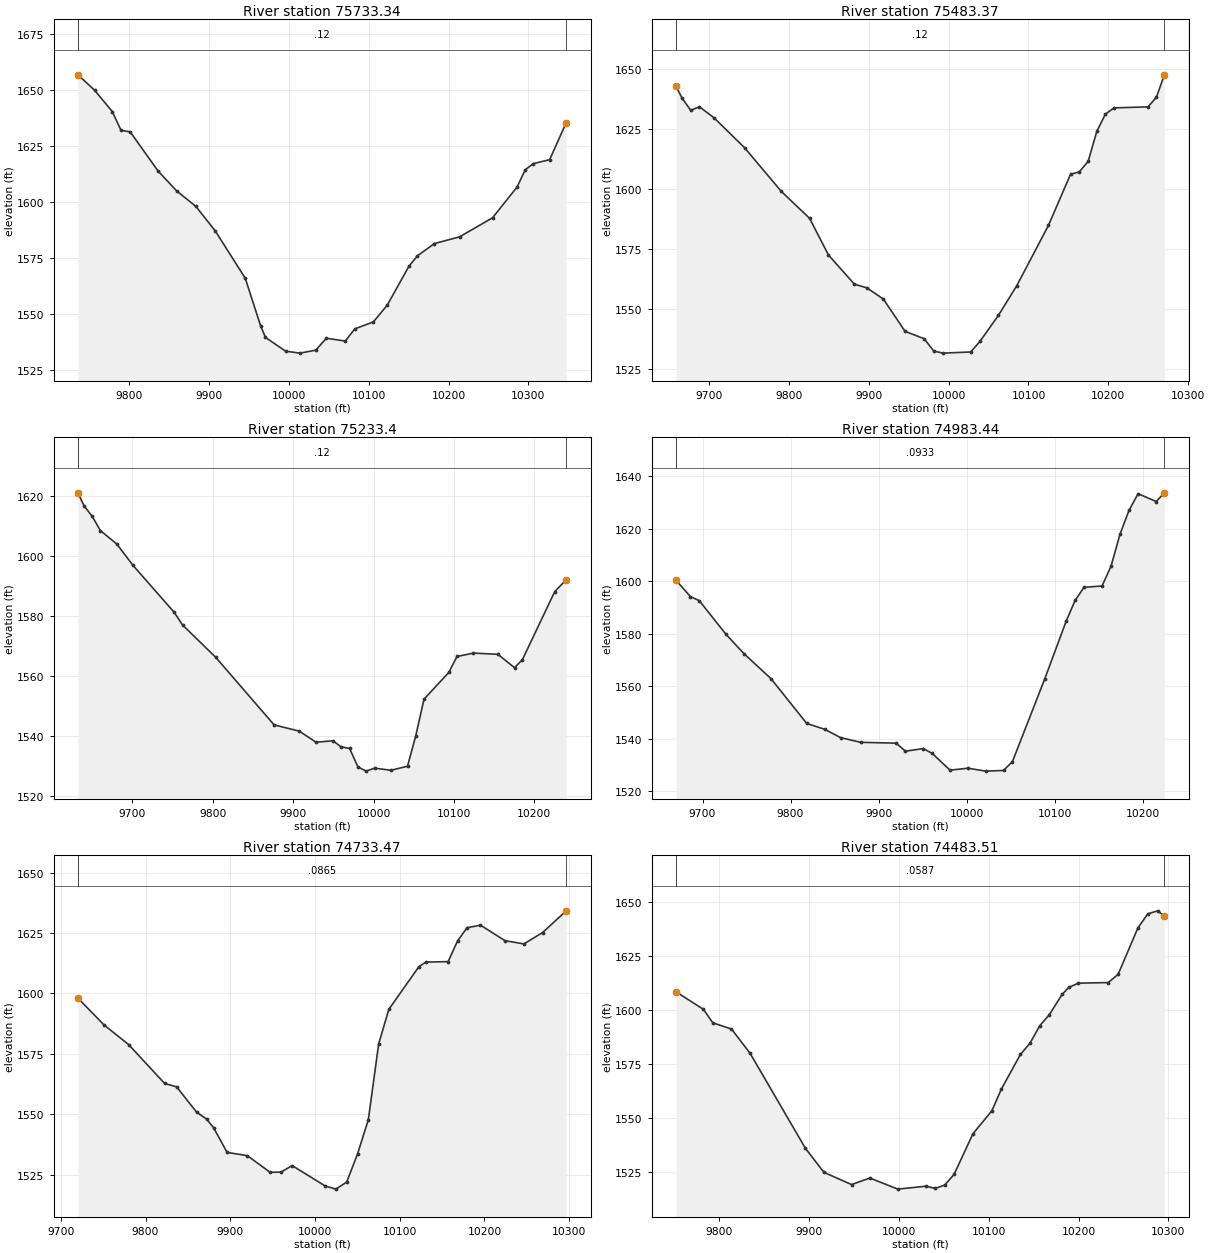
Type RM Length L Ch R = 1 ,75733.34,249.966200,249.966200,249.966200
XS GIS Cut Line= 6
528206.198100816792105.181163541528315.017007235 792047.05586164
528472.009186269 791930.08779185528524.480685705791897.749953615
528607.283872795791864.886901447528745.554367082791835.034183734
#Sta/Elev= 30
9735.6151656.6259756.4361649.7859778.5841640.2899789.6581631.8799801.0481631.242
9835.8711613.8689859.1061605.0039883.419 1598.039907.7541587.0879945.2471566.055
9964.5991544.7419970.5771539.7179995.9071533.58510013.681532.733 10033.61534.057
 10046.81539.36410070.521538.10310082.52 1543.5410105.721546.62510123.181554.124
10150.221571.37410160.991576.06410182.181581.50310213.76  1584.510255.061592.989
10285.841606.68510296.031614.37310306.231617.10410326.581618.84810347.361635.339
#Mann= 3 , 0 , 0
9735.615    0.12       09735.615    0.12       010347.36    0.12       0
#XS Ineff= 2 , 0
       0                               0
Bank Sta=9735.615,10347.36
Exp/Cntr=0.3,0.1

Type RM Length L Ch R = 1 ,75483.37,249.966200,249.966200,249.966200
XS GIS Cut Line= 6
528288.375957129792335.279161197528390.572235572792282.984023172
528565.345654534792170.014601269528649.562100444792121.183532302
528739.512002059792076.424213804528824.441877061792045.400877003
#Sta/Elev= 30
9658.8251642.7059666.1041637.8739677.0921632.704 9688.081634.206 9706.621629.507
9744.5871617.1259790.6611598.9449825.9521587.7639849.5621572.5219882.0641560.355
9897.5031558.8699918.3471554.1739945.4441540.7689969.4151537.663  9981.41532.553
9992.9851531.68310027.651532.16710039.211536.55310062.331547.38210085.331559.732
10125.021584.84410152.611606.06510163.651607.11310174.691611.45910185.561623.981
 10196.31631.09810207.041633.72710249.691634.147 10260.21638.15710270.13 1647.48
#Mann= 3 , 0 , 0
9658.825    0.12       09658.825    0.12       010270.13    0.12       0
#XS Ineff= 2 , 0
       0                               0
Bank Sta=9658.825,10270.13
Exp/Cntr=0.3,0.1

Type RM Length L Ch R = 1 , 75233.4,249.966200,249.966200,249.966200
XS GIS Cut Line= 6
 528337.56290489792473.002614918528403.454569211792461.112097659
528476.142558045792444.432983172 528672.74078316792388.111431653
 528805.33335231792356.920328901 528929.14704745792338.183875732
#Sta/Elev= 30
9632.1451621.0839639.6721616.775 9649.841613.2759660.0081608.5339680.3431604.078
9700.692 1596.929751.9921581.2759762.251  1577.1 9803.571566.3169876.2791543.816
9907.563 1541.759928.4191538.0489949.2761538.5399959.7041536.5189970.1321535.982
9980.5331529.8299990.8431528.43310001.151529.41910021.681528.72110042.211530.062
10052.481540.18110062.741552.37710093.541561.28410103.811566.59710124.241567.729
10154.711567.31910175.371562.88410185.121565.52310225.481588.23310239.691592.145
#Mann= 3 , 0 , 0
9632.145    0.12       09632.145    0.12       010239.69    0.12       0
#XS Ineff= 2 , 0
       0                               0
Bank Sta=9632.145,10239.69
Exp/Cntr=0.3,0.1

Type RM Length L Ch R = 1 ,74983.44,249.966200,249.966200,249.966200
XS GIS Cut Line= 6
528368.906362008792571.275306454528424.672314701792579.567324943
528614.609368726792617.330710223528750.506294898792639.336693068
528824.401335937 792653.02754267528914.135106386 792672.81875261
#Sta/Elev= 30
9669.9951600.3329686.2661594.1449696.3761592.5689726.7081579.741  9747.11572.371
9777.6871562.872 9818.471545.7399838.8621543.5219856.7961540.3599879.6441538.564
9920.0291538.2359930.5581535.1699950.8241536.1799960.9571534.3249981.2231527.929
10001.491528.68410021.741527.56710041.991527.82210052.121531.20210088.781562.694
10113.121584.71810123.291592.65110133.461597.67310153.941598.18510164.181605.772
10174.421618.04610184.661627.096 10194.9 1633.3910215.381630.40810224.74 1633.72
#Mann= 3 , 0 , 0
9669.995  0.0933       09669.995  0.0933       010224.74  0.0933       0
#XS Ineff= 2 , 0
       0                               0
Bank Sta=9669.995,10224.74
Exp/Cntr=0.3,0.1

Type RM Length L Ch R = 1 ,74733.47,249.966200,249.966200,249.966200
XS GIS Cut Line= 6
528340.872835205792689.928838489528407.845155567792721.230490039
528484.559970601792766.663936776528627.324432977792880.283539646
528665.419541181792905.456047678 528830.31060645792988.878342571
#Sta/Elev= 30
9720.2431598.0639751.1721586.9449780.0171578.884 9822.481562.8079836.7171561.368
9860.1561550.9589872.0331548.0619880.3031544.481 9896.281534.2639920.0351532.948
9947.0091526.0379959.9991526.1319972.9881528.839 10011.81520.42610024.581519.087
10037.361522.00110050.151533.60710062.931547.787 10075.11579.12110087.091593.426
10122.591611.08310130.821612.97110157.061613.17310168.25 1621.7410179.431627.193
10195.241628.24510224.181621.83710246.511620.49410268.551625.19510296.441634.179
#Mann= 3 , 0 , 0
9720.243  0.0865       09720.243  0.0865       010296.44  0.0865       0
#XS Ineff= 2 , 0
       0                               0
Bank Sta=9720.243,10296.44
Exp/Cntr=0.3,0.1

Type RM Length L Ch R = 1 ,74483.51,249.966200,249.966200,249.966200
XS GIS Cut Line= 6
528266.113011076793006.354140671528355.099624697793032.494552214
528488.540824583793062.160757232528593.397694477793093.410846079
528691.429557811793130.313212263528781.764742127793171.920125987
#Sta/Elev= 30
9752.3361608.5169782.7131600.4129793.2291594.147 9813.951591.2959834.6571580.045
9896.2331536.0429916.7211524.9749947.4531519.2969967.9421522.3189998.9141517.182
10030.24 1518.5410040.681517.49410051.131519.08510061.571524.00810082.46 1542.77
10103.531553.41410114.121563.47710135.321579.515   10146 1584.7310156.771592.784
10167.541597.95310181.681607.28610189.081610.55910199.931612.53710232.961612.797
10243.971616.57910265.991638.081   102771644.61610288.011646.01510295.461643.513
#Mann= 3 , 0 , 0
9752.336  0.0587       09752.336  0.0587       010295.46  0.0587       0
#XS Ineff= 2 , 0
       0                               0
Bank Sta=9752.336,10295.46
Exp/Cntr=0.3,0.1

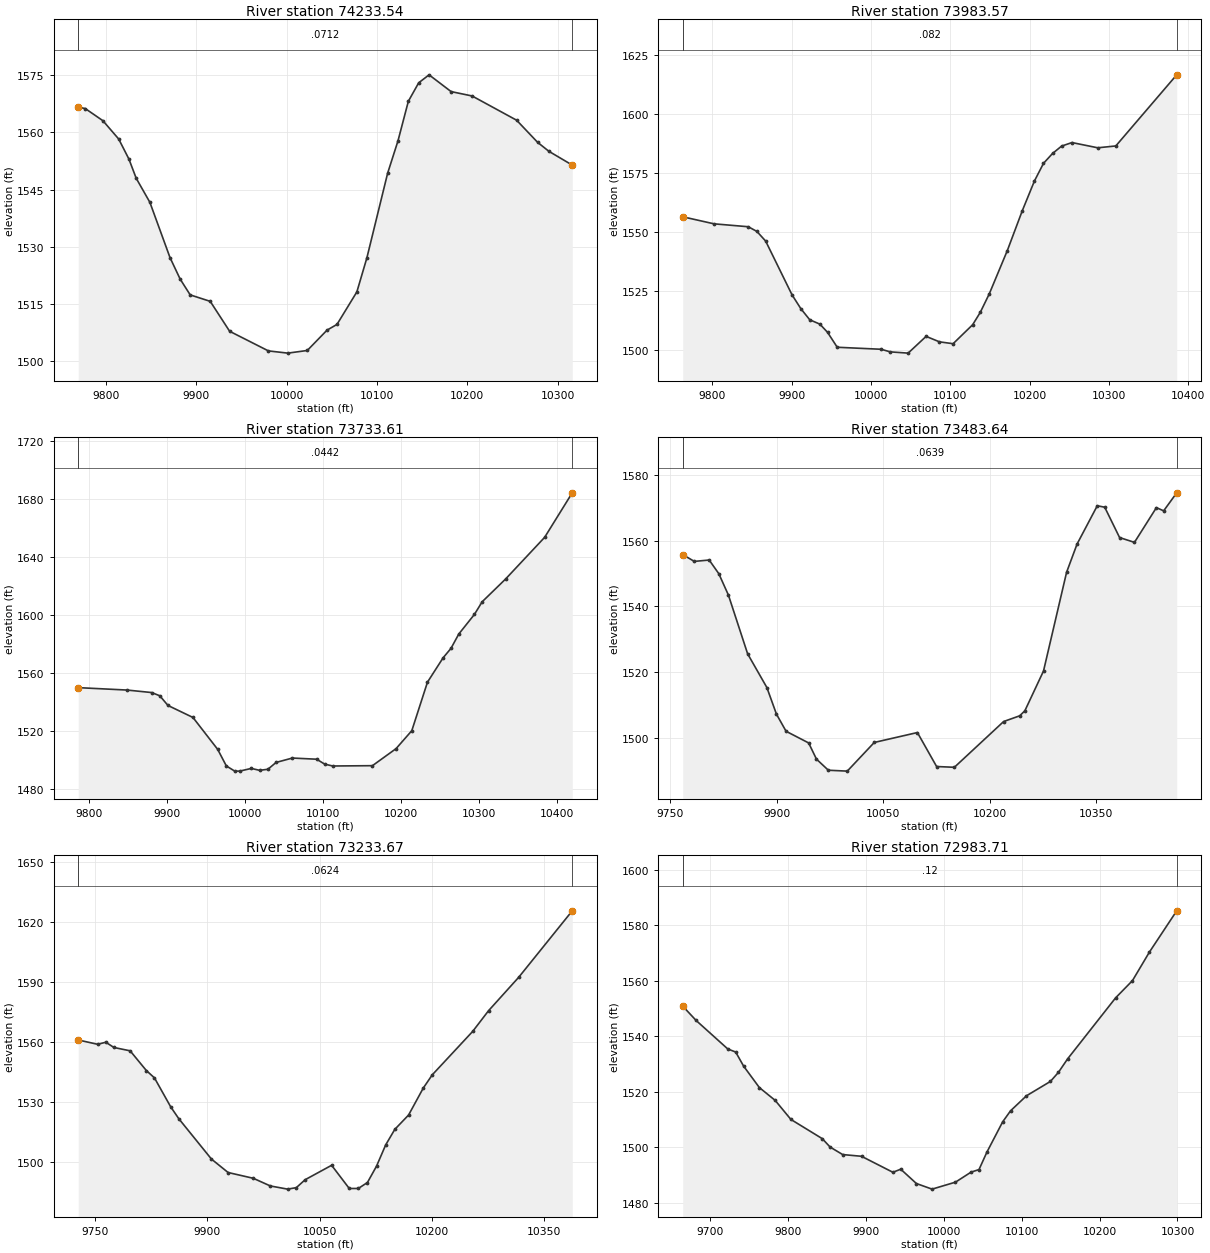
Type RM Length L Ch R = 1 ,74233.54,249.966200,249.966200,249.966200
XS GIS Cut Line= 6
528219.008509768793198.861344701 528281.78921908793240.948631844
528341.844939843793270.649863611528503.004542268793337.241390954
528571.636518467  793375.7630195528695.703549247793461.400213841
#Sta/Elev= 30
9769.465 1566.549777.1771566.2169796.7511563.0249814.2151558.2359825.5441552.979
9833.606 1547.959848.722 1541.669871.0351527.1659882.1911521.5729893.3471517.417
9915.5261515.7239936.9921507.8899979.9241502.74910001.391502.169 10022.91502.863
10044.771508.19110055.771509.68710077.771518.20210088.871527.134 10111.81549.267
10123.271557.75210134.741568.119 10146.21572.95410157.671575.03710182.031570.647
10205.281569.50110254.551563.15210277.761557.36310290.241555.01310316.091551.402
#Mann= 3 , 0 , 0
9769.465  0.0712       09769.465  0.0712       010316.09  0.0712       0
#XS Ineff= 2 , 0
       0                               0
Bank Sta=9769.465,10316.09
Exp/Cntr=0.3,0.1

Type RM Length L Ch R = 1 ,73983.57,249.966200,249.966200,249.966200
XS GIS Cut Line= 6
528156.451156939793257.843991674528173.258314824793304.917498738
528191.340337183793347.546934713528214.204213915793395.398207788
528297.655237279793554.890073377528438.291513465793812.382277752
#Sta/Elev= 30
9762.7941556.4449802.2161553.4539845.4671552.2169856.3291550.2259867.3561546.146
9900.6041523.3559911.6871517.4989922.9271512.7869935.728 1510.939945.4181507.445
9957.5881501.13110012.98 1500.2810024.311499.18410046.961498.64510069.611505.746
10086.481503.42610103.661502.63810128.321510.69210137.841515.87810149.231523.747
10172.021542.13410190.911559.04310206.21 1571.64 10217.61579.09210228.991583.271
10240.391586.39610253.491587.90210285.971585.68310308.761586.46110385.53 1616.61
#Mann= 3 , 0 , 0
9762.794   0.082       09762.794   0.082       010385.53   0.082       0
#XS Ineff= 2 , 0
       0                               0
Bank Sta=9762.794,10385.53
Exp/Cntr=0.3,0.1

Type RM Length L Ch R = 1 ,73733.61,249.966200,249.966200,249.966200
XS GIS Cut Line= 6
528089.028363749793304.450821547528057.000241216793416.714354485
528010.382588084793541.827497129527989.105688498793620.689578685
527969.436308847793766.543255591527969.598062295793920.353263529
#Sta/Elev= 30
9786.6591549.6789849.3291548.0089880.7231546.2969891.1881544.0639901.6531537.387
9933.7051529.094 9965.391507.0879976.4951495.6439987.1921492.0869993.5461492.061
10008.521493.92710019.121492.61210029.731493.33610040.281498.06510061.151501.092
10092.261500.28210102.541496.89410112.831495.60310163.771495.82210194.061507.587
10214.221519.979 10234.31553.45810254.38  1570.310264.421576.76610274.441586.673
10294.461600.21210304.471608.96810334.471624.66710384.491653.40910419.881684.127
#Mann= 3 , 0 , 0
9786.659  0.0442       09786.659  0.0442       010419.88  0.0442       0
#XS Ineff= 2 , 0
       0                               0
Bank Sta=9786.659,10419.88
Exp/Cntr=0.3,0.1

Type RM Length L Ch R = 1 ,73483.64,249.966200,249.966200,249.966200
XS GIS Cut Line= 6
527972.535355537793223.972127288527810.692040947 793378.15119679
527718.618685863793499.835590075527657.122873798793606.239346459
527625.675745654793680.701025894527594.965726768793792.981744917
#Sta/Elev= 30
9767.3641555.7879783.6961553.7019804.6931554.123 9818.251549.9649831.8071543.451
9858.9211525.5439886.0351515.2829899.5921507.1519913.1491501.9519944.9531498.402
9955.9511493.4749972.7251490.0879999.4221489.81410037.471498.548 10098.3 1501.57
10125.381491.21510150.431490.983 10219.91504.92410242.551506.66410249.811508.191
10276.111520.30610308.67 1550.3910323.461558.99710351.94 1570.6510362.421570.213
 10383.41560.96710404.371559.50110435.31 1570.0810445.551569.10710463.951574.591
#Mann= 3 , 0 , 0
9767.364  0.0639       09767.364  0.0639       010463.95  0.0639       0
#XS Ineff= 2 , 0
       0                               0
Bank Sta=9767.364,10463.95
Exp/Cntr=0.3,0.1

Type RM Length L Ch R = 1 ,73233.67,249.966200,249.966200,249.966200
XS GIS Cut Line= 6
527908.999274051793069.102008422 527705.03106912793157.760736608
527582.335360294793230.926019414527471.429116931793314.677584018
527397.569084223 793392.19370652527369.354439716793431.772468277
#Sta/Elev= 30
9727.4951560.9029753.5031558.741 9764.341559.7819775.177 1557.159796.8511555.486
9818.5251545.6229829.3631541.9469851.0371527.4859861.8741521.5349905.5191501.344
 9927.761494.626 9961.431491.7349984.2861487.89210007.261486.31110018.961487.052
10030.761491.02610066.141498.23410089.721486.62610101.811486.639   101141489.625
10126.191497.82310138.381508.42210150.581516.19810168.981523.36910188.691536.902
10200.711543.49810254.661565.19210275.831575.52710316.181592.26310387.731625.502
#Mann= 3 , 0 , 0
9727.495  0.0624       09727.495  0.0624       010387.73  0.0624       0
#XS Ineff= 2 , 0
       0                               0
Bank Sta=9727.495,10387.73
Exp/Cntr=0.3,0.1

Type RM Length L Ch R = 1 ,72983.71,249.966200,249.966200,249.966200
XS GIS Cut Line= 6
527911.826377404792903.716462038527784.546600961792925.963666841
527492.909322526792958.660828564527396.589108653792982.727242063
527359.675534264792995.617298538 527293.85177297 793026.44236257
#Sta/Elev= 30
9664.9421550.901 9682.151545.7259722.8271535.4439732.9551534.3379743.0841529.275
9763.3411521.5279783.5971516.916  9803.81510.0419844.0851503.1079854.1561500.079
9870.2541497.3789894.4421496.7539934.7271490.9889944.7981492.0999964.9411486.925
9985.0171484.91410015.051487.42710035.121491.05610045.241491.96110055.36 1498.24
10075.591509.15810085.711513.14310106.171518.56910136.891523.74210147.221527.023
 10158.91531.85110220.611553.88510242.211560.09210263.971570.38110299.011585.254
#Mann= 3 , 0 , 0
9664.942    0.12       09664.942    0.12       010299.01    0.12       0
#XS Ineff= 2 , 0
       0                               0
Bank Sta=9664.942,10299.01
Exp/Cntr=0.3,0.1

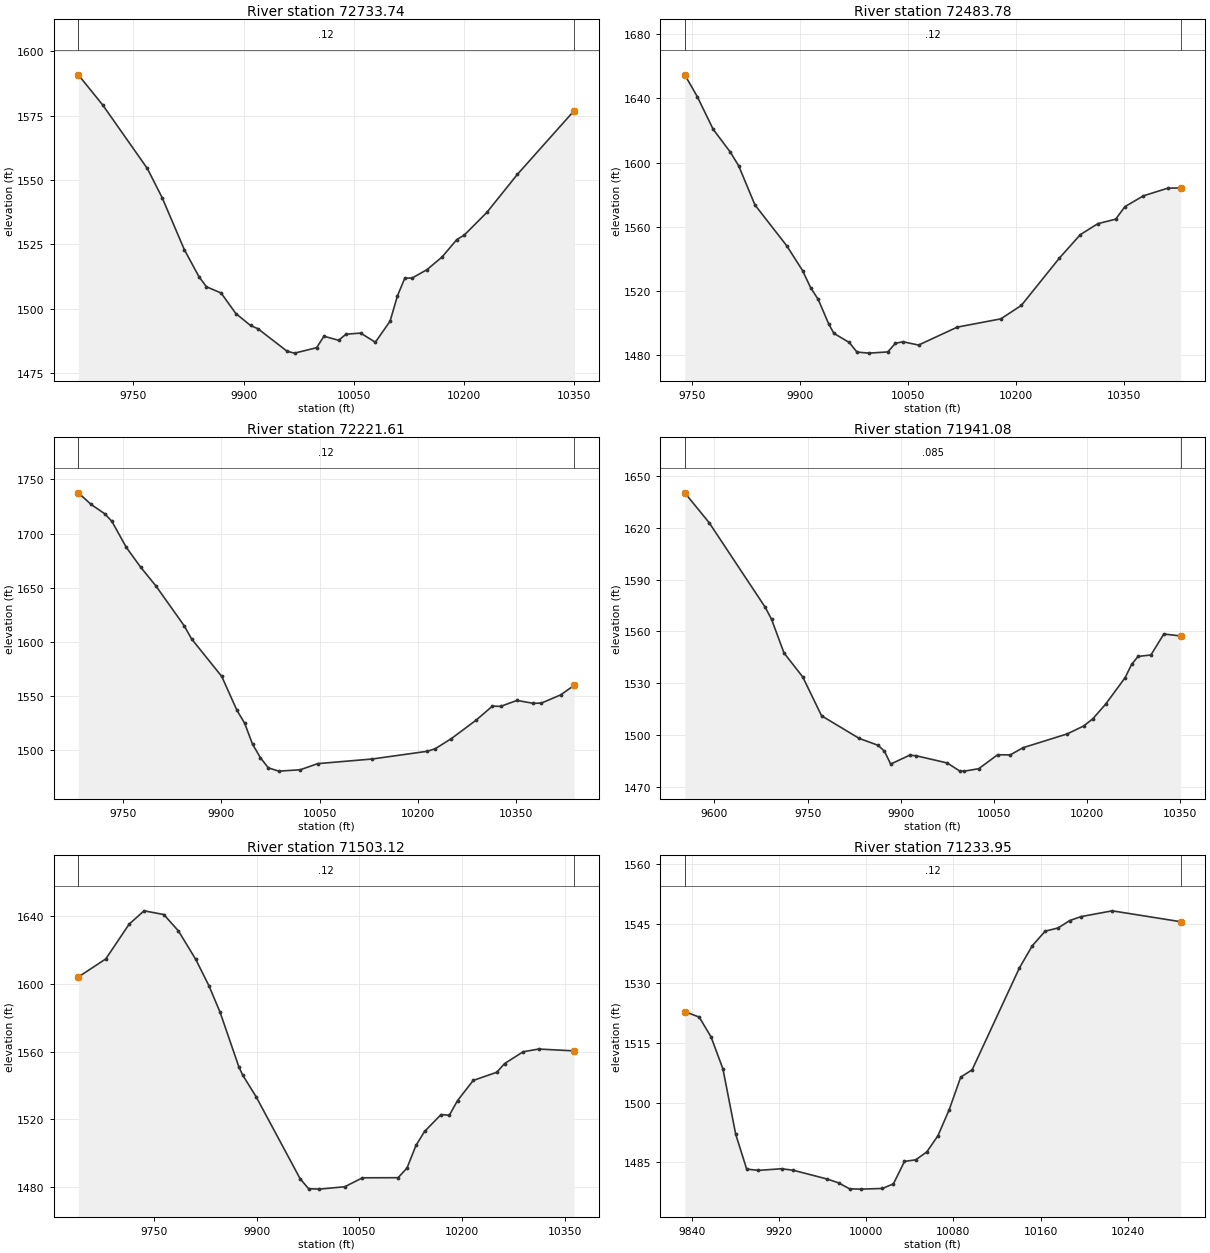
Type RM Length L Ch R = 1 ,72733.74,249.966200,249.966200,249.966200
XS GIS Cut Line= 6
 527907.42865594792666.839330812527771.431977523792689.584899362
527504.603923776792700.433756019527414.889547427792710.443542806
527314.562117846792734.880580743527243.377979865792763.809369161
#Sta/Elev= 30
9674.8481590.8229708.0221579.1449768.8471554.4939789.0281543.197 9819.261523.016
9839.3191512.4769849.3491508.6219869.4081506.1699889.4681498.2249909.5271493.575
9919.5351492.3299959.5411483.5389969.5421482.8559999.5461484.96110009.551489.402
10029.551487.84210039.561490.19610059.561490.62610079.571487.08510099.64 1495.25
10109.68 1505.0710119.711511.92110129.761512.00210149.961515.24510170.161520.061
10190.581526.89410200.791528.66310231.531537.44710273.141552.20910350.491576.921
#Mann= 3 , 0 , 0
9674.848    0.12       09674.848    0.12       010350.49    0.12       0
#XS Ineff= 2 , 0
       0                               0
Bank Sta=9674.848,10350.49
Exp/Cntr=0.3,0.1

Type RM Length L Ch R = 1 ,72483.78,262.166700,262.166700,262.166700
XS GIS Cut Line= 6
527769.470453024792344.347002412527661.241850098792404.658576424
527436.815818592792493.816146013527346.931150974 792536.91663752
 527241.42078992792603.874858728 527166.20421661  792667.3421651
#Sta/Elev= 30
9740.541 1654.699757.9471641.0489779.9251620.7629803.9931606.368 9815.471597.893
9837.9661573.5929882.266 1548.059904.0831532.6859915.466 1521.899925.8991514.657
9940.4981499.3399947.6731493.4949969.0531487.8179979.7421481.8249996.4291481.176
 10022.51481.92810033.19 1487.3410043.891488.25610065.271486.20210119.051497.396
10179.591502.54310208.061510.92710260.981540.47210290.091555.09510314.371561.896
 10339.11564.69610351.94  1572.510377.63 1579.2510411.311583.99810429.331584.202
#Mann= 3 , 0 , 0
9740.541    0.12       09740.541    0.12       010429.33    0.12       0
#XS Ineff= 2 , 0
       0                               0
Bank Sta=9740.541,10429.33
Exp/Cntr=0.3,0.1

Type RM Length L Ch R = 1 ,72221.61,280.526400,280.526400,280.526400
XS GIS Cut Line= 6
527525.584058331791976.650013717527481.066100683792086.470590798
527417.980494642792200.624802771527348.066093213792296.253302893
527251.003079143 792443.37616179 527122.64143164792615.058822742
#Sta/Elev= 30
 9681.191737.6459700.6991726.9369721.9611718.1169732.5921711.2099754.4061687.388
9776.2811669.1039799.7641651.6499843.1111614.7429854.3621602.6459900.5391567.921
9923.7191536.6799935.5181524.7399947.5861505.3169959.6531492.8199971.721 1483.49
 9987.731480.44310020.651481.70510047.181487.37210130.451491.64310214.861498.785
10227.051501.17310251.741510.55510289.491527.56710314.461540.53910326.951540.278
10351.931545.786 10376.91543.10410389.391543.348 10418.71550.87610439.391559.735
#Mann= 3 , 0 , 0
 9681.19    0.12       0 9681.19    0.12       010439.39    0.12       0
#XS Ineff= 2 , 0
       0                               0
Bank Sta=9681.19,10439.39
Exp/Cntr=0.3,0.1

Type RM Length L Ch R = 1 ,71941.08,437.963900,437.963900,437.963900
XS GIS Cut Line= 6
527158.630856994  791765.5797791527154.322778805791877.790401254
527146.457284713791949.139679556527110.555000167792180.028014897
527080.686270511792343.336385487527025.046014547792551.085437429
#Sta/Elev= 30
9552.179 1640.219591.6271622.8389681.8281573.9539691.8881567.098 9712.011547.581
9742.2261533.6739772.5871511.2049833.308  1498.19863.6681494.1229873.7891490.747
9883.909 1483.269914.2691488.3679924.3891488.1229975.0041483.9099995.301 1479.21
10002.561479.18210025.761480.58710056.241488.65810076.551488.56210096.921492.708
10168.531500.74710195.01 1505.3410209.791509.52410230.561518.07210261.71  1533.3
10272.091540.92510282.471545.53710303.241546.407   103241558.51310351.09 1557.41
#Mann= 3 , 0 , 0
9552.179   0.085       09552.179   0.085       010351.09   0.085       0
#XS Ineff= 2 , 0
       0                               0
Bank Sta=9552.179,10351.09
Exp/Cntr=0.3,0.1

Type RM Length L Ch R = 1 ,71503.12,269.174000,269.174000,269.174000
XS GIS Cut Line= 6
526501.461953315791857.388685597526673.851823135792086.853309695
526809.914284879792251.030314563   526839.809058792295.570164195
526877.803184126792364.324823565526917.647363483792445.976493257
#Sta/Elev= 30
9639.934 1604.079680.0111614.7549714.0631635.3139735.8281643.1729764.6011640.991
9785.9671631.2869811.1781614.5059830.301 1599.039846.7261583.2169874.206 1550.85
9879.5751546.1689899.4171533.1839963.4891484.819 9975.841478.9049991.5321478.664
 10028.5 1480.0610054.471485.357 10106.41485.42410119.391491.12810132.491504.493
10144.98 1512.7410169.071522.73510181.111522.32810193.161531.03110216.041542.927
10250.321547.73510261.741552.86810288.81 1559.8610311.611561.47310363.25 1560.38
#Mann= 3 , 0 , 0
9639.934    0.12       09639.934    0.12       010363.25    0.12       0
#XS Ineff= 2 , 0
       0                               0
Bank Sta=9639.934,10363.25
Exp/Cntr=0.3,0.1

Type RM Length L Ch R = 1 ,71233.95,249.966200,249.966200,249.966200
XS GIS Cut Line= 6
526482.892881037792326.545856261 526576.56600703 792364.43887528
526711.533586949792389.566055131526774.907622613792413.739985633
526843.520411887792463.697281772526883.648455405792511.805349273
#Sta/Elev= 30
 9833.771522.9039846.9521521.545 9857.841516.5559868.7271508.5029880.4351492.074
9890.502 1483.319901.2191482.9899922.5291483.3979933.1851483.0239964.4331480.799
9974.6881479.8559984.8461478.3519994.9091478.27210014.971478.44210025.011479.598
10035.181485.24510045.411485.63910055.641487.62810065.881491.72510076.211498.291
10086.711506.42710097.221508.29110140.591533.93610152.381539.49210164.161543.156
10175.951543.93710186.621545.81210197.051546.80810225.61 1548.2610288.331545.525
#Mann= 3 , 0 , 0
 9833.77    0.12       0 9833.77    0.12       010288.33    0.12       0
#XS Ineff= 2 , 0
       0                               0
Bank Sta=9833.77,10288.33
Exp/Cntr=0.3,0.1

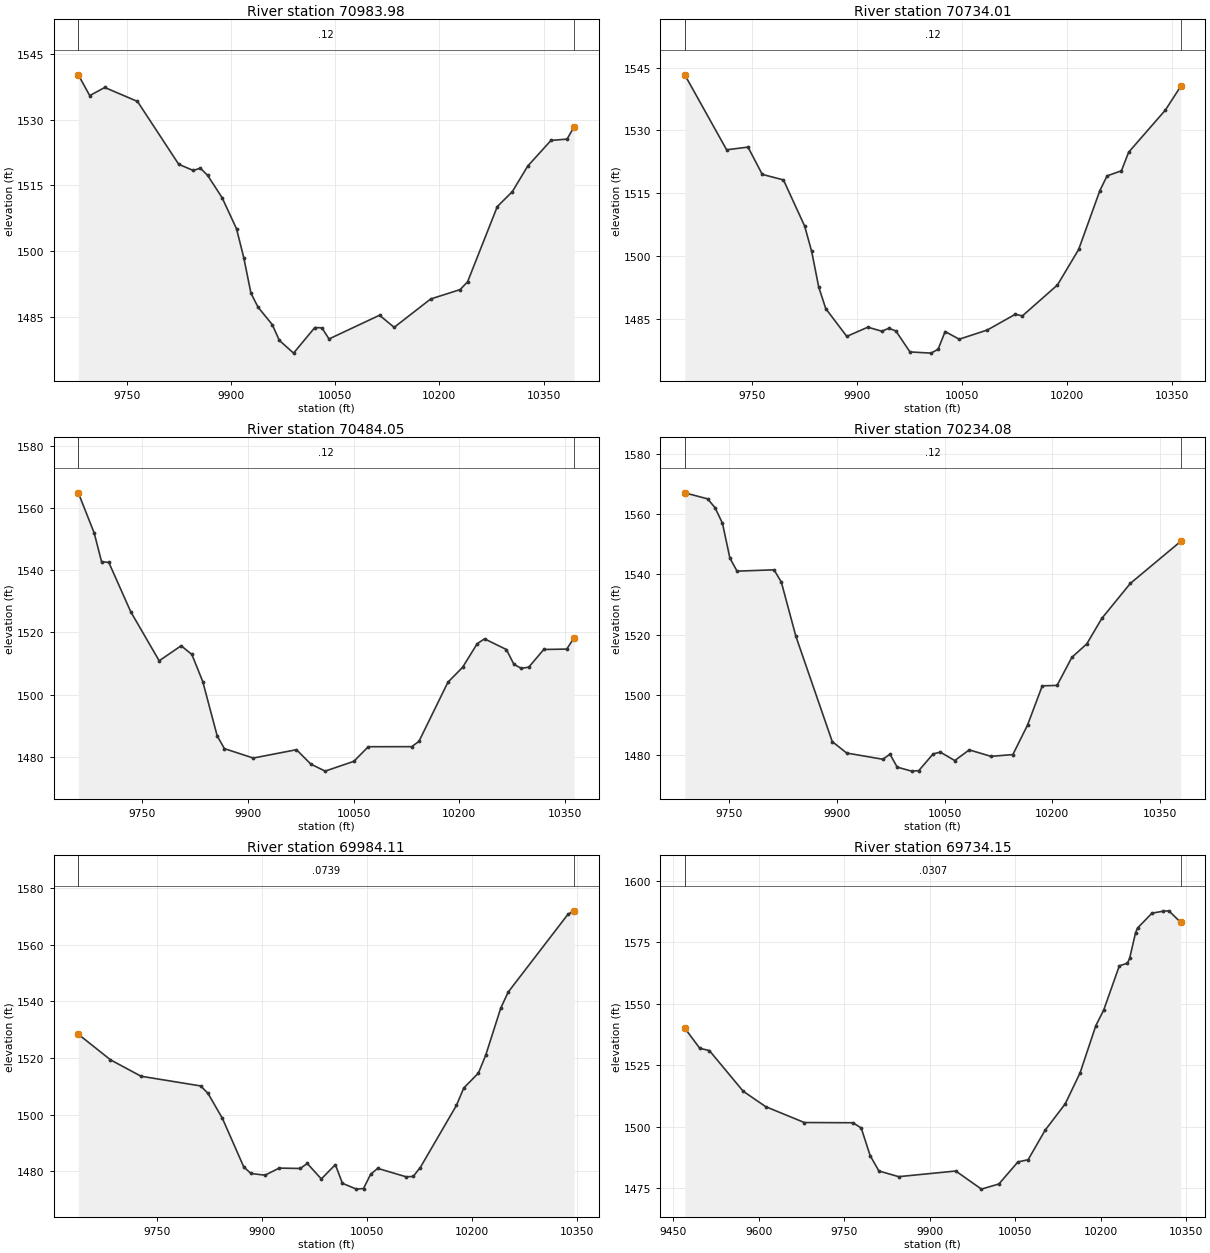
Type RM Length L Ch R = 1 ,70983.98,249.966200,249.966200,249.966200
XS GIS Cut Line= 6
526199.867006978792483.996419855526334.620792324792534.871651103
526590.114256684792597.870323589526702.381381616792634.070189105
526791.255599217792667.760092074526873.683232127792711.109814954
#Sta/Elev= 30
9680.4891540.2029696.881 1535.479718.545 1537.329765.6121534.1419824.9631519.821
 9845.761518.4189856.1591518.9229866.5581517.2969887.3551512.2219908.1531505.129
9918.5521498.5739928.9081490.4529939.1331487.2719959.5831483.2959969.8081479.693
9990.2581476.79310020.871482.62810031.07 1482.5510041.271480.02110114.011485.427
10135.021482.66910187.561489.12610230.011491.274 10240.71493.04510283.481510.188
10305.031513.57210327.291519.41710360.671525.24810383.921525.56310394.091528.378
#Mann= 3 , 0 , 0
9680.489    0.12       09680.489    0.12       010394.09    0.12       0
#XS Ineff= 2 , 0
       0                               0
Bank Sta=9680.489,10394.09
Exp/Cntr=0.3,0.1

Type RM Length L Ch R = 1 ,70734.01,249.966200,249.966200,249.966200
XS GIS Cut Line= 6
526167.109909954792797.392021848526270.611861359 792820.26830897
526369.766394895792831.188392671526696.038523125792823.005148177
526807.800411805792842.950343749526865.205789936792863.543811634
#Sta/Elev= 30
9654.5551543.2519714.2011525.3419744.7241525.9819765.035 1519.479795.3011518.138
9825.5171507.116 9835.551501.0579845.5821492.5689855.6141487.3949885.6411480.759
9915.6531482.9569935.6571481.992 9945.661482.7029955.6891482.0479975.7471477.045
10005.851476.75610015.891477.67210025.931481.916   100461480.08310086.061482.276
10126.091486.045 10136.11485.64910186.141493.037 10216.41501.52510246.671515.594
 10256.91519.10310277.431520.32710287.691524.756 10340.1 1534.8310361.861540.468
#Mann= 3 , 0 , 0
9654.555    0.12       09654.555    0.12       010361.86    0.12       0
#XS Ineff= 2 , 0
       0                               0
Bank Sta=9654.555,10361.86
Exp/Cntr=0.3,0.1

Type RM Length L Ch R = 1 ,70484.05,249.966200,249.966200,249.966200
XS GIS Cut Line= 6
526153.375260919792996.544432493526218.917845902 793014.93193789
526550.463090927793085.241010019526668.075835849793113.447813447
526751.230727851793136.945726806526834.843050844793169.195385233
#Sta/Elev= 30
9659.2261564.8159681.8111551.8699692.1711542.7269702.5321542.4389733.5411526.651
9774.0411510.8449805.2241515.6869820.4531512.8859835.9461504.1539856.4271486.696
9866.6681482.627 9907.63  1479.69968.9811482.2889989.3341477.665 10009.71475.399
10050.491478.55410070.92 1483.2410132.621483.26210142.911484.96810184.041503.972
10204.791508.73310225.571516.32510235.971517.90710267.141514.45910277.621509.752
10288.241508.40710298.871508.81510320.121514.48210352.741514.61110363.281518.255
#Mann= 3 , 0 , 0
9659.226    0.12       09659.226    0.12       010363.28    0.12       0
#XS Ineff= 2 , 0
       0                               0
Bank Sta=9659.226,10363.28
Exp/Cntr=0.3,0.1

Type RM Length L Ch R = 1 ,70234.08,249.966100,249.966100,249.966100
XS GIS Cut Line= 6
526134.866479432793264.921763643526324.753176046793307.558526062
526490.910175859 793317.82598343526609.663197136793336.270776572
526709.464078452793362.962814923526806.378903968793403.109914073
#Sta/Elev= 30
9688.4681567.0499720.185 1565.059730.6161562.0989740.9091556.9359751.2021545.407
9761.1861541.0479812.6811541.486 9822.821537.4169843.0981519.3969893.7051484.449
9913.8091480.6479964.0591478.586 9974.06 1480.269984.0621475.98510004.071474.644
10014.071474.79710034.091480.35710044.091480.95210064.221478.158 10084.41481.698
10114.67 1479.55 10145.11480.14810165.481489.92510186.011502.95610206.591503.111
10227.181512.41610248.051516.92110268.921525.36410308.541536.96510378.581550.908
#Mann= 3 , 0 , 0
9688.468    0.12       09688.468    0.12       010378.58    0.12       0
#XS Ineff= 2 , 0
       0                               0
Bank Sta=9688.468,10378.58
Exp/Cntr=0.3,0.1

Type RM Length L Ch R = 1 ,69984.11,249.966200,249.966200,249.966200
XS GIS Cut Line= 6
526067.990900298793460.419592197 526144.79555171793506.065739162
526242.097841804 793540.38792595526533.110342714793581.054077164
526658.097391309793619.462622221526739.879379582793659.203827207
#Sta/Elev= 30
9636.9921528.3629682.9661519.3369726.6381513.5419811.8791510.1199822.321  1507.5
9842.8881498.692 9873.481481.5279883.6741479.2259903.844 1478.629924.0131481.119
9954.1771480.9939964.2181482.7559984.2991477.29310004.381482.35710014.441475.762
10034.551473.701 10044.61473.911 10054.71478.88910064.851481.03610105.431478.058
10115.581478.17210125.761481.33410177.461503.26510187.91 1509.3910208.811514.648
 10219.41521.05610240.731537.561 10251.41543.23710336.881570.714 10345.71571.921
#Mann= 3 , 0 , 0
9636.992  0.0739       09636.992  0.0739       0 10345.7  0.0739       0
#XS Ineff= 2 , 0
       0                               0
Bank Sta=9636.992,10345.7
Exp/Cntr=0.3,0.1

Type RM Length L Ch R = 1 ,69734.15,249.966200,249.966200,249.966200
XS GIS Cut Line= 6
525969.678975102793433.685647619526073.641353496793563.283765867
 526170.47707382793660.927673424526235.350875011793716.462254254
526477.919352419793907.751517619526598.689351906794030.575969064
#Sta/Elev= 30
9469.9081540.008 9496.241531.8199513.0331530.9169572.4221514.3819612.0221508.094
9679.7991501.6549765.1871501.5639779.6621499.4439795.348 1488.229810.7251481.954
 9845.481479.646 9945.681481.942 9990.771474.57810021.471476.68710054.791485.626
10072.721486.53710102.691498.55410137.891509.24710163.941521.82510191.641541.037
10205.391547.329 10232.9 1565.3610247.061566.40310250.921568.35510261.461578.863
10264.821580.69210290.261586.77210309.461587.537 10319.91587.71210340.521583.051
#Mann= 3 , 0 , 0
9469.908  0.0307       09469.908  0.0307       010340.52  0.0307       0
#XS Ineff= 2 , 0
       0                               0
Bank Sta=9469.908,10340.52
Exp/Cntr=0.3,0.1

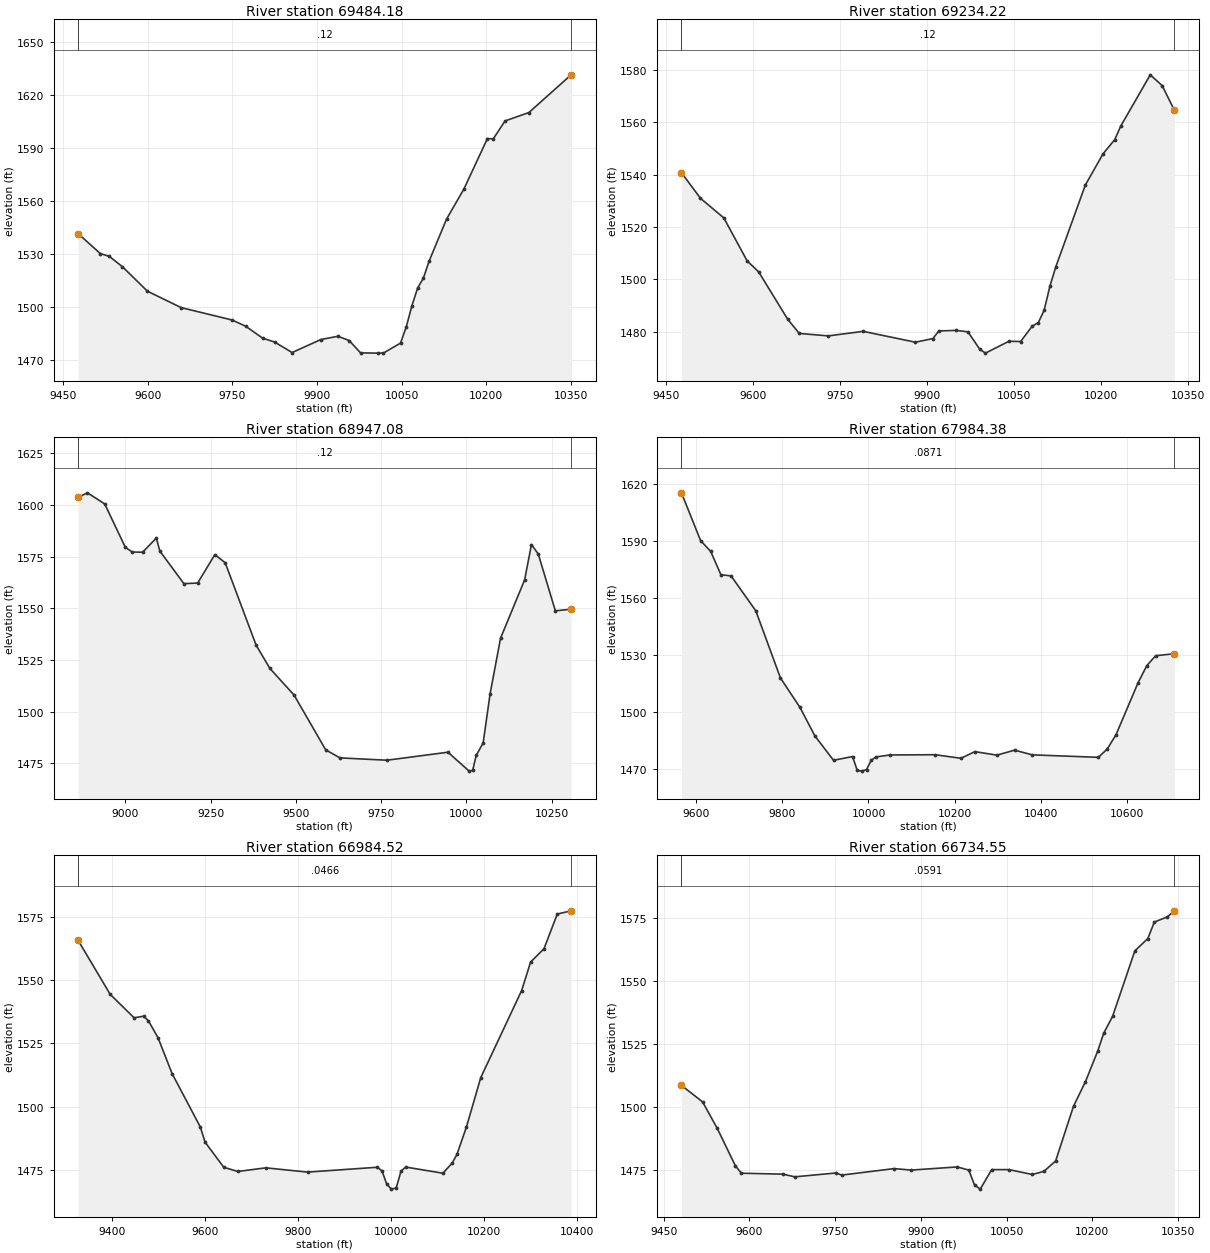
Type RM Length L Ch R = 1 ,69484.18,249.966200,249.966200,249.966200
XS GIS Cut Line= 6
525944.235445531793426.766793095526055.016828946793619.418953664
526100.503957778793723.451183802526120.575498301793811.744229071
526161.823768383794066.329662564526220.487097683794245.504790203
#Sta/Elev= 30
9476.9171541.4659516.0791530.2169532.0951528.5959555.2321522.7699599.6751508.849
9659.3461499.5629749.6381492.5339773.715    14899803.8131482.2019824.786 1480.07
9855.8831474.0889906.7241481.4469936.9161483.3179957.0441480.8989977.1731473.905
10007.481473.76110017.611473.791   100481479.45510058.131488.59810068.261500.754
10078.38 1510.7310088.511516.26310098.661525.94510129.441549.69610160.221566.743
10201.89 1595.3910212.311595.23210233.151605.38810275.341610.128 10350.21631.519
#Mann= 3 , 0 , 0
9476.917    0.12       09476.917    0.12       0 10350.2    0.12       0
#XS Ineff= 2 , 0
       0                               0
Bank Sta=9476.917,10350.2
Exp/Cntr=0.3,0.1

Type RM Length L Ch R = 1 ,69234.22,287.136400,287.136400,287.136400
XS GIS Cut Line= 6
525854.926402202 793402.48100058525864.635292876793485.285481142
525868.074468262793561.406435853525873.081611707793808.532940218
525905.181125583794053.304136731525942.959072743794245.504790204
#Sta/Elev= 30
9476.5641540.7739509.3061530.994 9549.581523.5089589.6811507.1349609.701 1502.88
9659.7281484.7889679.7291479.3869729.729 1478.46 9789.731480.193 9879.84 1476.05
9910.0081477.427 9920.071480.3469950.2541480.5569970.377    1480  9990.51473.437
10000.561471.87710040.921476.39410061.161476.31510081.411482.25310091.531483.463
10101.651488.20510111.771497.52510121.891504.86910172.681536.03810203.181547.964
10223.511553.42710233.67 1558.5310284.621578.14110305.161574.03410326.231564.596
#Mann= 3 , 0 , 0
9476.564    0.12       09476.564    0.12       010326.23    0.12       0
#XS Ineff= 2 , 0
       0                               0
Bank Sta=9476.564,10326.23
Exp/Cntr=0.3,0.1

Type RM Length L Ch R = 1 ,68947.08,962.694600,962.694600,962.694600
XS GIS Cut Line= 6
525673.552585423 792827.96482189525758.509583563  793435.3061537
 525739.45694375793525.480977699 525597.39117232793966.780310839
525575.080661923794094.062663183  525574.0678958794241.164512441
#Sta/Elev= 30
 8861.511603.6228888.8081605.7968939.2951600.4388999.8791579.4599020.0741577.198
9050.3661577.0819090.7551583.9359100.8531577.7129171.5341561.9129211.9241562.202
9262.4111575.9429292.7031572.0189383.5791532.1339423.9681520.9219494.7771508.077
9587.4121481.6399629.2941477.7159767.2291476.5879946.1451480.45110008.411471.314
 10018.71471.73510028.98 1478.8810049.461484.97910069.921508.77810100.451535.524
10171.091563.72610191.141580.80410211.191576.20210261.211548.76910307.471549.553
#Mann= 3 , 0 , 0
 8861.51    0.12       0 8861.51    0.12       010307.47    0.12       0
#XS Ineff= 2 , 0
       0                               0
Bank Sta=8861.51,10307.47
Exp/Cntr=0.3,0.1

Type RM Length L Ch R = 1 ,67984.38,999.864800,999.864800,999.864800
XS GIS Cut Line= 6
524781.076454298792937.350262575524912.799739247793160.834565088
525026.766073777793407.064022725525083.595921159793487.724834871
525101.323019151793522.574966735525204.583891447793987.416541693
#Sta/Elev= 30
9565.5591615.1789609.9771590.1199633.5721584.3939657.1671572.1979680.762 1571.58
9738.2641553.2469795.4911517.9889840.8321502.547 9875.541487.5739918.774 1474.78
9962.9771476.7649973.9311469.4339984.851  1469.19995.5111469.90510006.171474.713
10016.921476.53310049.931477.58210154.491477.71310214.651475.84110247.091479.331
10298.311477.49210339.29 1480.1110380.261477.64310533.921476.34210554.411480.665
10574.891488.17910626.111515.471 10646.61524.53210667.09 1529.6910710.541530.694
#Mann= 3 , 0 , 0
9565.559  0.0871       09565.559  0.0871       010710.54  0.0871       0
#XS Ineff= 2 , 0
       0                               0
Bank Sta=9565.559,10710.54
Exp/Cntr=0.3,0.1

Type RM Length L Ch R = 1 ,66984.52,249.966200,249.966200,249.966200
XS GIS Cut Line= 6
524269.018532343794164.049911438524599.776977023 794233.28830312
524761.894568401794239.218237221525073.825679624794222.165254752
525176.675985114794253.622649422525288.745626444794335.288106906
#Sta/Elev= 30
9326.2741565.6969395.0481544.4179446.717 1535.119467.2751535.7459477.5531533.942
9498.1111527.2859528.6311513.0449589.4911491.9099599.568 1485.979639.8781476.044
9670.0811474.3839730.2081475.8229820.232 1474.149970.4531476.0539980.6161474.647
9990.8411469.382 10001.11467.41110011.361467.91110021.621474.53810031.671476.133
10111.881473.69210131.971477.75210142.041481.105 10162.51491.93910193.381511.474
10281.451545.88610300.761557.14710329.57 1562.4210358.251576.118   103881577.385
#Mann= 3 , 0 , 0
9326.274  0.0466       09326.274  0.0466       0   10388  0.0466       0
#XS Ineff= 2 , 0
       0                               0
Bank Sta=9326.274,10388
Exp/Cntr=0.3,0.1

Type RM Length L Ch R = 1 ,66734.55,749.898600,749.898600,749.898600
XS GIS Cut Line= 6
524395.793352823794362.918547492 524545.94406507794411.824748709
524696.866417869794447.430411268525027.565340983794491.256170997
525120.923638356794521.234273016525225.398485563794574.491848321
#Sta/Elev= 30
 9481.131508.6189518.1571502.0749543.7641491.598 9575.421476.8439585.8651473.886
9658.7551473.513 9679.411472.4529751.4241473.9739761.6381473.1439853.048  1475.7
 9883.36 1475.129963.8471476.3719983.8911475.1029993.9131469.25510003.931467.589
10023.961475.296 10054.21475.302 10094.9 1473.3810115.33  1474.6 10135.91478.741
10167.151500.391   101881510.045 10209.3 1522.0710219.961529.21110235.581535.944
10274.491561.80510297.231566.696 10308.6 1573.2110331.381575.24810343.68 1577.64
#Mann= 3 , 0 , 0
 9481.13  0.0591       0 9481.13  0.0591       010343.68  0.0591       0
#XS Ineff= 2 , 0
       0                               0
Bank Sta=9481.13,10343.68
Exp/Cntr=0.3,0.1