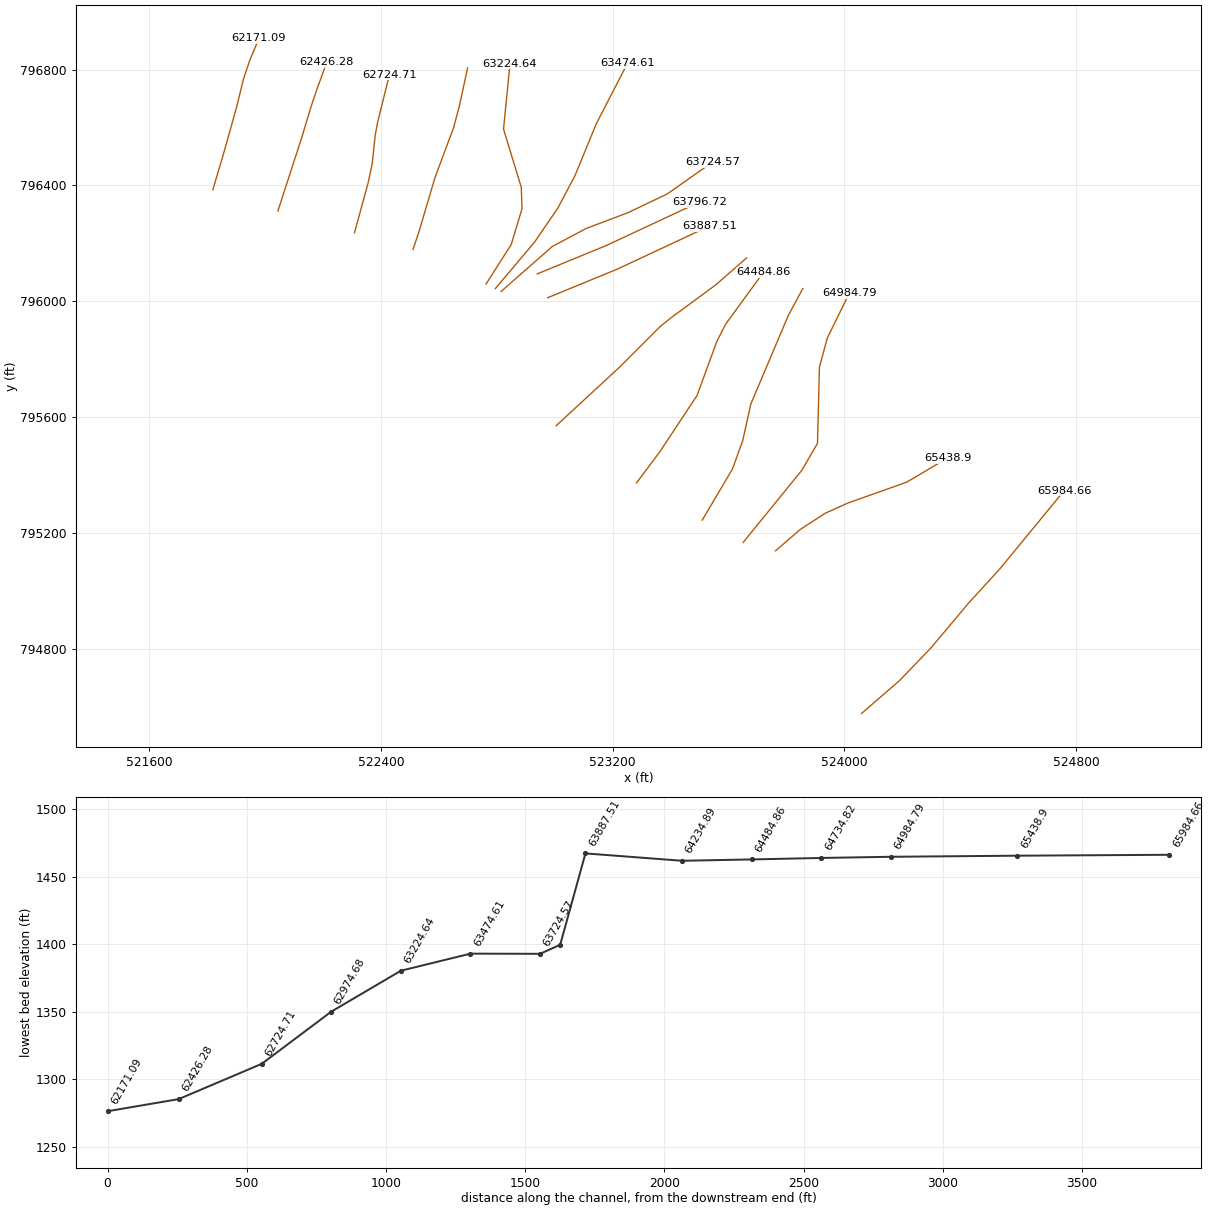
HEC-RAS study 5238_ras.prj: 5238

--- 5238_ras.g01 (geometry) --- (continued)

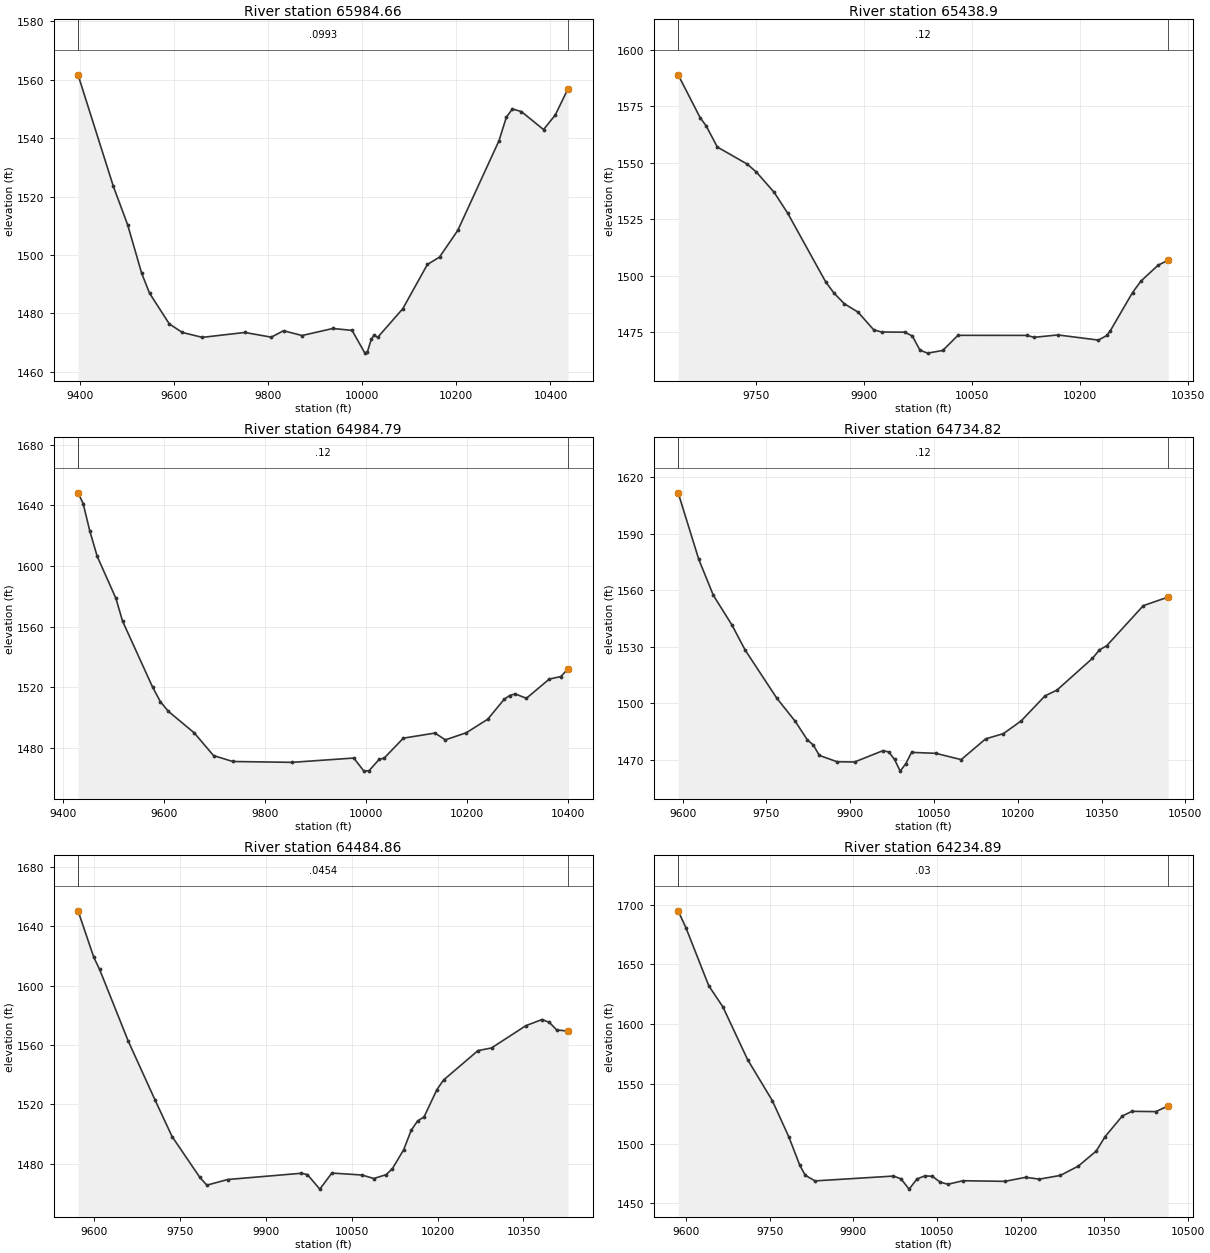
Type RM Length L Ch R = 1 ,65984.66,545.753600,545.753600,545.753600
XS GIS Cut Line= 6
524059.814791177794577.190822083524190.644377604794690.409724561
524300.008282963794804.197170776524432.644355673794962.050157821
524535.688952754795074.481991091524758.756407016795345.753114244
#Sta/Elev= 30
9396.6391561.7139471.5581523.5479502.0431510.304 9531.841493.6849548.593 1486.87
9590.4441476.3829618.0211473.4429660.6521471.7639750.8661473.4459806.9791471.831
9833.1021474.0349872.2871472.3969937.7621474.8029978.6521474.15810005.911466.362
10010.851466.61310019.421471.13410025.721472.57410032.931471.74710086.251481.552
10138.56 1496.7410164.371499.268 10203.11508.40110290.741539.15910306.37 1547.23
10319.281550.02510338.191549.12410385.311542.96210410.251547.96310437.471557.017
#Mann= 3 , 0 , 0
9396.639  0.0993       09396.639  0.0993       010437.47  0.0993       0
#XS Ineff= 2 , 0
       0                               0
Bank Sta=9396.639,10437.47
Exp/Cntr=0.3,0.1

Type RM Length L Ch R = 1 , 65438.9,454.111200,454.111200,454.111200
XS GIS Cut Line= 6
 523762.71281586795138.655813318523847.883035507795212.218847408
523933.397181628795267.888928925524011.100885088795303.027551516
524215.360759209795375.501243616524356.389151645795458.937720543
#Sta/Elev= 30
9641.2661588.9359671.7641569.9819680.0971566.3599695.7161556.9599737.0741549.426
9750.0921545.8319774.7541536.8559793.5111527.6299846.2281497.2519857.7521492.281
9872.0491487.5819891.1991483.8429913.0421475.9779923.8651475.0419956.0571474.957
 9966.681473.2549977.3041466.9719987.9281465.67810008.971466.86110030.011473.562
10125.391473.53210136.171472.68610168.961473.737 10225.21471.453   102371473.512
 10241.71475.56510272.571492.49210284.421497.63610308.131504.61310322.211506.848
#Mann= 3 , 0 , 0
9641.266    0.12       09641.266    0.12       010322.21    0.12       0
#XS Ineff= 2 , 0
       0                               0
Bank Sta=9641.266,10322.21
Exp/Cntr=0.3,0.1

Type RM Length L Ch R = 1 ,64984.79,249.966200,249.966200,249.966200
XS GIS Cut Line= 6
 523650.67601248795167.327794902523853.344193181795416.671339874
523907.413989964 795509.66053111523914.195512809795773.165703001
523941.285384885 795873.12091623524016.900747679796027.474674365
#Sta/Elev= 30
9429.9681648.3059440.1011641.2489453.0971623.3579467.8291606.5429505.0641578.675
9518.0551563.8319577.4811520.3929593.1461510.618 9608.811504.3279660.2551490.071
9698.3731475.1419736.4911471.2299854.0811470.673 9976.231473.5119996.3641464.882
10006.441465.18910026.581472.64310036.611473.51710074.381486.61310137.161489.981
10157.641485.48110199.181490.19510241.611499.09610274.161512.219   10285 1514.72
10295.871515.78810318.261512.88410363.431525.53410386.461527.24310400.821532.371
#Mann= 3 , 0 , 0
9429.968    0.12       09429.968    0.12       010400.82    0.12       0
#XS Ineff= 2 , 0
       0                10073.77       0
Bank Sta=9429.968,10400.82
Exp/Cntr=0.3,0.1

Type RM Length L Ch R = 1 ,64734.82,249.966200,249.966200,249.966200
XS GIS Cut Line= 6
523509.591456084795244.567820421523613.943834061795421.255367728
523649.227344395795518.984818221523677.329865206 795645.71489703
523806.425471583795950.504708112523856.710987858796044.273064181
#Sta/Elev= 30
9592.0061611.8399628.9831576.4319654.9791557.414 9688.37 1541.599711.7251528.429
9768.4111502.8389801.5781490.4789823.1691480.6749833.9651477.866 9844.761472.355
9876.3181469.0099907.7031468.8669958.9941474.9199969.1571474.1459979.3211470.265
9989.485 1464.019999.6481468.01510009.841473.97110053.351473.46310098.721470.126
10142.39 1481.1310174.32 1483.9410206.251490.73410248.831503.99610270.121507.042
10333.651523.91110346.081528.36610359.271530.63510424.821551.92810469.351556.478
#Mann= 3 , 0 , 0
9592.006    0.12       09592.006    0.12       010469.35    0.12       0
#XS Ineff= 2 , 0
       0                               0
Bank Sta=9592.006,10469.35
Exp/Cntr=0.3,0.1

Type RM Length L Ch R = 1 ,64484.86,249.966200,249.966200,249.966200
XS GIS Cut Line= 6
523282.448117843795372.889056968523363.199064071795480.687110922
523491.488647541795674.863228868523560.660518532795863.413403333
523590.307615563795921.151654755523720.975122599796100.439629131
#Sta/Elev= 30
9572.3281650.5249599.9551619.0659609.9441611.0499659.9821562.6989707.0171522.792
9736.5361498.3389785.1011470.7569797.2431465.5989833.6231469.4029961.8561473.597
9972.7971472.7289994.4091462.91510015.431473.75410067.821472.437 10088.81470.079
10110.321472.68910121.071476.71110140.891489.54210153.911502.56210165.151508.859
10176.391511.61610198.881530.02610210.351536.43410270.441556.27210294.211558.087
10354.111573.09910382.441577.26310395.191575.30210407.931570.22210427.871569.449
#Mann= 3 , 0 , 0
9572.328  0.0454       09572.328  0.0454       010427.87  0.0454       0
#XS Ineff= 2 , 0
       0                               0
Bank Sta=9572.328,10427.87
Exp/Cntr=0.3,0.1

Type RM Length L Ch R = 1 ,64234.89,347.379800,347.379800,347.379800
XS GIS Cut Line= 6
523004.982679295795570.398799665523224.882021531 795773.53562869
523362.285917327795911.051884352523399.562272517795941.612608089
523555.504518711796056.304387975523662.844411546796150.067166045
#Sta/Elev= 30
9586.1851694.7419600.1041680.577 9641.071632.0189666.2351614.4769710.5321570.335
9754.8291536.019 9784.361505.7779804.1681481.8629813.8911473.5249831.3511468.804
9971.8931472.8459985.403 1470.559999.9971461.91910014.261470.47710028.531473.045
 10041.71472.62310055.721467.73410069.751465.992 10096.41468.94110171.831468.427
 10208.81471.82210233.451470.28110270.861473.37310303.091481.14910335.291493.754
10350.861505.634   103821523.10110399.381527.01110442.17 1526.7710464.321531.588
#Mann= 3 , 0 , 0
9586.185    0.03       09586.185    0.03       010464.32    0.03       0
#XS Ineff= 2 , 0
       0                10147.62       0
Bank Sta=9586.185,10464.32
Exp/Cntr=0.3,0.1

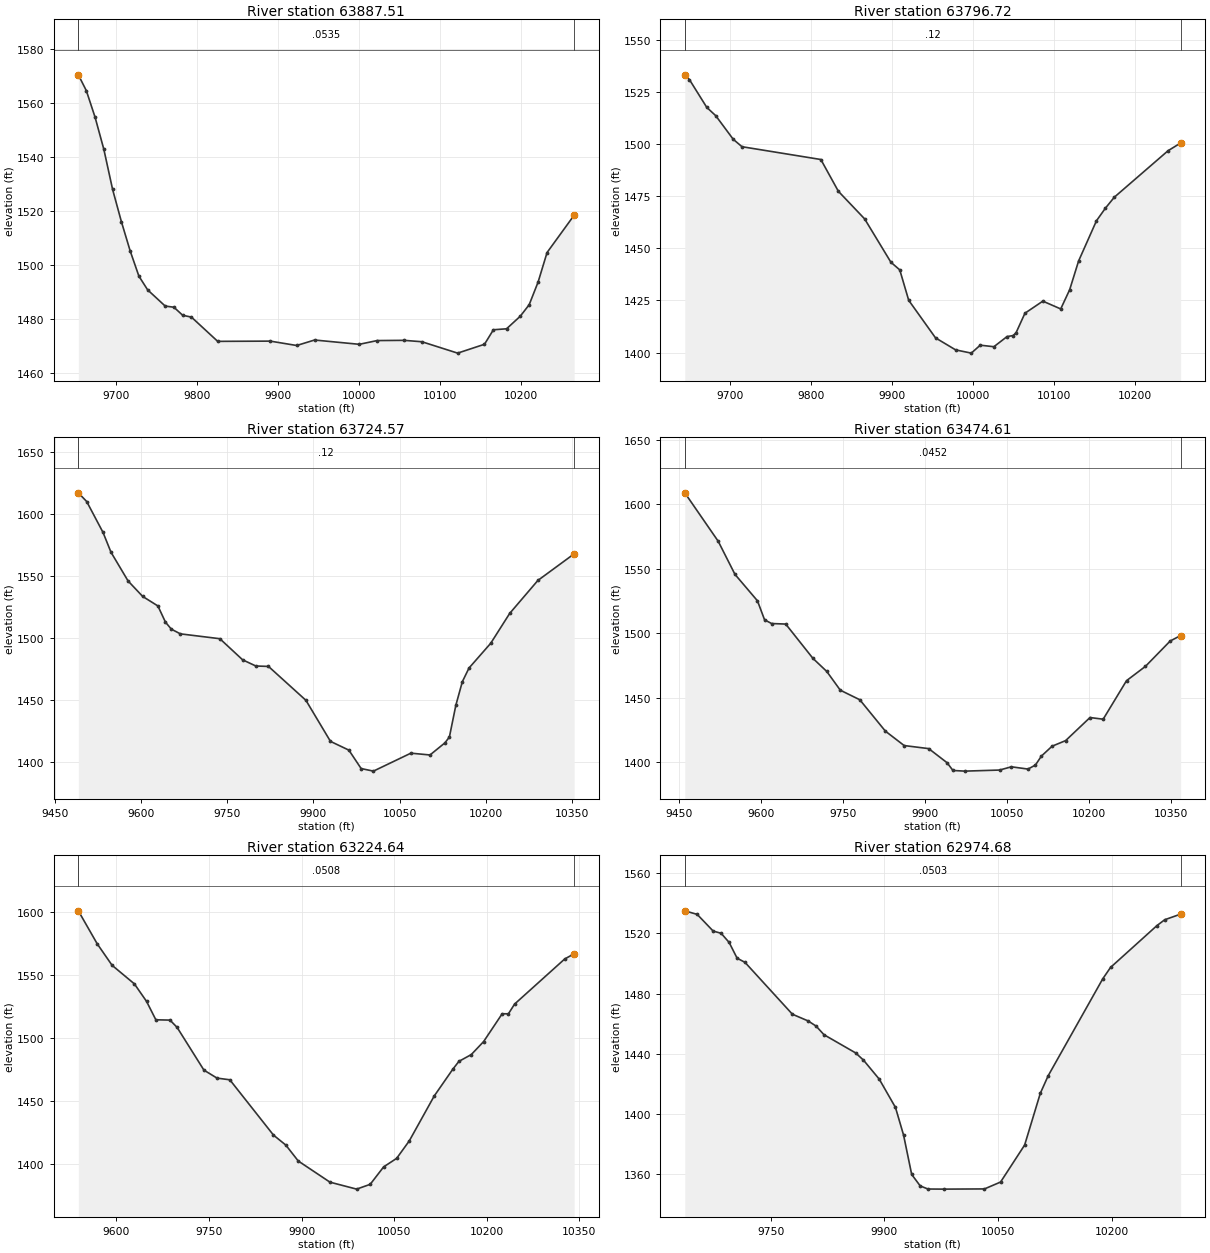
Type RM Length L Ch R = 1 ,63887.51,90.789300,90.789300,90.789300
XS GIS Cut Line= 3
522975.856294602796012.424965024 523216.08639586796111.149664149
523535.296256334796260.333653942
#Sta/Elev= 30
 9653.681570.3319663.5651564.4699674.3771554.6159685.1881542.755    9696 1527.91
9706.8111516.0349717.6231505.2359728.434 1495.869739.2461490.7759760.8691484.794
9771.6811484.3519782.4921481.3779793.3041480.6959825.7381471.7279890.6071471.816
9923.2441470.196 9945.321472.22510000.511470.63610022.59 1472.02 10055.71472.105
10077.781471.58510121.931467.37410155.051470.64910166.081476.019 10182.31476.373
 10199.21481.01410210.241485.28410221.281493.69110232.311504.59110265.761518.405
#Mann= 3 , 0 , 0
 9653.68  0.0535       0 9653.68  0.0535       010265.76  0.0535       0
#XS Ineff= 2 , 0
       0                               0
Bank Sta=9653.68,10265.76
Exp/Cntr=0.3,0.1

Type RM Length L Ch R = 1 ,63796.72,72.148800,72.148800,72.148800
XS GIS Cut Line= 3
522939.657238256796094.695547628523179.887339514796193.420246753
523499.097199988796342.604236546
#Sta/Elev= 30
9644.3891533.4169650.1651531.0819671.4981517.782  9682.61513.7749704.2231502.424
9715.0341498.8749812.3381492.7349833.9611477.4699866.3951464.193 9898.831443.363
9909.7571439.7029920.7951425.081 9953.911407.031  9978.71401.2669998.0631399.704
 10009.11403.52410025.941402.78210042.221407.66410049.561408.13110053.251409.438
10064.29 1418.8810086.371424.68410108.441420.93810119.481430.15410130.521443.977
 10152.61463.31410163.641469.36110174.671474.637 10240.91496.93210256.461500.666
#Mann= 3 , 0 , 0
9644.389    0.12       09644.389    0.12       010256.46    0.12       0
#XS Ineff= 2 , 0
       0                               0
Bank Sta=9644.389,10256.46
Exp/Cntr=0.3,0.1

Type RM Length L Ch R = 1 ,63724.57,249.966200,249.966200,249.966200
XS GIS Cut Line= 6
522815.000786788796034.059042633522991.996042566796189.611663917
 523109.04879357796251.684392014523252.769551357796305.994778305
523388.928474588796370.964473196523544.420370717796480.390784302
#Sta/Elev= 30
9490.3541617.1799504.9261610.1659533.4241585.2269547.2291569.3519577.0171546.189
9602.3591533.7619628.9641526.0619642.1051513.0359652.3891507.364 9668.131503.585
9736.907 1499.679776.5431482.6729799.5451477.6989821.5821477.3559886.8311450.048
9929.576 1416.989961.6361409.9329983.008 1395.09 10004.41393.02110069.641407.485
10102.971406.03210128.961415.79810136.75 1420.5110148.011446.12610159.271465.033
10170.871476.03510208.77 1496.03 10241.81520.07110290.871546.61510354.071568.041
#Mann= 3 , 0 , 0
9490.354    0.12       09490.354    0.12       010354.07    0.12       0
#XS Ineff= 2 , 0
       0                               0
Bank Sta=9490.354,10354.07
Exp/Cntr=0.3,0.1

Type RM Length L Ch R = 1 ,63474.61,249.966200,249.966200,249.966200
XS GIS Cut Line= 6
522795.148067639796044.081774641522929.867455583796203.646855075
523010.950813662796322.136708333523070.161729045796434.301453898
523143.465339142 796612.74637962523251.377059107796821.893679101
#Sta/Elev= 30
 9460.311608.7949521.4791571.2639552.1781545.6119593.3341525.1289606.3831510.376
9619.2871507.5139645.0941507.1019694.8861480.5349720.2861470.3739745.0151455.864
9780.7411448.4459827.5611424.141 9861.961412.9619906.9241410.5919940.4411399.691
9951.3171393.6479973.0691393.14510036.641393.97610058.261396.49810088.711394.738
10102.251397.83310113.261404.794 10132.8 1412.4610157.621416.79110202.241434.678
10226.351433.37710269.081463.21710303.791474.33810349.051493.96310368.171498.201
#Mann= 3 , 0 , 0
 9460.31  0.0452       0 9460.31  0.0452       010368.17  0.0452       0
#XS Ineff= 2 , 0
       0                               0
Bank Sta=9460.31,10368.17
Exp/Cntr=0.3,0.1

Type RM Length L Ch R = 1 ,63224.64,249.966100,249.966100,249.966100
XS GIS Cut Line= 6
522763.233108815796060.194181024522849.739404399 796195.82071367
522887.192929813796320.200252428 522884.67185295796393.686736657
 522823.33676802796594.591071233 522845.61655069796820.109680278
#Sta/Elev= 30
9538.2031600.6649568.8131574.5569592.9291557.5659629.1021542.8629648.8111529.015
9663.8751514.4589686.8271514.2149698.3021508.4619741.8081474.6539763.0031468.335
9783.7891466.9929854.6051423.2319874.6251415.3259894.7441402.7479946.1551386.005
9989.417  1380.510011.351384.29610033.181398.10210054.251404.84410074.781418.702
10115.181454.19310145.191475.29510155.211481.58510175.241486.93410195.281497.248
10225.331519.23210235.431519.19510245.521526.924 10326.61562.52910342.031566.706
#Mann= 3 , 0 , 0
9538.203  0.0508       09538.203  0.0508       010342.03  0.0508       0
#XS Ineff= 2 , 0
       0                               0
Bank Sta=9538.203,10342.03
Exp/Cntr=0.3,0.1

Type RM Length L Ch R = 1 ,62974.68,249.966200,249.966200,249.966200
XS GIS Cut Line= 6
522510.906278244796179.488777899522531.860810874796242.118539369
522586.067260985796425.765827327522650.953730486796600.010802238
522670.095113888796671.431333452522699.149963704796805.463021572
#Sta/Elev= 30
9636.3851534.9779652.7411532.6229673.8311521.5429684.3761520.0569694.9211513.983
9705.4321503.5339715.8581500.7639778.4171466.328 9799.271461.8539809.6971458.449
9820.1231452.7239861.8291440.6589872.2561435.8619893.109  1423.2 9914.491404.432
 9925.191386.0789935.8911359.9649947.0981352.3599957.2931350.2739978.6941350.199
10031.991350.33510053.261354.91110085.011379.47110105.721413.84510116.071425.454
10188.141489.84710198.371497.36910259.761525.21110269.99 1529.0710290.931532.782
#Mann= 3 , 0 , 0
9636.385  0.0503       09636.385  0.0503       010290.93  0.0503       0
#XS Ineff= 2 , 0
       0                               0
Bank Sta=9636.385,10290.93
Exp/Cntr=0.3,0.1

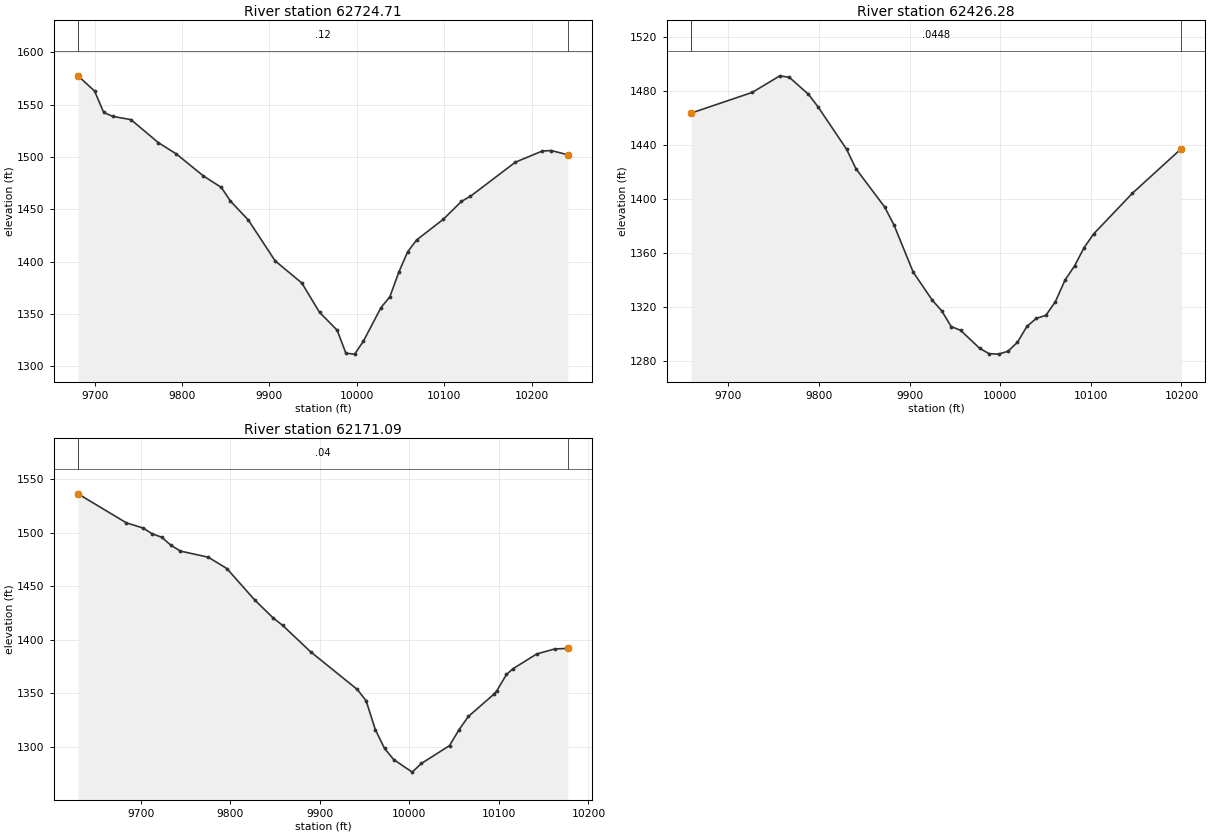
Type RM Length L Ch R = 1 ,62724.71,298.431400,298.431400,298.431400
XS GIS Cut Line= 6
522308.708555328796236.828430681522355.829139274796409.265626957
522369.875015456796475.551961386522380.183836446796573.479578052
522388.784589381796619.297636843522429.370936752796783.026484229
#Sta/Elev= 30
9681.0471577.6619699.9741563.0849710.3891542.6989720.8051538.8629741.6361535.762
9772.8831513.7969793.5351502.9699824.4841481.9419845.1171470.8799855.4331457.878
9875.9181439.7559906.5841400.7169937.1471379.5129957.3731351.5259977.5651334.397
9987.5831312.3579997.601 1311.5310007.621323.987 10027.71356.02310037.871366.375
10048.051389.77410058.221409.418 10068.41420.63910099.22 1440.6410119.791457.603
10130.081462.48310181.521495.09810212.381505.78710222.741506.19210241.471502.106
#Mann= 3 , 0 , 0
9681.047    0.12       09681.047    0.12       010241.47    0.12       0
#XS Ineff= 2 , 0
       0                               0
Bank Sta=9681.047,10241.47
Exp/Cntr=0.3,0.1

Type RM Length L Ch R = 1 ,62426.28,255.192100,255.192100,255.192100
XS GIS Cut Line= 6
522044.180342145796311.843894121522127.039307737796567.058794941
 522158.97311368  796672.9822469522177.572180816796728.672974214
522208.683753161796813.531222717522213.307308189796825.268922984
#Sta/Elev= 30
9658.8021463.6769726.2241478.9679756.7451491.2319767.2591490.1069788.2871477.571
  9798.81468.3949830.3421436.9829840.8561422.3879872.3971394.2629882.9111380.611
9903.9391346.0169924.966 1325.35 9935.431317.413 9945.881305.837 9956.331302.979
 9977.231289.757 9987.681285.756 9998.13 1285.4110008.561287.523   100191294.168
10029.431305.88810039.891311.86310050.431314.10110060.981324.32610071.521340.142
10082.061350.67110092.61 1364.1910103.221374.39510145.821404.32510199.481437.114
#Mann= 3 , 0 , 0
9658.802  0.0448       09658.802  0.0448       010199.48  0.0448       0
#XS Ineff= 2 , 0
       0                               0
Bank Sta=9658.802,10199.48
Exp/Cntr=0.3,0.1

Type RM Length L Ch R = 1 ,62171.09,255.076400,255.076400,255.076400
XS GIS Cut Line= 6
521819.675576782796385.459188502521855.042341936796504.615647044
521900.612038686796666.985554507521925.669123096796768.896826663
521947.018444504796831.960093178521978.852873556796908.100130422
#Sta/Elev= 30
9629.8991536.5839683.7561509.5399702.4391504.626 9712.871499.1729723.3011496.046
9733.7321488.4949744.1641483.0849775.3661477.3459796.1381466.7439827.2981437.294
 9848.071420.3949858.4571413.6319889.6161388.9519941.7471353.7729951.6381343.222
9961.9181316.2459972.1991298.6529982.4811288.18810003.121276.44910013.441284.575
10044.791301.22410055.35 1316.02 10065.91328.50210094.371349.29310097.651352.535
10108.441367.76110115.551373.01210142.091386.87110162.421391.61910176.921392.067
#Mann= 3 , 0 , 0
9629.899    0.04       09629.899    0.04       010176.92    0.04       0
#XS Ineff= 2 , 0
       0                               0
Bank Sta=9629.899,10176.92
Exp/Cntr=0.3,0.1