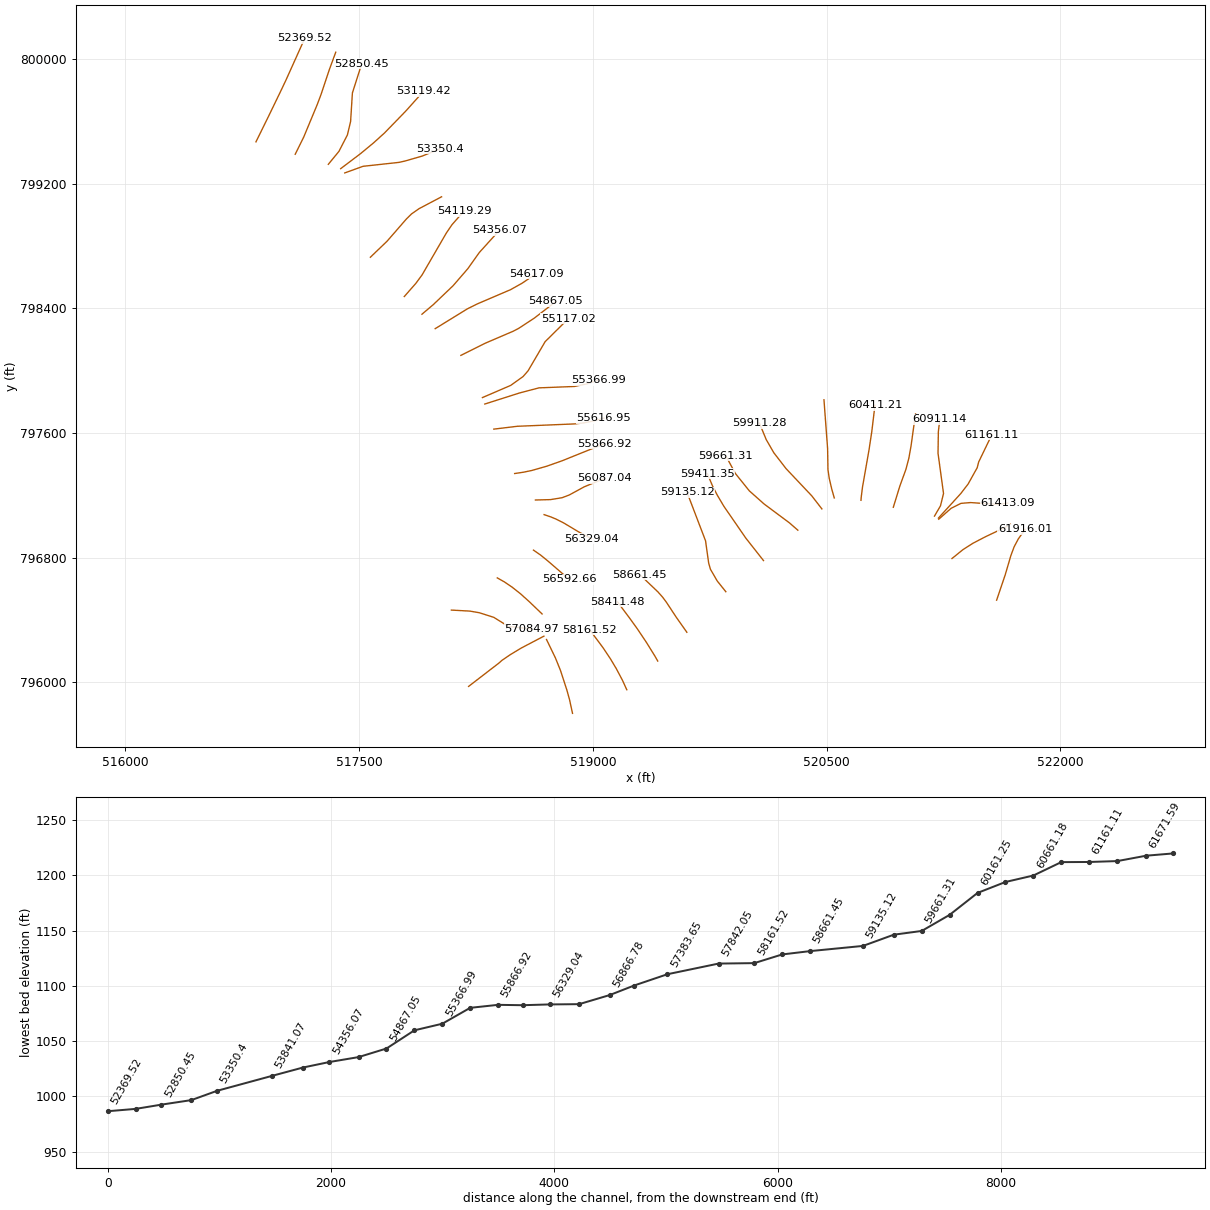
HEC-RAS study 5238_ras.prj: 5238

--- 5238_ras.g01 (geometry) --- (continued)

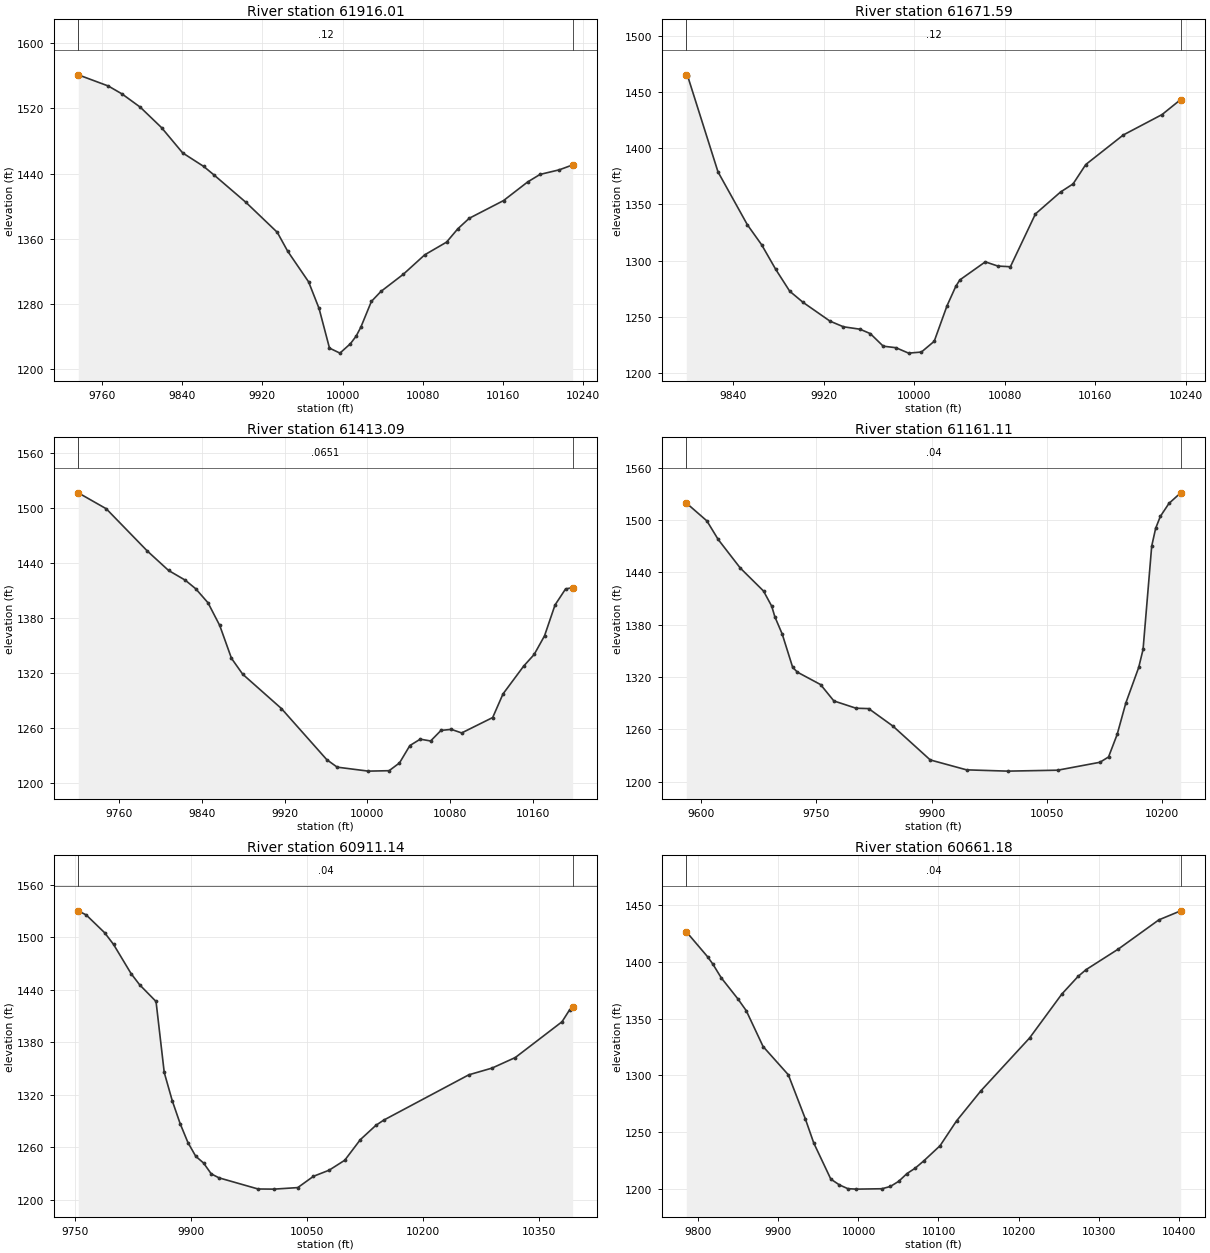
Type RM Length L Ch R = 1 ,61916.01,244.420200,244.420200,244.420200
XS GIS Cut Line= 6
521590.414151939 796526.78472434521645.418198945796688.927822793
 521682.18708859796814.102071821521702.783236342796869.056820185
 521729.90864131796920.660442856521773.215848963796980.750336718
#Sta/Elev= 30
 9736.521561.1659766.461 1547.469780.1171537.7559798.2961521.5149819.5191496.427
  9840.61465.382 9861.611448.7559872.1161438.0439903.6321404.7639934.8991367.986
9945.3091344.732 9966.131307.228 9976.541274.645 9986.951225.955 9997.361219.781
 10007.81231.32210013.561240.70310018.251251.75510028.711283.17810038.221295.445
10060.541316.522 10081.91340.38410103.631355.93110114.921372.35610126.221385.166
10160.411406.88210184.39 1429.6710196.811438.99210216.021444.64310229.33 1450.66
#Mann= 3 , 0 , 0
 9736.52    0.12       0 9736.52    0.12       010229.33    0.12       0
#XS Ineff= 2 , 0
       0                               0
Bank Sta=9736.52,10229.33
Exp/Cntr=0.3,0.1

Type RM Length L Ch R = 1 ,61671.59,258.502600,258.502600,258.502600
XS GIS Cut Line= 6
521304.040445827796794.238069913521374.599219996796851.383361468
521438.340841549796892.021169237 521517.54352349796933.339935024
521640.729322563796991.930946203521679.319628032797013.923253106
#Sta/Elev= 30
9798.7891465.4059800.1011463.9539826.7681379.0289852.7051331.9699865.3191314.145
9877.7381292.3069890.135  1272.89901.9941262.8259925.7131246.1759937.5731241.147
9952.193    12399961.291 1235.079972.7121223.8879983.9141222.5329995.0931217.707
10006.421218.66810017.741228.24110029.071259.91410036.841277.247 10040.4 1282.89
10062.86 1298.9510073.931295.20610085.011294.59110107.151341.622 10129.31361.098
10140.371368.31110151.591385.56310184.671411.82910218.951430.02510235.431443.411
#Mann= 3 , 0 , 0
9798.789    0.12       09798.789    0.12       010235.43    0.12       0
#XS Ineff= 2 , 0
       09970.615                       0
Bank Sta=9798.789,10235.43
Exp/Cntr=0.3,0.1

Type RM Length L Ch R = 1 ,61413.09,251.975400,251.975400,251.975400
XS GIS Cut Line= 6
521219.197779696797046.473023315   521298.642915797116.541749224
521361.375748289797148.077321627521422.589229206797153.271527656
521598.896274323797141.042192101521661.744830691797149.770600003
#Sta/Elev= 30
 9720.081516.2929747.139 1498.959787.0031452.761 9807.491431.6569823.6141421.078
9833.7691411.7299845.6711396.3989857.0361371.6439868.4011335.8379879.2771318.494
 9916.711281.1259960.6931225.291 9970.741217.17310000.881212.84110020.981213.312
10031.031221.75610041.081240.71510051.141247.69110061.191245.71410071.241257.256
10081.251258.35210091.251254.49110121.251271.27110131.251297.02710151.341327.481
10161.391340.01710171.441360.34510181.611394.02410191.791411.46910198.661412.947
#Mann= 3 , 0 , 0
 9720.08  0.0651       0 9720.08  0.0651       010198.66  0.0651       0
#XS Ineff= 2 , 0
       0                               0
Bank Sta=9720.08,10198.66
Exp/Cntr=0.3,0.1

Type RM Length L Ch R = 1 ,61161.11,249.966200,249.966200,249.966200
XS GIS Cut Line= 6
 521216.83801428 797053.48854214521360.731361768797211.458896477
521407.753962427 797272.56385289521465.999191581797377.206633707
521475.247608054797413.618603644521559.791460958797588.592228841
#Sta/Elev= 30
9581.1061519.3979607.8471498.8969622.571 1477.579651.2881444.8299681.4651418.516
9692.1621401.0779696.1891389.0529705.7861369.1849719.4111330.9519725.6361325.429
9755.6691311.2479772.9621292.4889801.8051284.1319818.2021283.6949849.7471263.642
9898.2461224.8479945.4691213.487    99991212.01910063.961213.08310118.841222.157
10130.071228.24610141.291254.11910152.521290.051 10169.3 1330.9110174.961351.534
10186.19 1469.9410191.321490.34210197.411504.01110208.641518.95310223.89 1531.06
#Mann= 3 , 0 , 0
9581.106    0.04       09581.106    0.04       010223.89    0.04       0
#XS Ineff= 2 , 0
       0                10064.52       0
Bank Sta=9581.106,10223.89
Exp/Cntr=0.3,0.1

Type RM Length L Ch R = 1 ,60911.14,249.966200,249.966200,249.966200
XS GIS Cut Line= 6
521191.635515798797066.319048468521230.062517054797131.902540019
521249.760942614797211.406572993 521214.43826846797469.839247812
521216.586598825797607.790526347521225.981480527797688.644838638
#Sta/Elev= 30
9753.7961530.261 9764.111525.5249787.8741505.2329799.489 1491.759822.0811458.472
9833.1631445.6589854.3681426.5549864.9711345.3349875.4011312.8439885.504  1286.9
9895.6071265.1759905.7091249.4779915.777 1241.819925.7811229.3239935.7841224.807
9986.2891212.05410006.961211.89510037.621213.64710057.931226.573 10078.21233.563
10098.371244.93610118.551268.52110138.661284.87210148.691290.78710258.821342.679
10288.851350.36710318.921362.43910379.331403.36910389.391417.37510393.061419.772
#Mann= 3 , 0 , 0
9753.796    0.04       09753.796    0.04       010393.06    0.04       0
#XS Ineff= 2 , 0
       0                               0
Bank Sta=9753.796,10393.06
Exp/Cntr=0.3,0.1

Type RM Length L Ch R = 1 ,60661.18,249.966200,249.966200,249.966200
XS GIS Cut Line= 6
520927.531566102797123.115596749 520969.43670465797259.119249519
521008.459023416797366.564876993521027.152059941797437.455381683
521040.890022689797514.214461736521070.041339316797722.005167372
#Sta/Elev= 30
9784.8791426.411 9811.471404.3969818.1011397.859 9828.521385.8669849.3591367.268
9859.7841356.9189880.8151325.3539912.3611300.4569933.476 1261.929944.1341240.373
 9965.451208.5939976.1081203.5189986.7671200.1599997.4251199.77310029.261200.107
10039.861202.11710050.251206.64110060.591213.46410070.931218.25410081.271224.433
10101.961238.001 10122.51259.81310152.981286.341 10213.81332.859 10254.21371.616
10274.391387.06510284.491393.08310324.881411.25310375.371436.89210402.64 1444.84
#Mann= 3 , 0 , 0
9784.879    0.04       09784.879    0.04       010402.64    0.04       0
#XS Ineff= 2 , 0
       0                               0
Bank Sta=9784.879,10402.64
Exp/Cntr=0.3,0.1

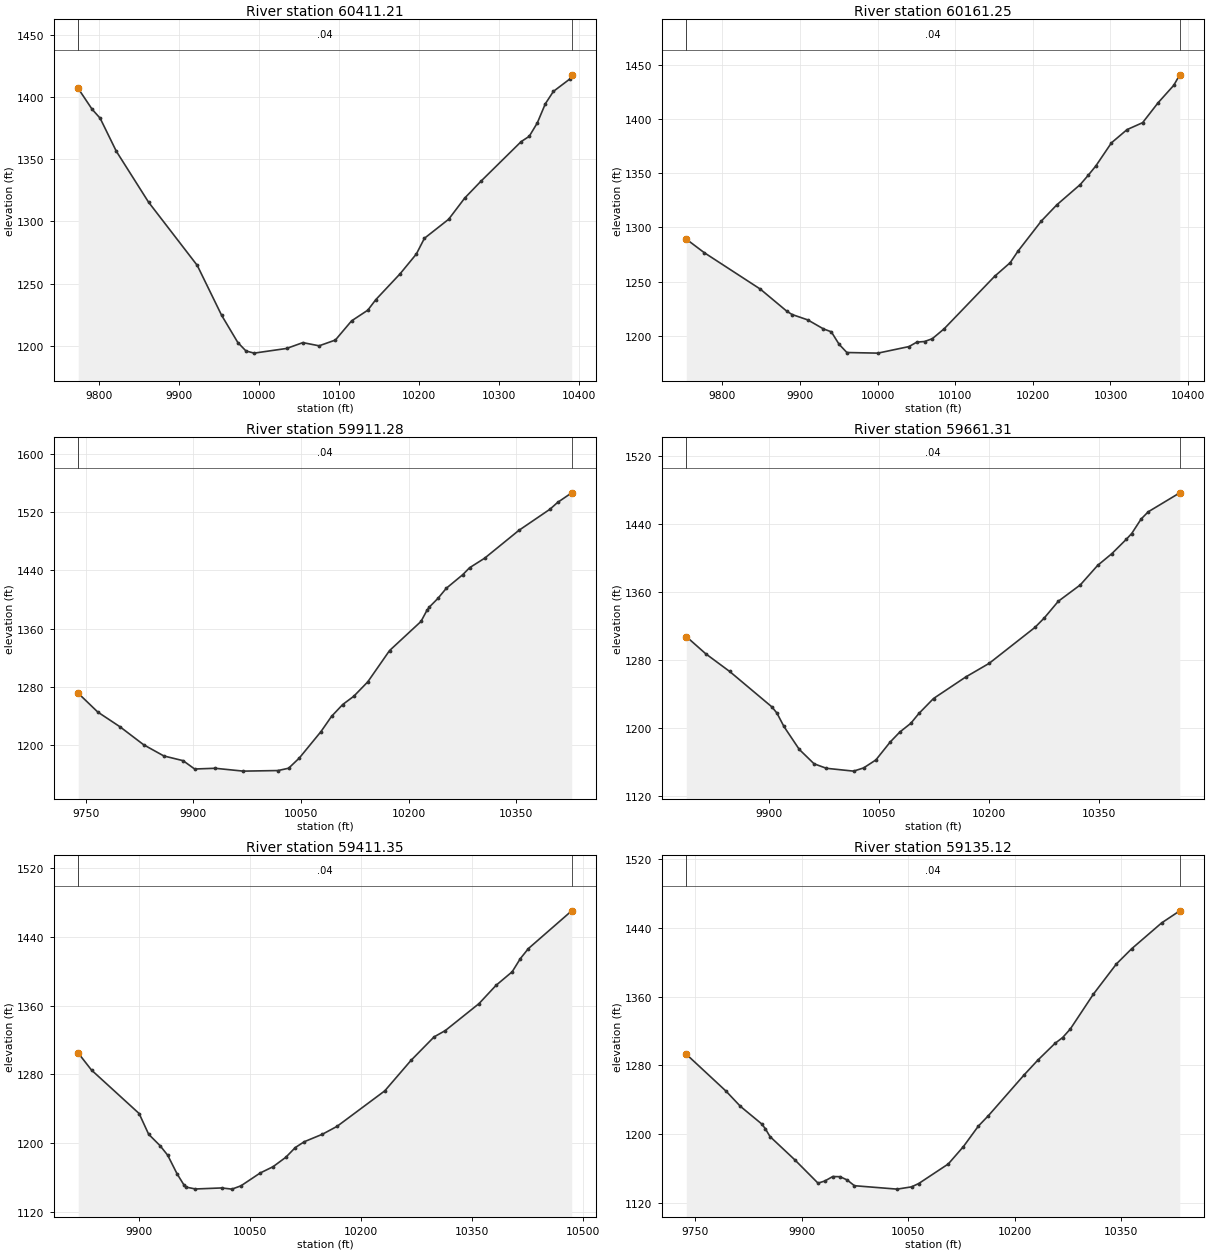
Type RM Length L Ch R = 1 ,60411.21,249.966200,249.966200,249.966200
XS GIS Cut Line= 6
 520720.13304852797167.717428489520721.619478646797187.869733177
520729.775815305797252.281405103520771.665688499797491.659136195
520789.430120905797608.942080712  520809.7797188797777.683026481
#Sta/Elev= 30
9773.9651407.1739791.2951390.4649801.3591383.2239821.5191356.6729861.8581315.583
9922.7581264.5839953.2081224.3639973.5081202.3989983.6581195.6439993.8081193.913
10034.431197.68710054.731202.38310075.041199.80910095.351204.45610115.61 1219.91
10135.831228.51210145.951237.05710176.291257.88810196.521273.75410206.631286.443
10236.911301.78710257.051318.906 10277.21332.40110327.561364.37710337.631368.627
10347.711379.42510357.78 1394.8910367.851404.843   103881414.642 10390.71418.185
#Mann= 3 , 0 , 0
9773.965    0.04       09773.965    0.04       0 10390.7    0.04       0
#XS Ineff= 2 , 0
       0                               0
Bank Sta=9773.965,10390.7
Exp/Cntr=0.3,0.1

Type RM Length L Ch R = 1 ,60161.25,249.966200,249.966200,249.966200
XS GIS Cut Line= 6
520548.646993244797182.954075901520532.509429758797239.771485386
520516.445817384797308.497542041520508.247435196797364.165999964
520505.902457765797498.642249463520482.549431869 797812.75916821
#Sta/Elev= 30
9753.7631289.2059776.6811276.8259849.0051243.1439883.406 1222.599889.9781219.666
9910.1941214.693 9930.411206.372 9940.511203.7029950.5241192.2049960.538 1184.59
10000.551184.02710040.561190.07410050.571194.16110060.571194.74810070.581197.323
10085.851206.50510150.811254.89810170.871267.482 10180.91278.12910210.991305.931
10231.05 1320.9410261.141339.61210271.171347.973 10281.21356.79510301.261378.071
10321.321390.25610341.381396.65310361.431415.13410381.45  1431.110389.221440.802
#Mann= 3 , 0 , 0
9753.763    0.04       09753.763    0.04       010389.22    0.04       0
#XS Ineff= 2 , 0
       0                               0
Bank Sta=9753.763,10389.22
Exp/Cntr=0.3,0.1

Type RM Length L Ch R = 1 ,59911.28,249.966200,249.966200,249.966200
XS GIS Cut Line= 6
520469.139255379797112.576413199520404.632609453797195.998819922
520239.600062104797370.646719069520160.931737196 797472.51678608
520111.868182546797557.565498131520068.206814606797663.573495899
#Sta/Elev= 30
 9739.581271.1269766.9091245.2599797.7741225.0899830.7931200.3699858.9061185.011
9885.6881178.5479901.8181167.1019930.4261168.0899969.6021164.18110017.851164.971
10032.74 1168.1510047.631182.13510077.841218.46410092.591239.41110108.081255.608
10123.571266.99210143.061286.773 10173.4 1329.7210217.171369.65210225.481384.887
10228.951389.58410240.72 1401.26 10252.51415.26210275.451433.94910284.891443.436
 10305.9 1456.5410353.531494.70110396.891523.76410407.571533.11810427.211546.302
#Mann= 3 , 0 , 0
 9739.58    0.04       0 9739.58    0.04       010427.21    0.04       0
#XS Ineff= 2 , 0
       0                               0
Bank Sta=9739.58,10427.21
Exp/Cntr=0.3,0.1

Type RM Length L Ch R = 1 ,59661.31,249.966200,249.966200,249.966200
XS GIS Cut Line= 6
520314.884528876796976.035148146520260.200550086797023.607286696
520098.792114787797143.759523124520004.003371926797227.940746935
 519914.09521238 797339.75988529519852.425878616797454.047079798
#Sta/Elev= 30
9786.6011307.949 9813.251287.6559845.8761266.8989903.5691225.2029910.4641217.933
9920.0261202.1419940.987 1175.179961.1941158.2519978.0361152.94510015.211149.616
10028.891153.38410045.651162.77410065.291183.93310078.351195.59910093.331205.843
10104.49 1217.51 10124.41235.04710168.651260.50810200.481276.45310262.94 1318.68
10275.781329.86710294.95 1349.5110324.991368.752 10348.61391.63910368.071405.518
10387.571422.178 10395.21429.20710408.061446.24410417.771454.74410460.88 1477.09
#Mann= 3 , 0 , 0
9786.601    0.04       09786.601    0.04       010460.88    0.04       0
#XS Ineff= 2 , 0
       0                               0
Bank Sta=9786.601,10460.88
Exp/Cntr=0.3,0.1

Type RM Length L Ch R = 1 ,59411.35,276.231500,276.231500,276.231500
XS GIS Cut Line= 6
520094.572943353796781.022500662519982.053054617796923.781473065
519840.176556196797129.400041508519798.436510452797200.018288195
519766.721483999797261.601698233519734.152585464797339.201998038
#Sta/Elev= 30
 9817.191304.7179835.1781284.8719899.5261234.2849912.3951210.1639927.7181196.946
9938.1341185.7799950.808 1164.099960.3451150.8159963.2351148.5679975.6611146.412
10011.211147.62110024.991146.23810037.231150.10210063.211165.03110080.541172.322
10097.871183.33610110.69 1194.6810122.931201.49810147.421210.19510167.211219.396
10231.641260.69110266.971296.06810298.33 1323.5410313.441330.87710358.981362.256
10382.071383.58110403.88 1399.3710414.841414.61810425.811426.40910484.331470.341
#Mann= 3 , 0 , 0
 9817.19    0.04       0 9817.19    0.04       010484.33    0.04       0
#XS Ineff= 2 , 0
       0                               0
Bank Sta=9817.19,10484.33
Exp/Cntr=0.3,0.1

Type RM Length L Ch R = 1 ,59135.12,473.667000,473.667000,473.667000
XS GIS Cut Line= 6
 519852.66333141796581.262663382519797.725865875 796649.96665996
519754.067521194796725.279371697519742.556864692796765.736135334
519722.698804962796907.733053597519603.683355786797219.279484732
#Sta/Elev= 30
9737.7281293.1279793.729 1250.139814.0491232.3659843.6741212.1469848.9031206.573
9855.6321197.2519890.4181170.2989923.2091143.0589932.5651145.4539944.0191150.734
9954.2911150.5479964.3821146.683 9974.461140.05310034.591136.07310054.92  1138.7
10065.091142.61910106.671165.36410127.861185.48110149.061209.47910163.131221.559
10213.671269.24410232.541286.05210256.931305.73410267.751312.56710278.571322.566
10311.021363.07410343.471398.27610364.881415.88810407.041445.93910432.631460.049
#Mann= 3 , 0 , 0
9737.728    0.04       09737.728    0.04       010432.63    0.04       0
#XS Ineff= 2 , 0
       0                               0
Bank Sta=9737.728,10432.63
Exp/Cntr=0.3,0.1

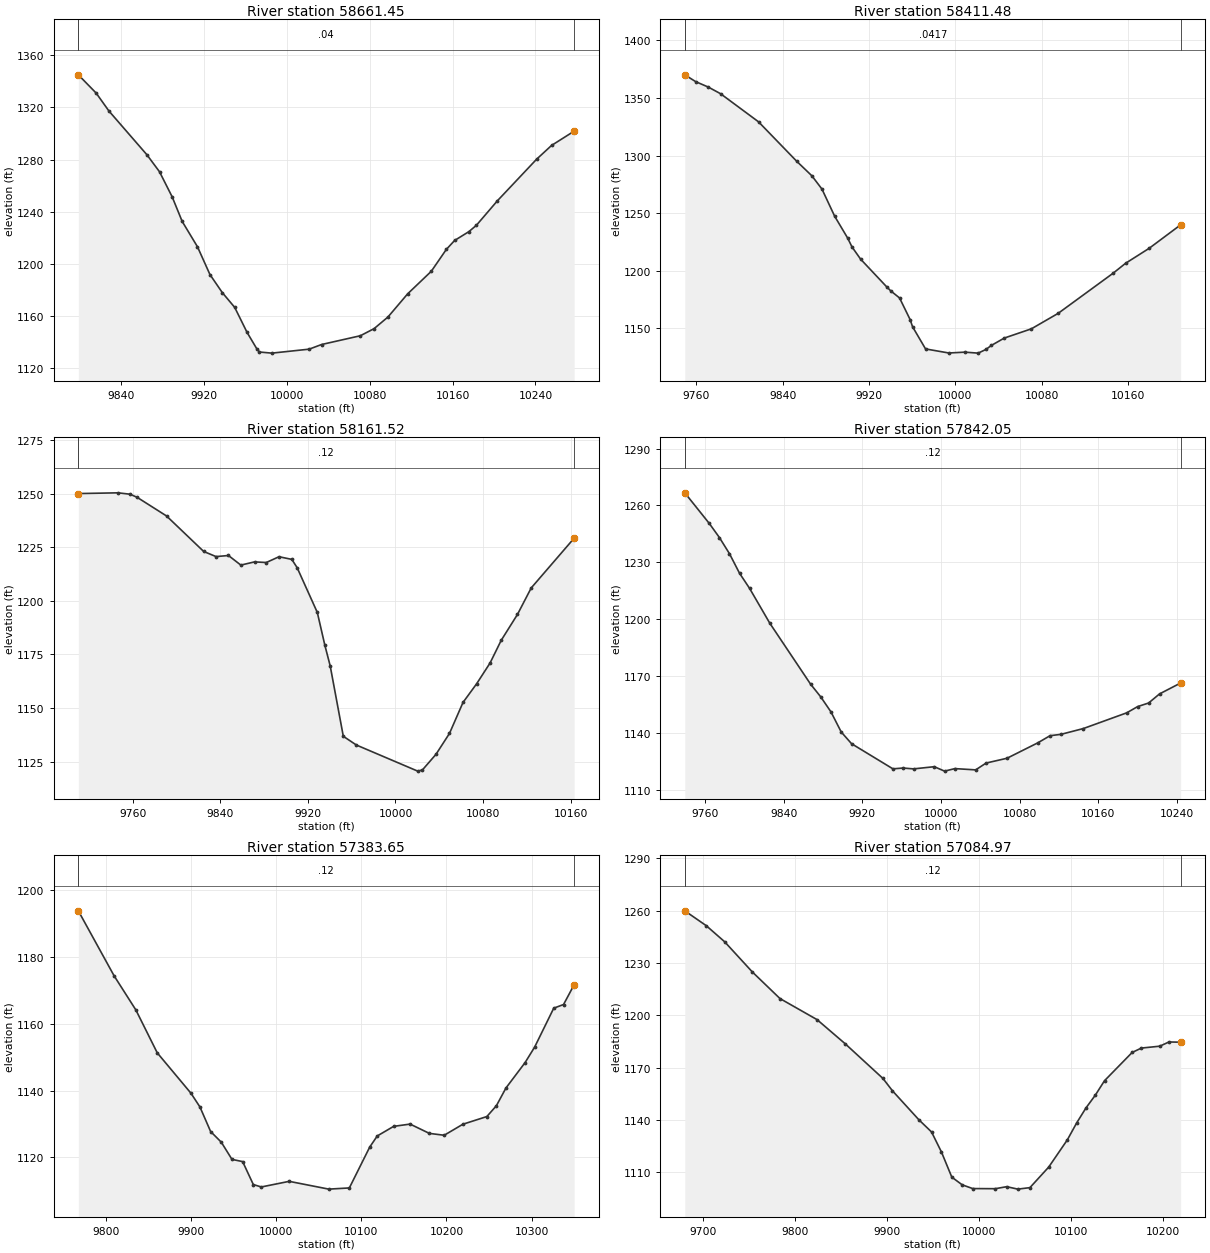
Type RM Length L Ch R = 1 ,58661.45,249.966200,249.966200,249.966200
XS GIS Cut Line= 6
519602.675009332796320.879513885519534.400628479796417.973981404
519469.921082614796515.845430292519446.944756688796546.480103135
519417.860365812796579.255418436519301.507024261796690.201759232
#Sta/Elev= 30
9798.592 1345.079815.8541331.0149828.0791317.3549864.7531283.7499876.9781270.652
9889.2031251.3839898.8611232.5329913.6521213.018 9925.691191.7089937.6491177.813
9949.6081166.4889961.5671147.2369970.8971134.7419973.5261132.2229985.4851131.378
10021.46 1134.4210033.481137.99210070.931144.72710084.181150.17710097.551159.088
 10116.61176.90510139.461194.24910153.971211.04110161.941217.88310175.741224.667
   101831229.55510203.331248.41210241.061280.23210255.571290.85910277.381301.829
#Mann= 3 , 0 , 0
9798.592    0.04       09798.592    0.04       010277.38    0.04       0
#XS Ineff= 2 , 0
       0                               0
Bank Sta=9798.592,10277.38
Exp/Cntr=0.3,0.1

Type RM Length L Ch R = 1 ,58411.48,249.966200,249.966200,249.966200
XS GIS Cut Line= 6
519415.805732796796136.208699414519397.071672342796169.029987114
519342.807648948 796256.73286695519285.199497449796342.629839306
519234.685665716796412.784563076519157.473631835796515.775999589
#Sta/Elev= 30
9749.173 1370.169759.2961364.2229770.9711359.5069782.3241353.7479817.5041329.335
9852.7821295.1649866.9251282.443  9876.31270.874 9888.061247.3089900.0521228.416
9904.1151220.6439912.0921210.0389936.1741186.0599940.0221182.4719948.2151176.279
9957.9751157.5479960.2551151.2889972.2961132.0079993.8711128.47810008.711129.209
10021.04 1128.3610028.181131.52210033.371135.09110045.271141.45110070.371149.471
10095.241162.94810146.131197.79510157.731206.45610179.471219.38410208.691239.824
#Mann= 3 , 0 , 0
9749.173  0.0417       09749.173  0.0417       010208.69  0.0417       0
#XS Ineff= 2 , 0
       0                               0
Bank Sta=9749.173,10208.69
Exp/Cntr=0.3,0.1

Type RM Length L Ch R = 1 ,58161.52,319.463600,319.463600,319.463600
XS GIS Cut Line= 6
519217.164017548795952.054835959519190.140869741796011.556131882
519150.106920416796087.246804131 519111.98782309796150.936831916
519065.231644861796221.187819052518979.733778788796336.172982839
#Sta/Elev= 30
9710.3121250.1739746.4951250.5239757.4781249.8819763.9111248.457 9790.871239.717
9824.808 1223.139836.1211220.7329847.4331221.2459858.746 1216.769871.232 1218.26
9881.9781217.9689893.6321220.6719905.2861219.4339910.1761215.5499928.5951194.642
9935.5141179.2649940.3761169.6449952.3431136.784 9964.311132.698 10020.3 1120.51
10024.621121.07610036.97 1128.3510049.331138.13610061.691152.60910074.051161.269
 10086.41171.03310096.561181.60710111.391193.69310123.971206.086 10163.21229.351
#Mann= 3 , 0 , 0
9710.312    0.12       09710.312    0.12       0 10163.2    0.12       0
#XS Ineff= 2 , 0
       0                               0
Bank Sta=9710.312,10163.2
Exp/Cntr=0.3,0.1

Type RM Length L Ch R = 1 ,57842.05,458.402600,458.402600,458.402600
XS GIS Cut Line= 6
518869.012900752 795800.50539545518850.046766165795887.794527806
518832.831447431795949.934547699518791.983431601796075.363255862
518759.523963733796155.850463979518702.112547439796274.583236813
#Sta/Elev= 30
 9739.411266.6629764.365 1250.519774.6191243.1279784.8721234.6069795.1251224.293
9805.3791216.3069825.8851198.0119867.3581165.9279877.7341159.2049888.1111151.322
9898.5591140.7189909.076 1134.559951.1471121.3149961.6641121.7289972.1821121.286
9993.2171122.43310003.731120.10310014.251121.42910035.37 1120.7610045.981124.354
10067.261126.88610098.571135.00110111.071138.76410122.191139.47610144.951142.532
10189.031150.79810200.171154.09510211.31 1155.9710222.451160.771 10243.91166.511
#Mann= 3 , 0 , 0
 9739.41    0.12       0 9739.41    0.12       0 10243.9    0.12       0
#XS Ineff= 2 , 0
       0                               0
Bank Sta=9739.41,10243.9
Exp/Cntr=0.3,0.1

Type RM Length L Ch R = 1 ,57383.65,298.685400,298.685400,298.685400
XS GIS Cut Line= 6
518202.147820496795973.596686985518395.246380667796122.256022833
 518417.01660951796141.400796823518469.084120299796176.811439882
518539.292954567796219.344634113518685.550964206 796296.07663078
#Sta/Elev= 30
9767.1441193.8659809.2151174.3849834.8271164.1469859.9551151.2999899.533 1139.22
9910.1521135.0799922.701 1127.739935.2511124.531  9947.81119.3799960.3491118.714
9972.8981111.8379982.2931111.11410015.071112.79810061.621110.467 10085.81110.823
10109.75 1123.0610118.641126.40110137.941129.28110157.241129.956 10179.91127.171
10197.341126.60910219.291129.911 10247.51132.21710258.731135.46610269.961140.776
10292.43 1148.3810303.661153.01810326.131164.68710337.691165.79410350.151171.734
#Mann= 3 , 0 , 0
9767.144    0.12       09767.144    0.12       010350.15    0.12       0
#XS Ineff= 2 , 0
       0                               0
Bank Sta=9767.144,10350.15
Exp/Cntr=0.3,0.1

Type RM Length L Ch R = 1 ,57084.97,218.182600,218.182600,218.182600
XS GIS Cut Line= 6
518091.616124064796463.318616748518210.907483041 796456.75485985
518271.267995238796446.233669177518363.888507485796416.736625582
518457.358280003796358.554874033518607.658754051796342.195851535
#Sta/Elev= 30
9679.8291259.8879703.2151251.3599723.217 1242.149753.286 1224.869783.4161209.575
9823.8481197.463  9854.31183.6999895.5871163.7139905.9411156.6299934.6931140.017
9948.4821133.0249959.2451121.5529970.5531107.0989981.8611102.7019993.2821100.563
10017.881100.48810030.31 1101.6410042.37 1100.2410055.571101.09610076.051112.898
10096.321128.50910106.461138.214 10116.61146.82310126.731154.11110136.781162.427
10166.851178.62910176.881181.15110196.931182.23610206.96 1184.6610219.651184.526
#Mann= 3 , 0 , 0
9679.829    0.12       09679.829    0.12       010219.65    0.12       0
#XS Ineff= 2 , 0
       0                               0
Bank Sta=9679.829,10219.65
Exp/Cntr=0.3,0.1

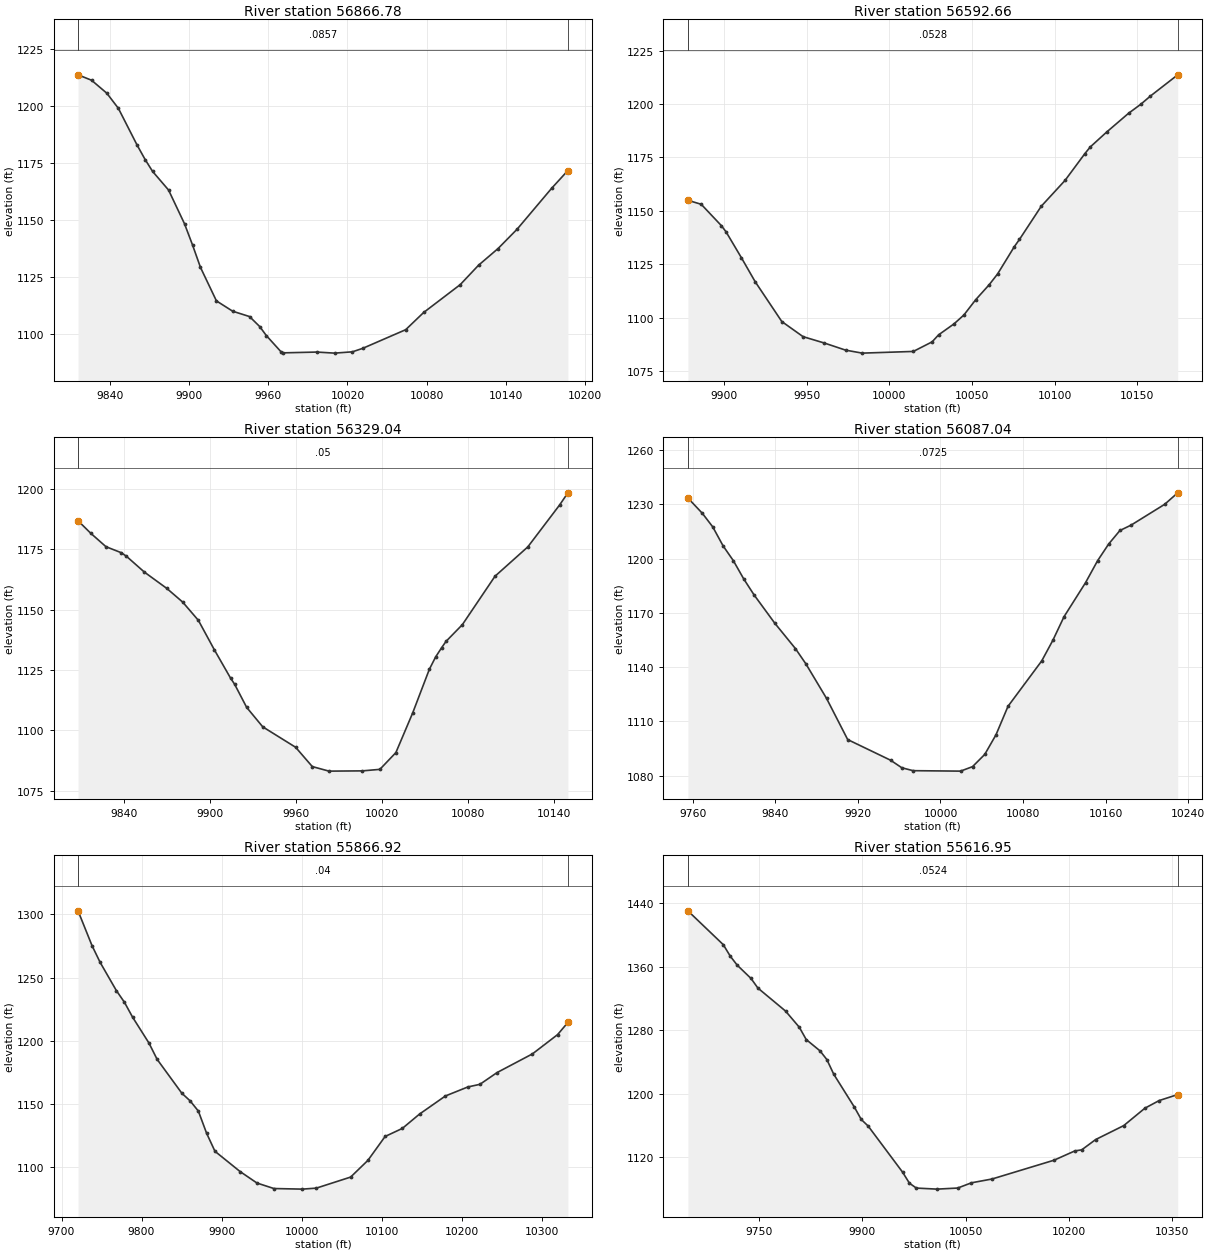
Type RM Length L Ch R = 1 ,56866.78,274.124200,274.124200,274.124200
XS GIS Cut Line= 6
518386.036764381796670.031319177518431.708715903 796644.19714381
518481.568504718796610.392045825518534.438645985 796568.54531501
518591.439216571796517.377811594518673.843266972796438.439859272
#Sta/Elev= 30
9816.0511213.518 9826.271211.1549837.8381205.4729846.5821198.8439860.8161182.687
9866.8931176.375  9872.51171.2179884.5821163.0589896.6631148.2849902.7321138.996
9908.7451129.1789920.827  1114.59933.1391109.9769945.8921107.6379953.5641103.279
9958.6461099.2849969.6771092.2469971.3991091.7419996.9271092.08610010.29 1091.62
10023.75 1092.1910031.521093.69810064.121101.88510077.721109.42210105.421121.628
10119.261130.11810134.051137.43110148.51 1145.9310174.661163.855 10186.91171.597
#Mann= 3 , 0 , 0
9816.051  0.0857       09816.051  0.0857       0 10186.9  0.0857       0
#XS Ineff= 2 , 0
       0                               0
Bank Sta=9816.051,10186.9
Exp/Cntr=0.3,0.1

Type RM Length L Ch R = 1 ,56592.66,263.613700,263.613700,263.613700
XS GIS Cut Line= 5
518618.376378527796848.178944552518663.462597851796816.925751035
518709.533391999796779.546787513518711.054035769796778.247694551
518847.511894888796660.391243146
#Sta/Elev= 30
9878.0771154.9249886.1361153.0779898.3041143.103 9901.211140.1359910.4711128.053
9918.7631116.8759934.9161098.1879947.7931091.093 9960.671088.1149973.5481084.779
9983.6081083.38310014.531084.175 10025.91088.65610029.831091.94610039.121097.057
10045.131101.22210052.331108.43210060.431115.38710065.541120.45310075.731133.304
10078.761136.59110091.971152.14810106.321164.208 10118.41176.81410121.621179.899
10131.611186.92310144.821195.67210152.22  1199.910158.04 1203.7410174.571213.678
#Mann= 3 , 0 , 0
9878.077  0.0528       09878.077  0.0528       010174.57  0.0528       0
#XS Ineff= 2 , 0
       0                               0
Bank Sta=9878.077,10174.57
Exp/Cntr=0.3,0.1

Type RM Length L Ch R = 1 ,56329.04,242.007600,242.007600,242.007600
XS GIS Cut Line= 6
518686.577974014797075.902884791518730.290256453 797060.97709189
518762.438615033797047.682733171518812.467294617797022.387538538
518912.360029286796962.829996723518990.141015134796921.917566461
#Sta/Elev= 30
9808.1991186.8419817.0981181.6359827.6651176.0919838.2321173.6279841.9391172.123
9854.3891165.587 9870.031158.8269881.1281153.1469892.048 1145.589903.2531133.302
9914.4591121.6699917.2861119.1319925.6651109.557 9936.871101.4929959.7891093.022
9971.3991085.0269983.0091083.14410006.291083.24910018.481083.87610029.621090.811
10041.291107.17410052.951125.32510057.321130.43110061.541134.29410064.551136.873
10075.95 1143.8110098.681163.85810121.541176.01210143.761193.42410149.451198.405
#Mann= 3 , 0 , 0
9808.199    0.05       09808.199    0.05       010149.45    0.05       0
#XS Ineff= 2 , 0
       0                               0
Bank Sta=9808.199,10149.45
Exp/Cntr=0.3,0.1

Type RM Length L Ch R = 1 ,56087.04,220.119300,220.119300,220.119300
XS GIS Cut Line= 6
518630.949168445797169.735755657518728.245327096797172.308109388
518802.081177321797184.433087292 518847.40485086797201.549686869
518943.511034017797253.964066823519076.709852496797309.208390017
#Sta/Elev= 30
9755.3341233.4989769.3921224.9849779.3971217.5319789.402 1207.059799.408 1198.79
9809.4131188.7469819.4181179.9169839.4291164.3019859.4841150.2219869.5551141.835
9889.6971122.6099910.1211099.885 9951.671088.4649962.5491084.2889973.4641082.679
10019.471082.42810031.071084.90910042.911091.682 10053.81102.54310065.431118.284
10098.061143.36710108.881154.79810119.711167.85810140.53 1186.6610152.191198.801
10163.011208.09510173.841215.51410184.661218.48910217.141229.97910229.821236.346
#Mann= 3 , 0 , 0
9755.334  0.0725       09755.334  0.0725       010229.82  0.0725       0
#XS Ineff= 2 , 0
       0                               0
Bank Sta=9755.334,10229.82
Exp/Cntr=0.3,0.1

Type RM Length L Ch R = 1 ,55866.92,249.966200,249.966200,249.966200
XS GIS Cut Line= 6
 518497.65412836797339.543769745518553.722201247797347.999858684
518607.046524176797358.996672003518705.160376867797387.067278158
518803.155055771797421.776012226519076.839098221797532.043757598
#Sta/Elev= 30
9720.6351302.8849738.127 1275.359748.2561262.1199768.5151239.8369778.6541230.543
9788.8651218.7349809.2851198.3129819.4961185.4219850.3521158.6519860.6871152.612
9871.0231144.5149881.3581126.9459891.7961112.6929923.229 1096.669944.2861087.599
9965.446 1083.24   100011082.76910018.481083.55810061.37  1092.310082.921105.492
10104.461124.408   101261130.79110147.551142.15810179.861156.45710207.931163.586
10222.951165.65710244.491174.99210288.631189.73710320.051204.96910332.911214.585
#Mann= 3 , 0 , 0
9720.635    0.04       09720.635    0.04       010332.91    0.04       0
#XS Ineff= 2 , 0
       0                               0
Bank Sta=9720.635,10332.91
Exp/Cntr=0.3,0.1

Type RM Length L Ch R = 1 ,55616.95,249.966200,249.966200,249.966200
XS GIS Cut Line= 6
518364.043988641797624.519426083518514.253112507797642.741843609
518886.617091905797658.176230206518941.397819445 797664.68710139
519012.109363645797678.561336435519070.974813729797694.987091372
#Sta/Elev= 30
9646.1521430.1989697.6841387.5799707.7741373.1859717.8281361.8969737.9341345.167
9747.9871333.025  9788.21304.0949808.264 1283.679818.2791268.2569838.3081254.037
9848.322 1243.039858.3371224.5779888.3491183.2019898.3521167.6699908.3561159.427
9958.3711101.4749968.3881087.5349978.4151081.385 10008.5 1080.0610038.561081.425
10058.571088.00610088.571092.80510178.721116.45910208.931128.116   10219 1129.49
 10239.31142.45710280.071159.96410310.881181.88810331.641191.49710358.621199.057
#Mann= 3 , 0 , 0
9646.152  0.0524       09646.152  0.0524       010358.62  0.0524       0
#XS Ineff= 2 , 0
       0                               0
Bank Sta=9646.152,10358.62
Exp/Cntr=0.3,0.1

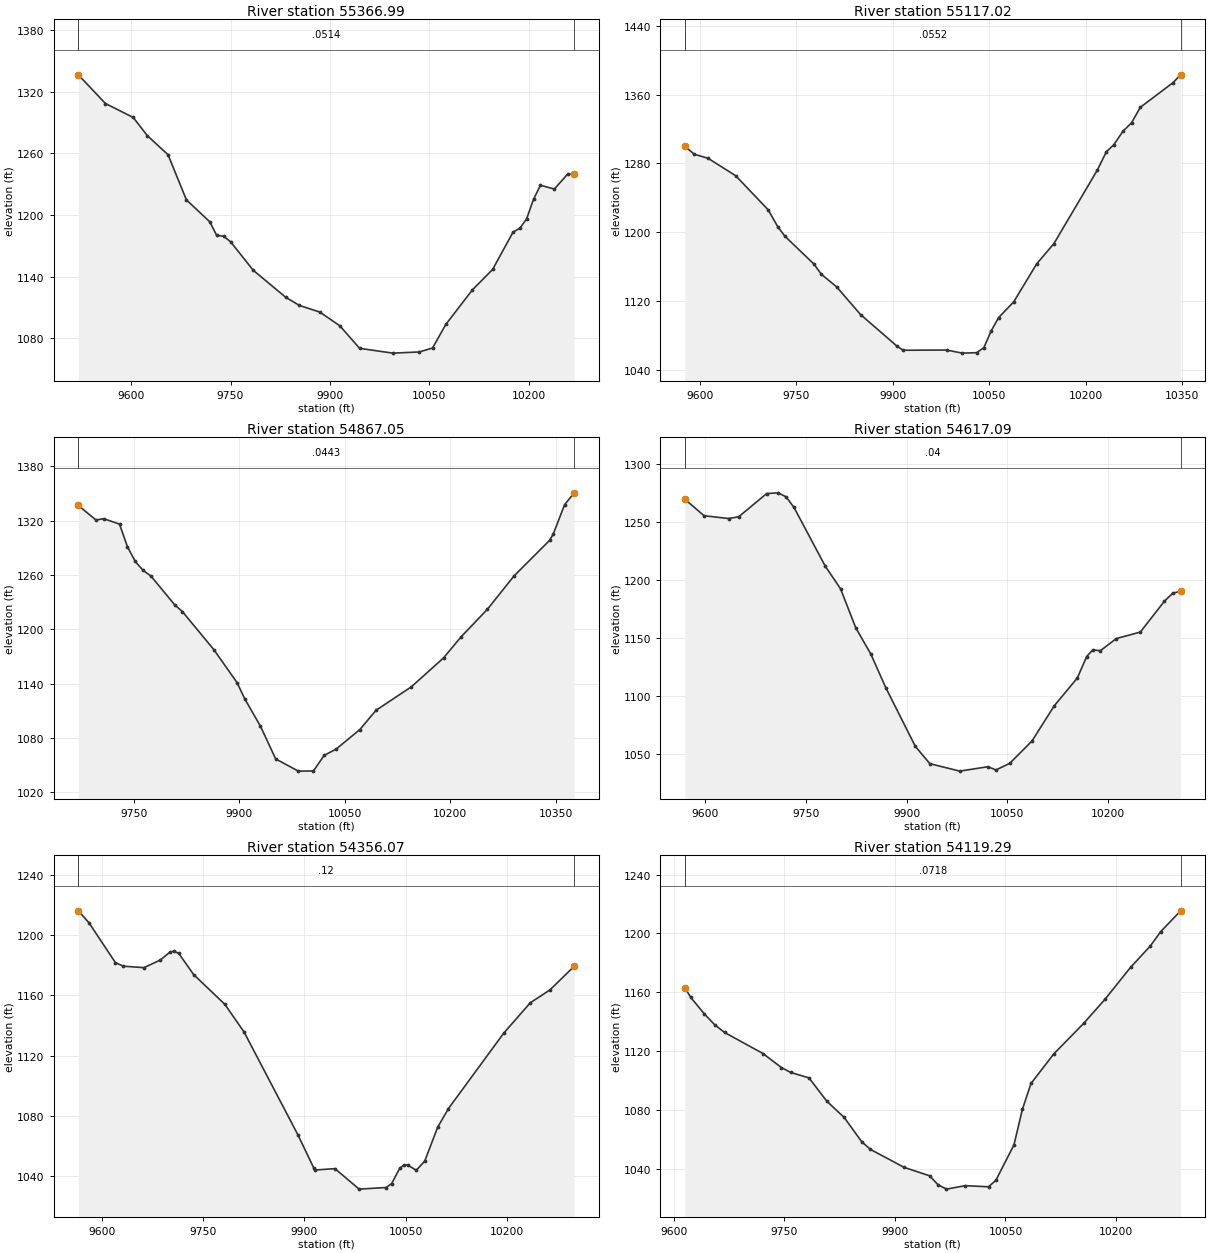
Type RM Length L Ch R = 1 ,55366.99,249.966200,249.966200,249.966200
XS GIS Cut Line= 6
 518305.95329126797785.479066721518529.123680542797856.553599265
 518653.76761174 797889.30147039   518881.804197797898.335645432
518965.602553537797915.949051058 519033.01711534 797938.50157551
#Sta/Elev= 30
9520.226 1336.319561.2051308.4099603.1841294.8259624.1741277.2799655.6591258.612
9683.4141214.6859718.6281193.4339729.1231180.1319739.6181179.3559750.1131173.955
9784.3071146.2289833.477 1119.929853.9491112.0619884.6361105.6299914.8431092.365
9944.8891070.3289994.9051065.67110034.961066.819   100551070.64910075.071093.644
10115.251127.25510145.691147.039 10176.51183.28410186.781187.12510197.061196.282
10207.511215.45410217.971228.91910238.89 1225.2510258.78 1239.62 10268.81239.995
#Mann= 3 , 0 , 0
9520.226  0.0514       09520.226  0.0514       0 10268.8  0.0514       0
#XS Ineff= 2 , 0
       0                               0
Bank Sta=9520.226,10268.8
Exp/Cntr=0.3,0.1

Type RM Length L Ch R = 1 ,55117.02,249.966200,249.966200,249.966200
XS GIS Cut Line= 6
518290.974413741797826.983039896518472.085130619797904.999641457
518551.714508615797961.918510724 518583.43852916797998.142478809
518693.056328007798185.435335832518841.982721219798332.951165361
#Sta/Elev= 30
9576.3281300.0239591.1991290.7249612.4671286.0419655.5121265.7629705.9721226.185
 9720.931206.5339732.0241195.5019777.1571163.1749788.8651151.1899812.2811136.829
9849.674 1104.539906.601 1067.639916.0241063.0589983.4141063.28510007.931059.706
10030.141060.21310041.37 1065.9210052.861085.58810064.361100.93810087.881119.293
10123.681163.50510150.241186.766 10217.91272.29110232.021293.72310243.491301.719
10257.511317.16910271.151327.33310284.78 1345.2410335.321373.70610347.451382.985
#Mann= 3 , 0 , 0
9576.328  0.0552       09576.328  0.0552       010347.45  0.0552       0
#XS Ineff= 2 , 0
       0                               0
Bank Sta=9576.328,10347.45
Exp/Cntr=0.3,0.1

Type RM Length L Ch R = 1 ,54867.05,249.966200,249.966200,249.966200
XS GIS Cut Line= 6
518152.655828341798097.793084738518308.996667926798175.852684625
518488.342106298798252.766549744518522.480828171798270.432450098
518624.539286033 798337.35682445 518762.29836372 798443.53353902
#Sta/Elev= 30
9671.5321336.6429696.5071320.6559707.6841321.9919730.0381316.0649741.2151291.239
9752.3921274.823 9763.571264.9359774.747 1258.689808.2781227.0819819.4551219.402
9863.921 1177.569896.9981141.0589908.0231123.0089930.0741093.1389951.9381056.725
9984.1041043.24410005.561043.42210020.761060.62910037.911067.62710071.531089.201
10094.541110.47610144.581136.29710190.491168.34410215.131191.39310252.691221.963
10290.241258.52710341.03 1298.0610346.311305.08810362.321337.40110375.98 1350.61
#Mann= 3 , 0 , 0
9671.532  0.0443       09671.532  0.0443       010375.98  0.0443       0
#XS Ineff= 2 , 0
       0                               0
Bank Sta=9671.532,10375.98
Exp/Cntr=0.3,0.1

Type RM Length L Ch R = 1 ,54617.09,261.013900,261.013900,261.013900
XS GIS Cut Line= 6
517987.841241979798269.200254576518194.579858556798396.523523132
518257.779723761798427.949093288518471.063836124798519.212382097
 518544.98388462798560.616217537518634.520108839798620.858464152
#Sta/Elev= 30
9569.9161269.4989598.6521255.2819635.0261252.8979650.0871254.3439691.7921274.369
9708.9651274.9919720.7411271.5099732.5171262.3889778.8761212.0179801.8121192.387
9824.4361158.8639846.7721136.3489869.1081107.3669913.0661056.8299934.8781041.877
9979.3181035.48710021.021039.26810033.231036.51210053.561042.14210086.671061.302
10119.961091.69610154.341115.63510168.211134.08110177.261139.87810188.681139.102
10212.161149.52710248.071155.14510283.971181.72510296.271188.52710308.111190.388
#Mann= 3 , 0 , 0
9569.916    0.04       09569.916    0.04       010308.11    0.04       0
#XS Ineff= 2 , 0
       0                               0
Bank Sta=9569.916,10308.11
Exp/Cntr=0.3,0.1

Type RM Length L Ch R = 1 ,54356.07,236.784700,236.784700,236.784700
XS GIS Cut Line= 6
517902.830813274798361.903131787517976.231430875798424.109322174
 518102.46091578 798544.54779318518197.683385765798654.714973488
518270.870480776798757.866875862518400.320231559798900.726199244
#Sta/Elev= 30
 9564.461216.3849580.146 1208.519619.5011181.8769631.3641179.5069661.9931178.549
9686.2611183.659 9699.891188.6779706.1471189.5469713.5191188.0159735.5831173.945
9782.0021154.0539810.3961135.6899890.2211067.2729913.858 1045.129916.3541043.774
 9945.251044.6879981.1991031.03310021.361032.11510029.47 1034.7810041.441044.933
10047.861047.16610053.411047.04510065.991043.59310078.591049.74310097.751072.283
10113.79 1084.7310195.781134.93910235.191155.13610264.411163.73710300.281179.436
#Mann= 3 , 0 , 0
 9564.46    0.12       0 9564.46    0.12       010300.28    0.12       0
#XS Ineff= 2 , 0
       0                               0
Bank Sta=9564.46,10300.28
Exp/Cntr=0.3,0.1

Type RM Length L Ch R = 1 ,54119.29,278.214200,278.214200,278.214200
XS GIS Cut Line= 6
517789.540197935798475.433340395517863.086345318798559.188510552
517903.393156173798613.695622274518059.718136915798883.500314317
518095.792201281 798936.55268401518173.410025493799024.516490207
#Sta/Elev= 30
9614.8941163.2329622.9251156.5329641.5761145.1899655.2121138.0339668.8491132.646
9720.9421118.339 9746.061108.7769758.4981105.4699783.3721101.755 9807.55 1085.91
9831.1931074.8129854.8351058.3919866.6571053.1099912.5231040.8519947.118 1035.11
 9958.531028.9869969.9421026.0499995.5481028.39910027.021027.64710036.97 1032.06
10061.51 1056.1310073.091080.54210084.681097.956 10115.51118.03810156.291138.936
10184.891155.13810219.741176.97110246.48 1191.4710260.721201.31810287.671215.427
#Mann= 3 , 0 , 0
9614.894  0.0718       09614.894  0.0718       010287.67  0.0718       0
#XS Ineff= 2 , 0
       0                               0
Bank Sta=9614.894,10287.67
Exp/Cntr=0.3,0.1

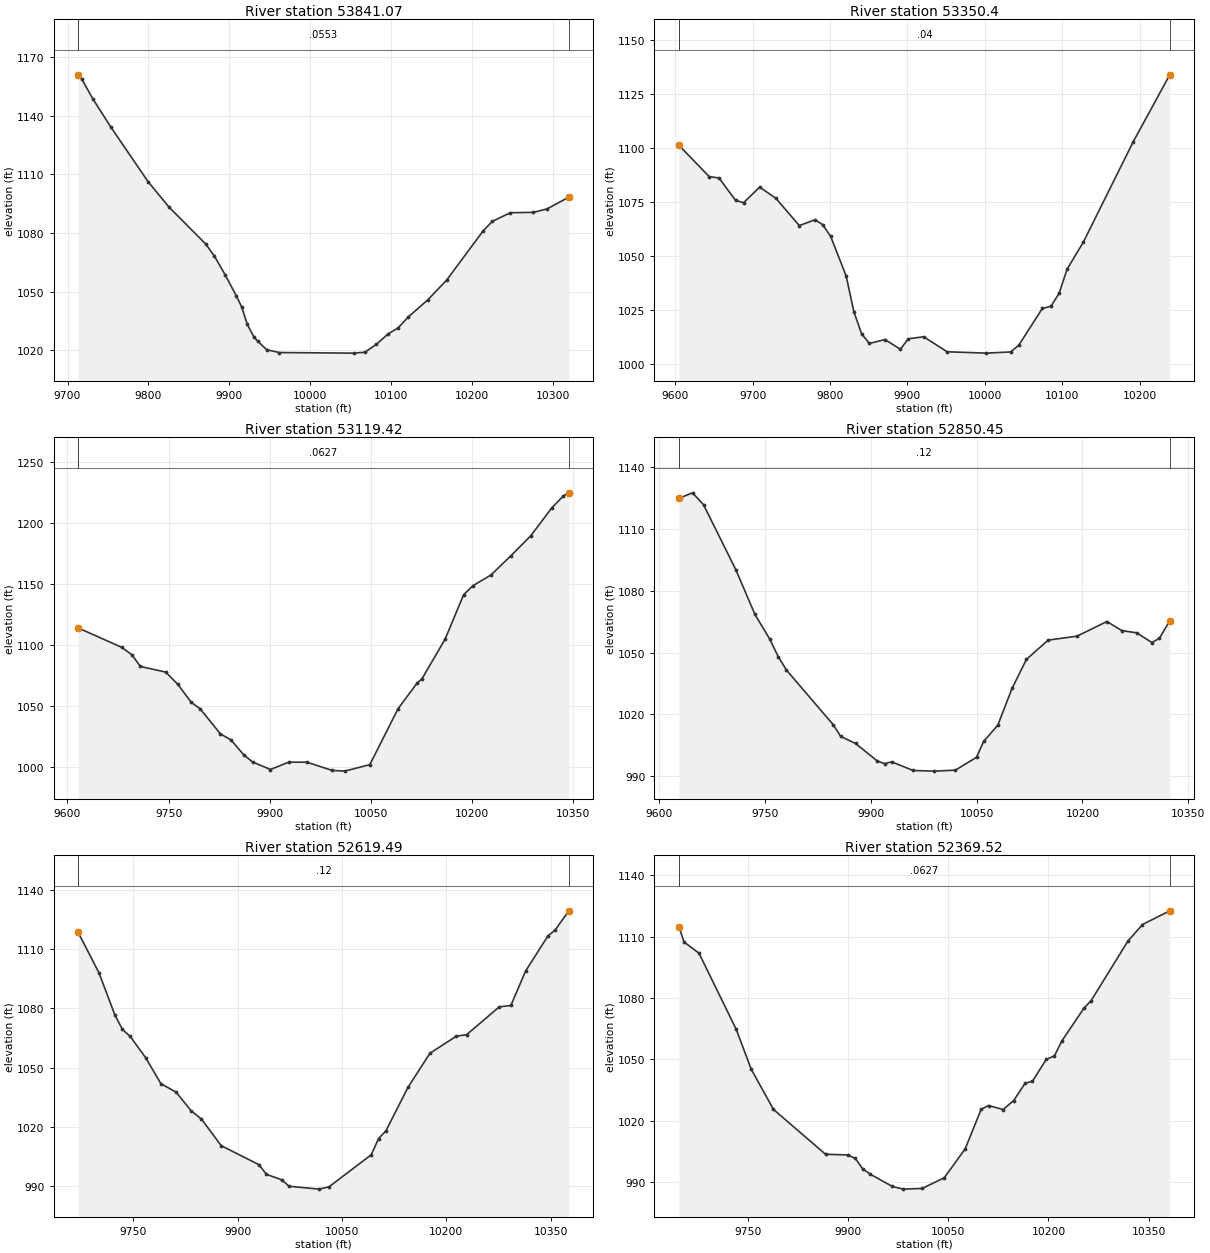
Type RM Length L Ch R = 1 ,53841.07,490.676400,490.676400,490.676400
XS GIS Cut Line= 6
517571.688588798798727.419293372 517679.09753918798830.483443775
517803.059103752798973.068089037517836.215134711799005.652009813
517883.947548175799039.071235278518028.807836623 799115.39964864
#Sta/Elev= 30
9713.0711160.974 9717.571158.8319731.1541148.783 9753.821134.0499799.7381106.167
9825.8371093.0699870.7171074.3769881.6081068.0729895.1441058.3429908.6791047.736
9915.2311042.0889922.1071033.232 9930.571026.553 9935.191024.5349946.0791020.231
9961.5881018.77610053.641018.47510067.661018.94210081.681023.01410096.481028.408
10108.451031.35810121.021036.95710145.151045.75310168.451055.85110213.441080.992
10224.741085.89610247.351090.37510275.711090.54710292.561092.32310319.471098.337
#Mann= 3 , 0 , 0
9713.071  0.0553       09713.071  0.0553       010319.47  0.0553       0
#XS Ineff= 2 , 0
       0                               0
Bank Sta=9713.071,10319.47
Exp/Cntr=0.3,0.1

Type RM Length L Ch R = 1 , 53350.4,230.974200,230.974200,230.974200
XS GIS Cut Line= 6
517407.618327698799268.567352053517524.915566133799311.070724801
 517755.37462047799336.215988061517794.913881452799345.049657751
517905.058979229799376.925589414 518018.06856929 799423.06081871
#Sta/Elev= 30
9604.5761101.2569643.6141086.8179656.4271086.1239677.6651075.8049688.075 1074.69
9708.8941081.9049729.7111076.7829760.1451064.0969780.4341066.7939790.579 1064.47
9800.6841059.0679820.7321040.7519830.7551024.0789840.779 1013.879850.8031009.471
 9870.851011.3059890.8971006.7829900.921 1011.649920.9971012.5779951.2211005.625
10001.961004.99910033.451005.56410043.871008.65410074.321025.69110085.54 1026.74
10095.961032.67410106.381043.90910127.461056.50410191.491102.70110239.021133.946
#Mann= 3 , 0 , 0
9604.576    0.04       09604.576    0.04       010239.02    0.04       0
#XS Ineff= 2 , 0
       0                               0
Bank Sta=9604.576,10239.02
Exp/Cntr=0.3,0.1

Type RM Length L Ch R = 1 ,53119.42,268.976200,268.976200,268.976200
XS GIS Cut Line= 6
517381.342804452799295.976335054517507.289868388799391.169661098
 517591.87082433799461.007611437517662.185422993799524.614965356
517799.041706656799665.419354022517911.738593199 799791.15038275
#Sta/Elev= 30
9615.8271113.9169680.547 1097.989695.6221091.9089708.1571082.3359745.7621077.694
 9763.471067.8069783.7011052.8619796.6691047.7179826.8361027.1029842.5421022.119
9861.5111009.9059874.4791004.1129901.093997.90299928.0621003.9189955.0321003.882
 9992.63997.154610011.07996.574910048.381001.87410090.241047.72610118.151068.478
10125.761072.29710160.021104.73210187.531141.18510201.061148.42210228.121157.321
10257.631173.06910287.321189.60410317.831212.02710335.291222.02210343.421224.571
#Mann= 3 , 0 , 0
9615.827  0.0627       09615.827  0.0627       010343.42  0.0627       0
#XS Ineff= 2 , 0
       0                               0
Bank Sta=9615.827,10343.42
Exp/Cntr=0.3,0.1

Type RM Length L Ch R = 1 ,52850.45,230.956200,230.956200,230.956200
XS GIS Cut Line= 6
517301.947535451799323.755819472517370.201477845799407.032301324
517424.413166606799512.308049106517444.945482711799598.351451569
517456.509734592 799781.88056154517516.140209474799968.607321047
#Sta/Elev= 30
 9628.111124.7999647.3251127.4539662.9431121.6729708.6961090.1599735.8731068.439
9756.9981056.3759768.7551048.0129780.5121041.4639846.7211015.0029857.4131009.282
9878.4111005.8759909.349997.35399919.538996.08199929.671996.97459959.911 992.779
9989.942  992.4610019.95992.931510049.97999.184510059.991006.84810080.051014.722
10100.311032.59310120.56 1046.6210151.371055.99710192.61 1057.9510234.721065.031
10255.771060.64710277.011059.53810298.471054.84310309.191056.88310323.79 1065.38
#Mann= 3 , 0 , 0
 9628.11    0.12       0 9628.11    0.12       010323.79    0.12       0
#XS Ineff= 2 , 0
       0                               0
Bank Sta=9628.11,10323.79
Exp/Cntr=0.3,0.1

Type RM Length L Ch R = 1 ,52619.49,249.966200,249.966200,249.966200
XS GIS Cut Line= 6
517089.579743078799388.389974426517144.257876842799498.860288711
517231.566103691799709.080441163517254.846714657799770.912153426
517308.276465468 799930.79667994517349.613980853800043.137277929
#Sta/Elev= 30
9670.8761118.4749700.9331097.9259723.5241076.8669734.6371069.304 9745.691065.859
9767.7951055.145  9789.91041.9179811.6471037.6739833.3071028.2419848.1791024.034
9876.6291010.5699930.781 1000.999941.612996.07429963.273993.39259974.103990.0606
10017.39988.614410031.54989.800210092.181005.98310102.721014.19410113.261018.074
10144.891040.00210176.521057.29210214.551065.94710229.241066.674 10276.21080.759
10292.811081.44110314.081098.88910345.991116.51910356.631119.64510376.15 1129.29
#Mann= 3 , 0 , 0
9670.876    0.12       09670.876    0.12       010376.15    0.12       0
#XS Ineff= 2 , 0
       0                               0
Bank Sta=9670.876,10376.15
Exp/Cntr=0.3,0.1

Type RM Length L Ch R = 1 ,52369.52,203.374000,203.374000,203.374000
XS GIS Cut Line= 6
516837.780069926799468.145527002516918.408567581799631.967306905
 516992.19981505799784.325156211516993.116057213799786.102935809
517030.286931496799864.512512443517150.903967177800132.214180612
#Sta/Elev= 30
9647.1251114.9249654.7641107.4189677.0551101.9579732.783  1064.79755.074 1045.27
9788.5111025.5029866.4161003.553 9899.751003.2189910.8611001.5699921.972996.4648
9933.083993.84279966.416  987.819982.483986.499410010.85986.835510044.05992.0384
10075.43 1006.2610099.281025.54810110.251027.40410132.181025.44510147.931029.866
10165.09 1038.3210176.051039.28910196.621049.96710208.961051.73910219.931058.984
10252.83 1074.94 10263.81078.73810318.641107.77210340.581115.96410381.391122.676
#Mann= 3 , 0 , 0
9647.125  0.0627       09647.125  0.0627       010381.39  0.0627       0
#XS Ineff= 2 , 0
       0                               0
Bank Sta=9647.125,10381.39
Exp/Cntr=0.3,0.1