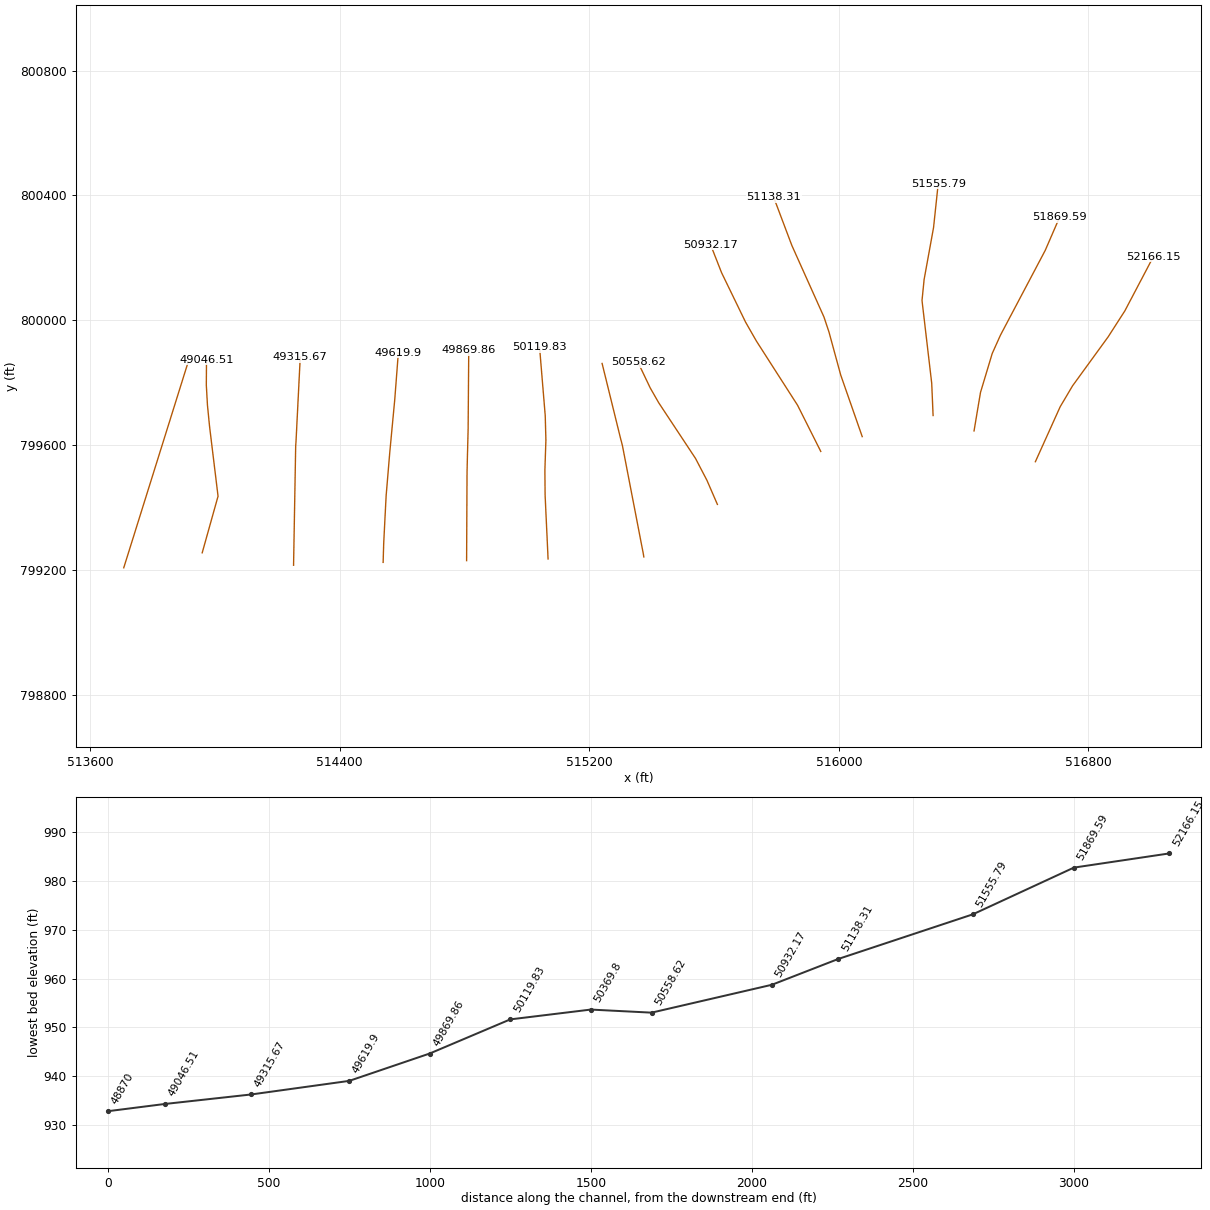
HEC-RAS study 5238_ras.prj: 5238

--- 5238_ras.g01 (geometry) --- (continued)

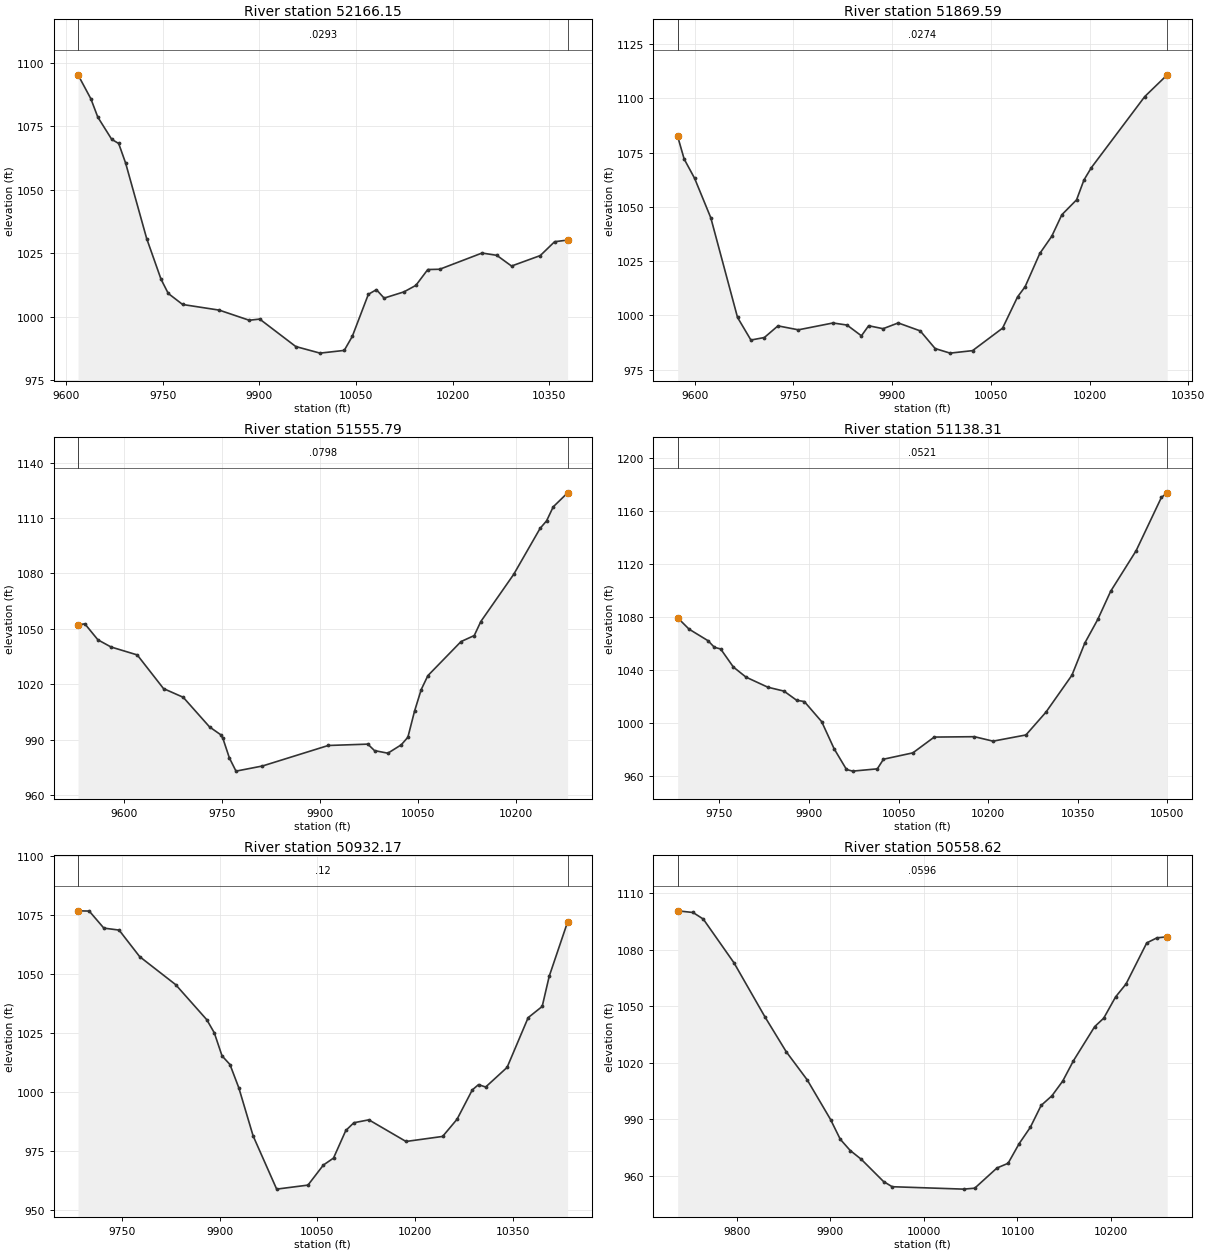
Type RM Length L Ch R = 1 ,52166.15,296.558300,296.558300,296.558300
XS GIS Cut Line= 6
516629.795674581799546.527707463516709.293032422 799722.77846816
516748.837600105799789.590073524516863.100704707 799946.84093133
516916.565667683800030.015710113517007.703749936800203.160004014
#Sta/Elev= 30
9618.4921095.3139638.435 1085.869649.2311078.6199670.8231069.8719681.6191068.237
9692.4151060.4999725.0781030.7619747.425 1014.689758.5981009.1029780.9441004.743
9837.804 1002.529884.285998.52929900.592998.99469956.587988.16449994.221985.5667
10031.83986.638910044.31992.160710069.281008.75810081.761010.58910093.751007.268
10124.551009.72110143.051012.28110161.541018.52910180.041018.64410245.83 1025.04
 10268.71024.13310291.581019.913 10336.21024.03810358.45  1029.510378.661030.152
#Mann= 3 , 0 , 0
9618.492  0.0293       09618.492  0.0293       010378.66  0.0293       0
#XS Ineff= 2 , 0
       0 9828.39                       0
Bank Sta=9618.492,10378.66
Exp/Cntr=0.3,0.1

Type RM Length L Ch R = 1 ,51869.59,313.799700,313.799700,313.799700
XS GIS Cut Line= 6
 516433.17434924799645.190327431516453.852654615799768.490003829
516491.447713576799893.420255147516517.730403109799951.948194807
 516661.31938658 800223.83387128516707.718632343800330.883468609
#Sta/Elev= 30
9574.1051082.4469583.9911072.0139599.9021063.1119624.4981044.9579665.134999.0848
9685.451988.69029705.884989.84739726.555995.21059757.561 993.392 9810.19996.5388
 9831.47995.58819853.394990.63079864.356 995.275 9886.28993.90939909.285 996.561
9942.742992.90249965.434984.76799988.126982.664710022.28983.813610067.88994.1605
10090.681008.55810102.071013.19910124.44 1028.5310142.591036.43910157.981046.365
10180.351053.22610191.531062.34910202.691067.98510283.931100.742 10318.11110.754
#Mann= 3 , 0 , 0
9574.105  0.0274       09574.105  0.0274       0 10318.1  0.0274       0
#XS Ineff= 2 , 0
       0 9791.07                       0
Bank Sta=9574.105,10318.1
Exp/Cntr=0.3,0.1

Type RM Length L Ch R = 1 ,51555.79,417.482800,417.482800,417.482800
XS GIS Cut Line= 6
516301.935813621799694.571769885516297.499407644799797.933691182
516266.408972892800063.291943295516273.192072231800130.715605184
 516303.36710335800296.904400924516318.264628998800436.911040197
#Sta/Elev= 30
9530.2911052.204 9540.721052.7649560.7251044.1099580.7531040.244 9620.811035.951
9660.9681017.7499691.1231013.0419731.364997.01629748.111992.86689751.562991.0123
9761.661980.23289771.761973.11469812.158975.88589912.779986.98269973.277987.7118
9983.482 984.21510003.89982.810710024.29987.328110034.48991.431810044.681005.564
10054.881017.23510065.071024.75710115.691043.16610135.93 1046.43   101461054.023
10196.281079.548 10236.51104.34110246.561108.49610256.621116.02110278.65 1123.61
#Mann= 3 , 0 , 0
9530.291  0.0798       09530.291  0.0798       010278.65  0.0798       0
#XS Ineff= 2 , 0
       0                               0
Bank Sta=9530.291,10278.65
Exp/Cntr=0.3,0.1

Type RM Length L Ch R = 1 ,51138.31,206.136000,206.136000,206.136000
XS GIS Cut Line= 6
516074.772349735799626.956052112516005.868065853799824.254831392
515967.942499051799963.087969946515952.081436203800010.506034507
515849.245533797800239.567295568515790.878814137800394.281226796
#Sta/Elev= 30
 9680.261079.6569699.3731071.067 9731.151062.3429741.7421057.3949752.3341056.082
9773.5191042.5189794.703 1034.889831.2181027.2889858.2571024.3439879.4421017.443
9892.2751016.4839921.3351001.324 9942.21980.84029962.875 965.241 9973.19964.0012
10014.49965.722210024.83972.987810073.99977.778110109.74989.676610176.97989.9674
 10208.2986.603810263.24991.274510296.611008.39310340.191036.30210361.831060.629
10383.46 1078.3810404.991099.58310447.641130.183   104901170.42210499.741173.859
#Mann= 3 , 0 , 0
 9680.26  0.0521       0 9680.26  0.0521       010499.74  0.0521       0
#XS Ineff= 2 , 0
       0                               0
Bank Sta=9680.26,10499.74
Exp/Cntr=0.3,0.1

Type RM Length L Ch R = 1 ,50932.17,373.551300,373.551300,373.551300
XS GIS Cut Line= 6
515941.932071466799579.457316822515867.621757316799727.350340821
515735.512126437799933.340352233515700.644071322799994.334966258
515623.911737986800152.473664885515588.940321379800241.545476343
#Sta/Elev= 30
9682.3171076.6049699.5041076.505 9721.991069.2819745.4211068.4469777.0861057.182
9832.313 1045.349880.183 1030.46 9891.661024.9419903.5451015.1689915.734 1011.51
9929.3191001.6449951.315981.26399987.479958.726110035.58960.4328 10059.2968.9197
10074.81971.876210093.69983.566410106.09986.842910129.12988.079810186.17978.9096
10242.42 981.04610264.56988.319110287.981000.74110297.541002.98810308.531001.972
10341.461010.28610373.811031.35710395.38  1036.110406.171048.89210434.441071.917
#Mann= 3 , 0 , 0
9682.317    0.12       09682.317    0.12       010434.44    0.12       0
#XS Ineff= 2 , 0
       0                               0
Bank Sta=9682.317,10434.44
Exp/Cntr=0.3,0.1

Type RM Length L Ch R = 1 ,50558.62,188.827400,188.827400,188.827400
XS GIS Cut Line= 6
515610.559865881799409.653818219515576.951330261799487.134465799
515540.408571373799557.074232527515422.572100798799735.292069104
515395.074004182799783.366947011515356.106304955799865.033467592
#Sta/Elev= 30
9736.9121100.5729753.3561099.6889764.3051096.2089797.1521072.9839830.2621044.286
9852.8281025.9459875.3931010.9139900.299989.92119910.642979.47839921.329973.4886
9933.061968.86619956.866957.07369966.066954.310110042.42953.029710054.31953.5303
10078.07964.240910089.96966.727310101.84977.203110113.72 985.82310125.26997.4102
10136.781002.506 10148.31010.30310159.821021.13510182.451039.18110192.081043.639
10204.791054.92510215.951061.79510238.081083.567   102491086.25810259.971086.786
#Mann= 3 , 0 , 0
9736.912  0.0596       09736.912  0.0596       010259.97  0.0596       0
#XS Ineff= 2 , 0
       0                               0
Bank Sta=9736.912,10259.97
Exp/Cntr=0.3,0.1

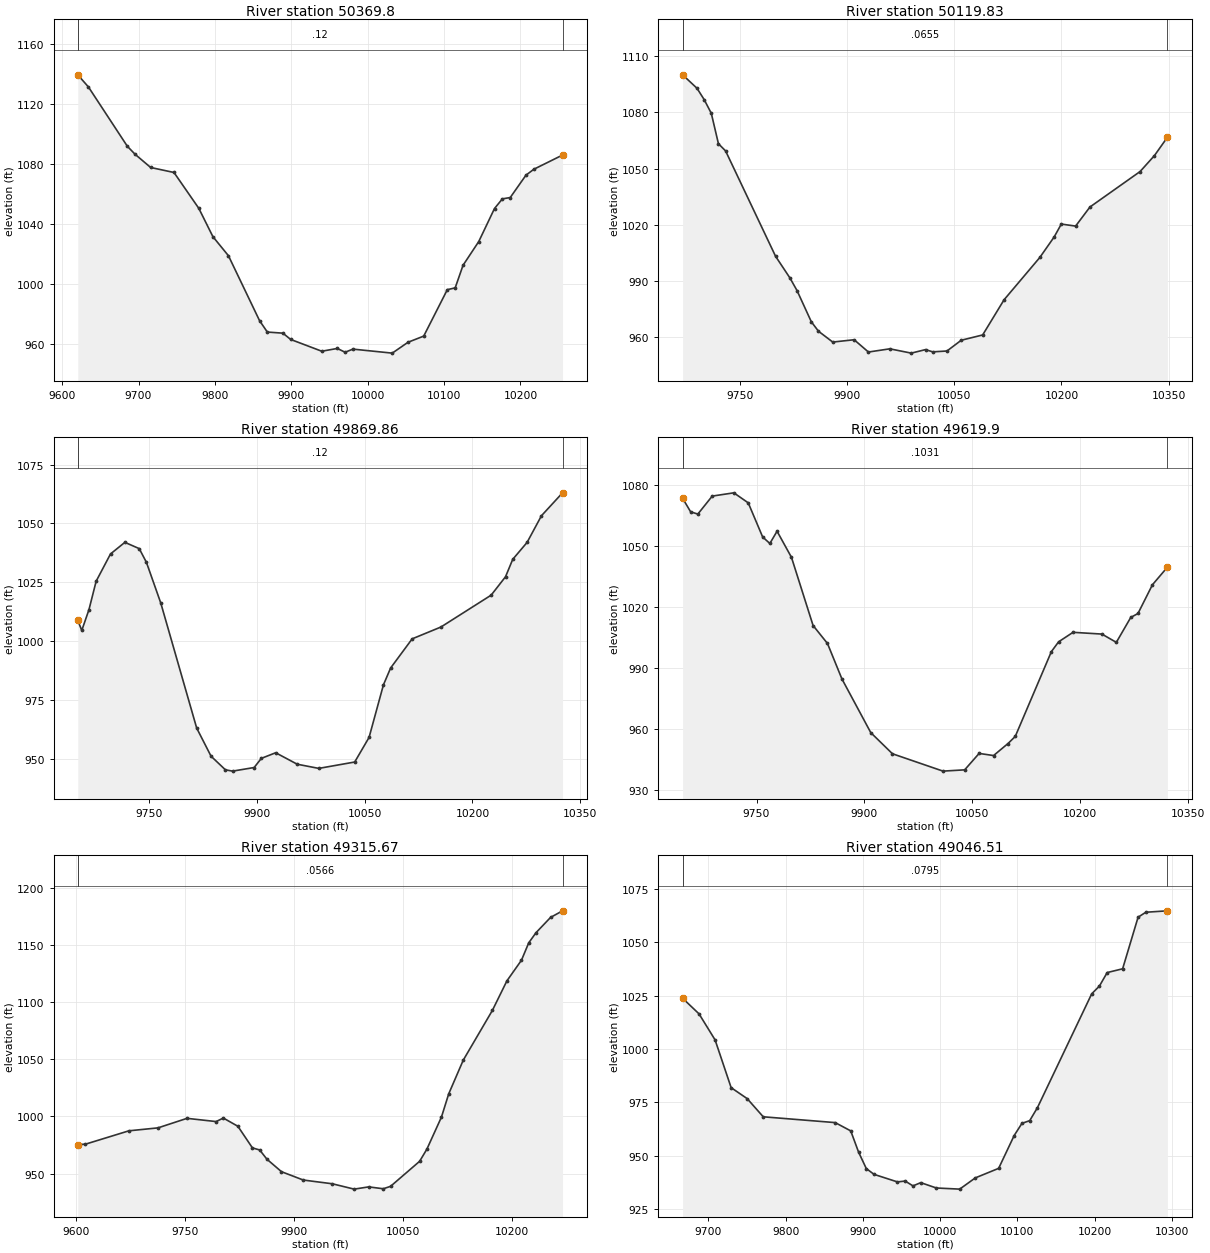
Type RM Length L Ch R = 1 , 50369.8,249.966200,249.966200,249.966200
XS GIS Cut Line= 6
515374.737187182    799241.25485515373.318733274799250.257731563
515306.227854951799597.689743527515302.430355535799612.838751984
515301.725635542799614.710481059515241.010432146 799861.49991823
#Sta/Elev= 30
9620.4181139.1799634.3621131.0929685.2851091.572 9695.471086.209 9715.841077.412
9746.3941074.081 9778.891050.1749797.3171031.3169817.6871018.5889858.426975.3067
9868.611967.7014 9888.98966.96719899.165962.78089939.904954.92259960.273956.7776
9970.458954.24049980.643956.329110032.19953.657310052.79960.893610073.39965.0112
10104.28995.966210114.58997.155110124.881012.22210145.471028.06610166.071050.069
10176.371056.49310186.671057.37710207.261072.29210217.561076.23210255.151085.707
#Mann= 3 , 0 , 0
9620.418    0.12       09620.418    0.12       010255.15    0.12       0
#XS Ineff= 2 , 0
       0                               0
Bank Sta=9620.418,10255.15
Exp/Cntr=0.3,0.1

Type RM Length L Ch R = 1 ,50119.83,249.966200,249.966200,249.966200
XS GIS Cut Line= 6
 515067.86750073 799234.86173154515058.302904055799439.929510098
 515057.63587779799519.996850514515060.869075621799615.477232587
515058.774774651799693.593287062515040.562574522 799913.04590907
#Sta/Elev= 30
9669.1341100.0859689.2941092.9169699.3051086.8879709.3161079.5689719.3271063.325
9729.3371059.5099799.4141003.2829819.435991.78879829.446985.02499849.468968.3848
9859.479963.34169879.495957.55259909.496958.78999929.497952.23679959.501953.9459
9989.521951.651710009.53953.533410019.54952.330510039.55952.783110059.56958.5242
10089.57961.342110119.58980.1169 10169.71002.69310189.751013.60810199.781020.485
10219.831019.40910239.891029.58310310.161048.50210330.261057.004 10348.41066.756
#Mann= 3 , 0 , 0
9669.134  0.0655       09669.134  0.0655       0 10348.4  0.0655       0
#XS Ineff= 2 , 0
       0                               0
Bank Sta=9669.134,10348.4
Exp/Cntr=0.3,0.1

Type RM Length L Ch R = 1 ,49869.86,249.966200,249.966200,249.966200
XS GIS Cut Line= 6
 514806.70891599 799229.42092768514808.116195682799512.642002722
514809.660456266 799577.88574889514809.767778091799579.882867321
514811.582875317799651.649130014514813.571604765 799904.37109493
#Sta/Elev= 30
9650.5131008.7069656.0931004.4869666.0931013.3269676.0931025.4049696.0931036.994
9716.0931041.9249736.0941039.2579746.0941033.4369766.0941016.1239816.095962.9732
9836.095951.02029856.095945.23119866.095944.68019896.096946.21239906.096950.0998
9926.096952.49279956.102947.61229986.111 945.84310036.13948.552610056.13959.0171
10076.14981.361910086.14988.519910116.141000.90710156.141005.92610226.141019.484
10246.15 1027.3110256.151034.69510276.151041.89910296.151053.22710325.521062.972
#Mann= 3 , 0 , 0
9650.513    0.12       09650.513    0.12       010325.52    0.12       0
#XS Ineff= 2 , 0
       0                               0
Bank Sta=9650.513,10325.52
Exp/Cntr=0.3,0.1

Type RM Length L Ch R = 1 , 49619.9,304.229600,304.229600,304.229600
XS GIS Cut Line= 6
514539.138414225 799223.84654224514540.963691187 799284.80866896
514548.744751561799437.238898477514560.491694838799576.898996624
514576.369723012799745.439813429514587.880304114799895.745949691
#Sta/Elev= 30
9647.2291073.3559658.3871066.6889668.3921065.593  9688.41074.4379718.4231076.045
9738.4491071.1059758.4751054.3189768.4881051.1239778.5011057.1499798.5271044.301
9828.5661010.7529848.5921001.8999868.635984.47279908.776958.03019938.882947.6325
10009.14939.086710039.27939.717410059.36947.797110079.45946.755710099.54952.6803
10109.58956.1565 10159.8997.903910169.851002.726 10189.91007.39610230.021006.535
10250.081002.45910270.141014.72910280.171016.66510300.231030.78810321.03 1039.44
#Mann= 3 , 0 , 0
9647.229  0.1031       09647.229  0.1031       010321.03  0.1031       0
#XS Ineff= 2 , 0
       0                               0
Bank Sta=9647.229,10321.03
Exp/Cntr=0.3,0.1

Type RM Length L Ch R = 1 ,49315.67,269.152300,269.152300,269.152300
XS GIS Cut Line= 5
514252.070684861799214.655967433514258.864082529799597.136977728
514259.630257372799607.778916937514259.851120425799609.766684406
514273.470867965799881.463405783
#Sta/Elev= 30
 9602.49975.39899612.836975.66059672.845987.40239712.851989.97699752.858998.3385
9792.864995.50669802.865 998.5859822.869991.38719842.872972.44249852.873970.6192
9862.875962.51229882.878951.59259912.883944.27919952.889 940.9989982.894936.3115
10002.94938.272610022.97936.636110032.98938.740310073.03960.699310083.04971.3696
10103.07999.445510113.081019.813 10133.11049.34610173.151092.88710193.181118.808
 10213.21136.86810223.221152.12810233.231161.00410253.251174.38310269.741180.155
#Mann= 3 , 0 , 0
 9602.49  0.0566       0 9602.49  0.0566       010269.74  0.0566       0
#XS Ineff= 2 , 0
       0                               0
Bank Sta=9602.49,10269.74
Exp/Cntr=0.3,0.1

Type RM Length L Ch R = 1 ,49046.51,176.516700,176.516700,176.516700
XS GIS Cut Line= 6
513959.221254021 799254.52224043514010.020403864799435.939202499
513982.808348789799659.633137072 513976.09093463799727.410686314
513972.414126597799792.232447521513973.018330923799872.897699291
#Sta/Elev= 30
9666.6641023.7559687.9291016.4469708.699 1004.259729.468981.88799750.237976.7507
9771.007968.24229864.172965.51919884.287961.63379894.345951.77739904.403943.9977
 9914.46941.27539944.676937.7445 9954.76938.13789964.843935.88239974.927937.3939
9995.094934.890910025.34934.3604 10045.5939.620110075.74944.091210095.85959.4783
 10105.9965.168710115.95966.4388   10126972.553810196.191025.836 10206.21029.489
10216.221035.79410236.221037.56410256.221061.71710266.221064.04810294.141064.712
#Mann= 3 , 0 , 0
9666.664  0.0795       09666.664  0.0795       010294.14  0.0795       0
#XS Ineff= 2 , 0
       0                               0
Bank Sta=9666.664,10294.14
Exp/Cntr=0.3,0.1

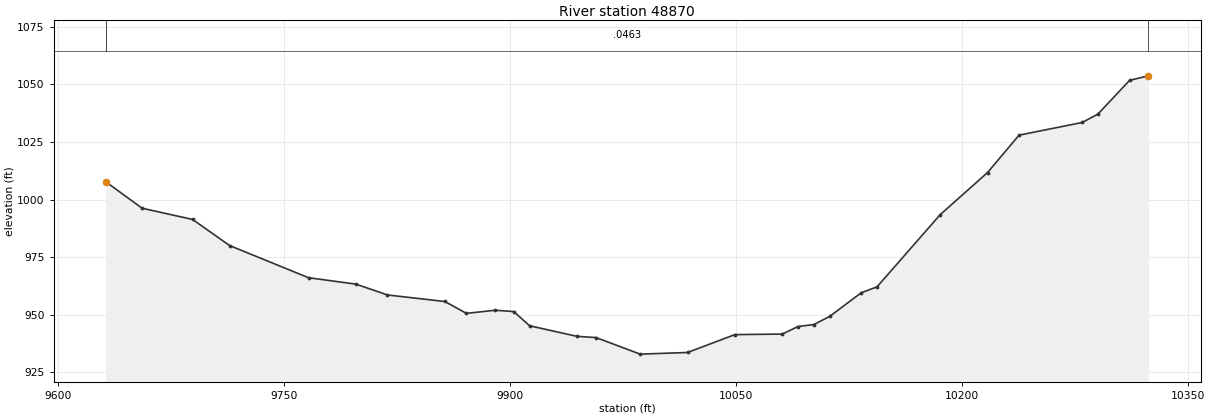
Type RM Length L Ch R = 1 ,   48870,69.963400,69.963400,69.963400
XS GIS Cut Line= 2
513707.773454267799206.526438921513914.478242278799866.941736475
#Sta/Elev= 30
9631.6261007.7469655.819996.22749689.297991.36439713.853 980.0339766.245966.0541
 9797.68963.28089818.637958.57099856.687955.73749871.029950.58519890.165951.9411
9902.464951.35619912.942945.20059944.378940.60849957.122940.06029986.291932.8848
10017.73933.596510049.16941.3572 10080.6 941.58810091.07944.875710101.55 945.716
10112.03949.239610132.99959.522510143.47962.079610185.38993.406310216.821011.713
10237.771027.96410279.691033.45810290.161037.13710311.121051.76510323.631053.714
#Mann= 3 , 0 , 0
9631.626  0.0463       09631.626  0.0463       010323.63  0.0463       0
#XS Ineff= 2 , 0
       09863.432                       0
Bank Sta=9631.626,10323.63
Exp/Cntr=0.3,0.1