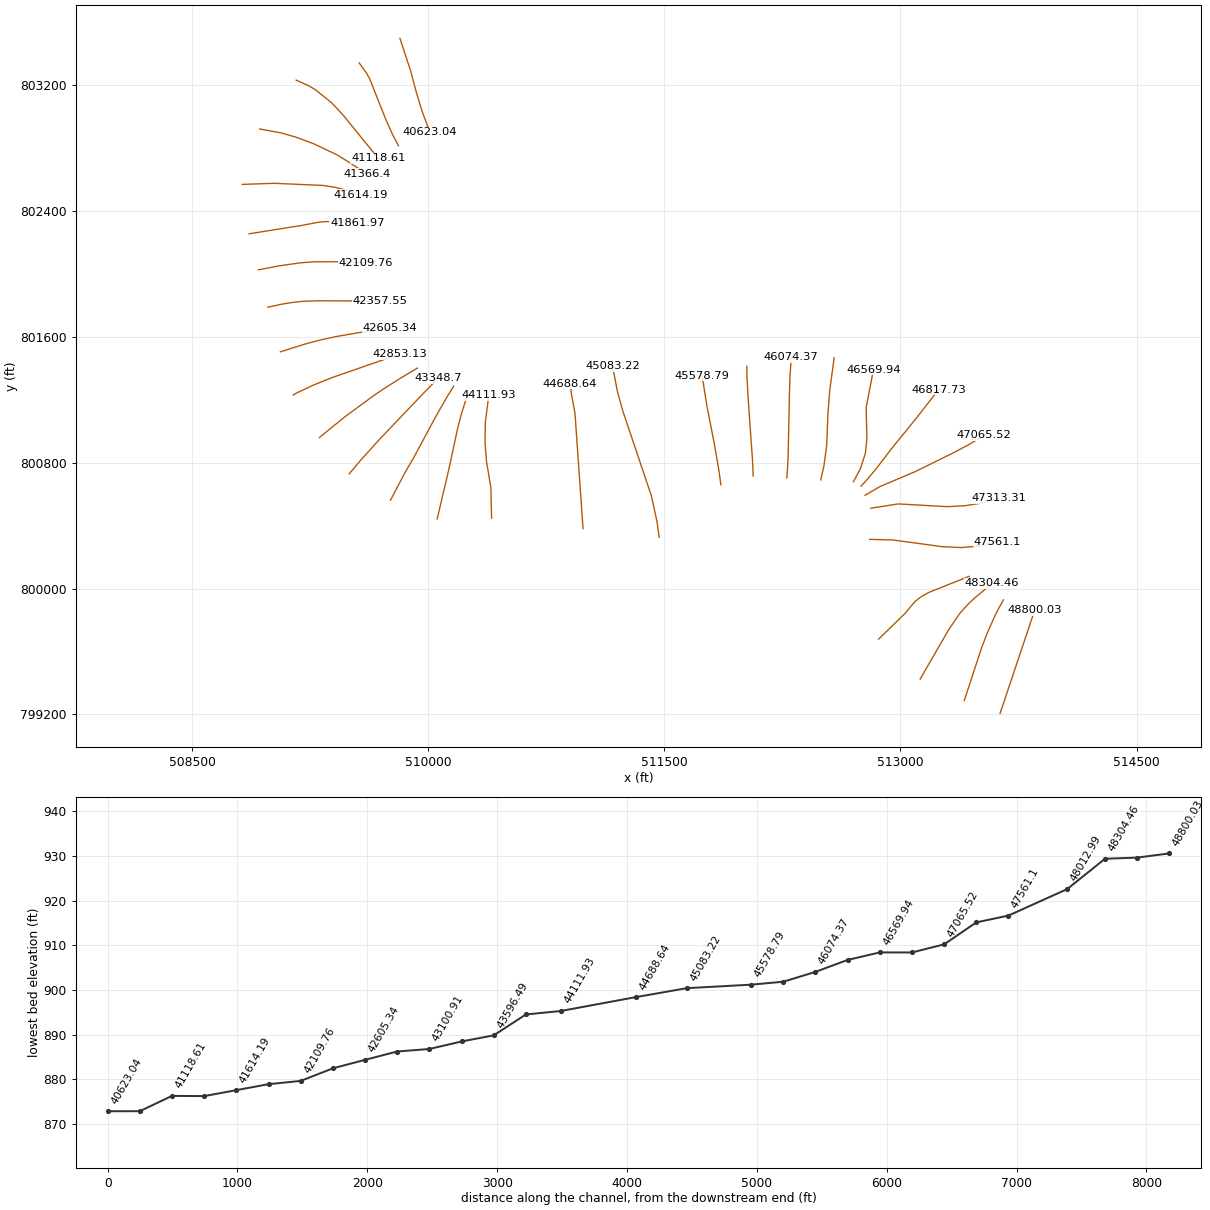
HEC-RAS study 5238_ras.prj: 5238

--- 5238_ras.g01 (geometry) --- (continued)

Type RM Length L Ch R = 3 ,48828.85,,,
BEGIN DESCRIPTION:
END DESCRIPTION:
Bridge Culvert--1,0,-1,-1, 0
Deck Dist Width WeirC Skew NumUp NumDn MinLoCord MaxHiCord MaxSubmerge Is_Ogee
22.481700,25.000000,2.6,0, 47, 47, , , 0.95, 0, 0,0,,
 9633.50 9645.27 9655.73 9666.18 9676.64 9687.10 9697.55 9708.01 9718.47 9731.88
 9739.38 9749.83 9760.29 9766.10 9770.75 9781.20 9791.66 9800.32 9802.12 9812.57
 9823.03 9833.49 9843.94 9854.40 9868.76 9875.31 9885.77 9896.22 9906.68 9927.59
 9954.64 9954.6410014.6410014.6410066.0710076.4610086.9110097.4910108.0810118.67
10129.2510139.8410145.8710150.4310161.0110171.6010175.39
 1014.35 1011.80 1008.58 1005.49 1003.59 1000.76  998.41  994.08  990.54  983.89
  981.22  979.95  980.11  979.65  978.66  974.92  972.55  971.37  971.05  966.81
  964.76  963.88  963.15  962.17  961.38  960.48  949.82  948.97  948.57  947.60
  946.67  946.67  944.50  944.50  942.66  942.22  941.59  942.16  946.06  948.60
  953.48  959.50  961.54  963.27  972.70  979.88  982.84
   14.35   11.80    8.58    5.49    3.59    0.76   -1.59   -5.92   -9.46  -16.11
  -18.78  -20.05  -19.89  -20.35  -21.34  -25.08  -27.45  -28.63  -28.95  -33.19
  -35.24  -36.12  -36.85  -37.83  -38.62  -39.52  -50.18  -51.03  -51.43  -52.40
  -53.33  943.17  941.00  -55.50  -57.34  -57.78  -58.41  -57.84  -53.94  -51.40
  -46.52  -40.50  -38.46  -36.73  -27.30  -20.12  -17.16
 9633.50 9645.27 9655.73 9666.18 9676.64 9687.10 9697.55 9708.01 9718.47 9731.88
 9739.38 9749.83 9760.29 9766.10 9770.75 9781.20 9791.66 9800.32 9802.12 9812.57
 9823.03 9833.49 9843.94 9854.40 9868.76 9875.31 9885.77 9896.22 9906.68 9927.59
 9979.59 9979.5910039.5910039.5910066.0710076.4610086.9110097.4910108.0810118.67
10129.2510139.8410145.8710150.4310161.0110171.6010175.39
 1014.35 1011.80 1008.58 1005.49 1003.59 1000.76  998.41  994.08  990.54  983.89
  981.22  979.95  980.11  979.65  978.66  974.92  972.55  971.37  971.05  966.81
  964.76  963.88  963.15  962.17  961.38  960.48  949.82  948.97  948.57  947.60
  945.77  945.77  943.60  943.60  942.66  942.22  941.59  942.16  946.06  948.60
  953.48  959.50  961.54  963.27  972.70  979.88  982.84
   14.35   11.80    8.58    5.49    3.59    0.76   -1.59   -5.92   -9.46  -16.11
  -18.78  -20.05  -19.89  -20.35  -21.34  -25.08  -27.45  -28.63  -28.95  -33.19
  -35.24  -36.12  -36.85  -37.83  -38.62  -39.52  -50.18  -51.03  -51.43  -52.40
  -54.23  942.27  940.10  -56.40  -57.34  -57.78  -58.41  -57.84  -53.94  -51.40
  -46.52  -40.50  -38.46  -36.73  -27.30  -20.12  -17.16
BR Coef=-1 , 0 , 0 ,, 0 ,,,0.8,0,1,0,
WSPro=,,,, 1 ,,,, 0 ,,,, 0 ,,,,-1 ,-1 ,-1 , 0 , 0 , 0 , 0 , 0
BC Design=,, 0 ,, 0 ,,,,,,

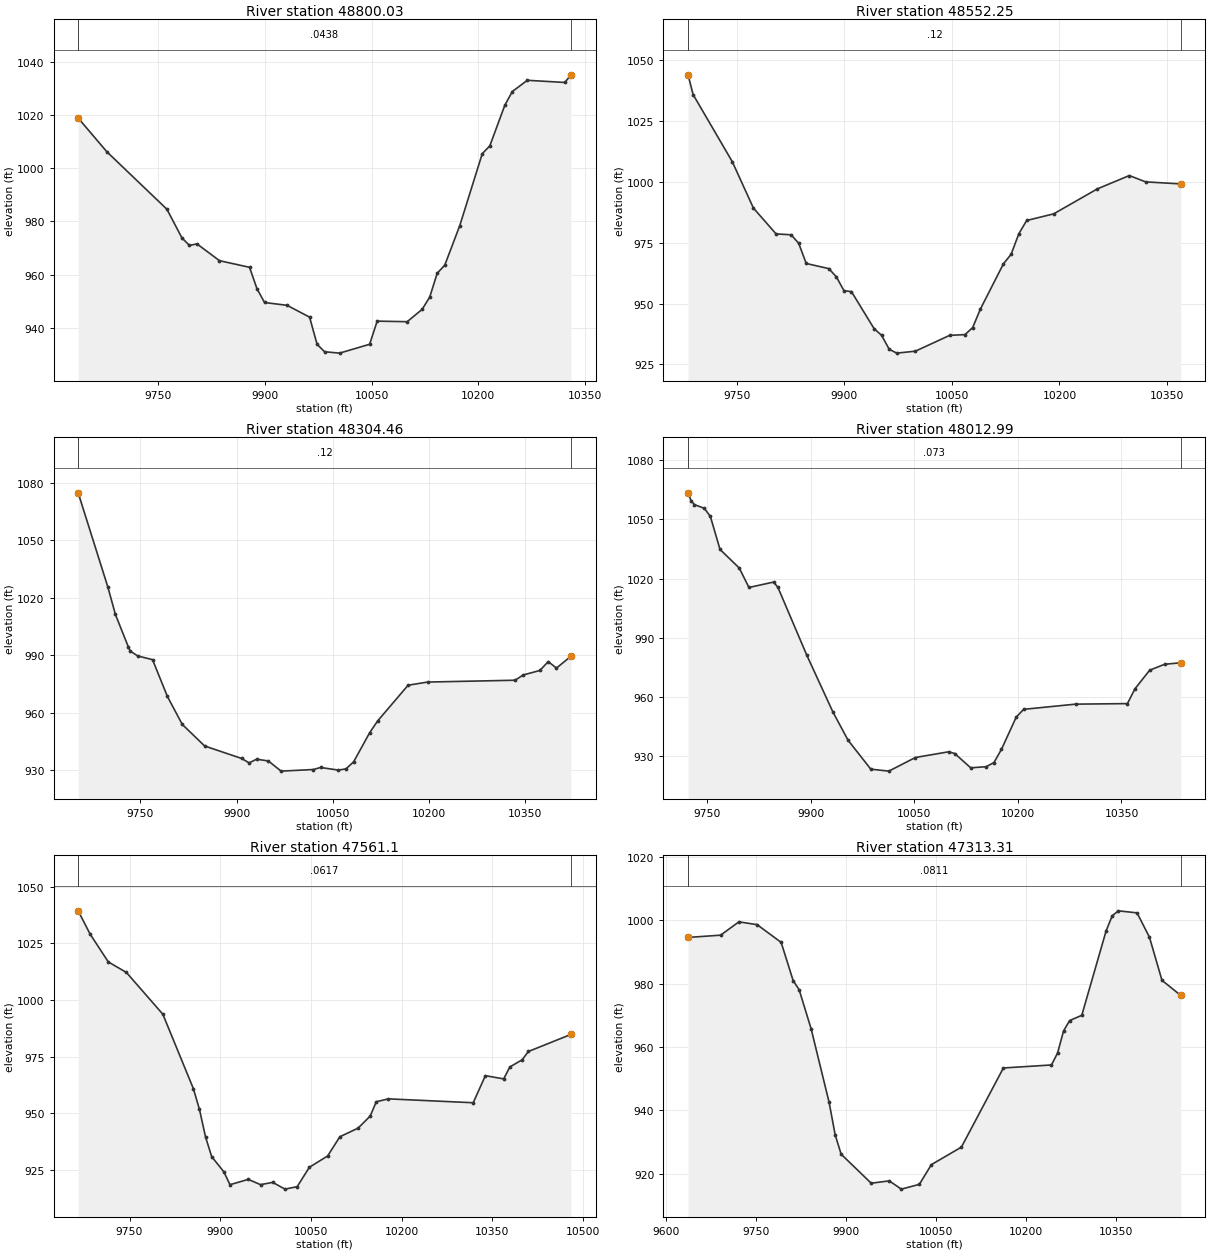
Type RM Length L Ch R = 1 ,48800.03,247.787900,247.787900,247.787900
XS GIS Cut Line= 2
513633.228242278799206.785486475513853.280325621 799863.03548646
#Sta/Elev= 30
9637.8241018.8159678.1291006.1619762.507984.57759783.602973.81079794.149971.0066
9804.696971.57769836.338965.27039878.527962.78449889.074954.70219899.621949.5711
9931.263948.51499962.904944.07699973.452 933.8579983.999931.074110005.09930.5622
10047.28 933.89710057.83942.575310100.02942.362710121.11947.018110131.66 951.613
10142.21960.581210152.75963.560810173.85978.424110205.491005.47110216.041008.363
10237.131023.61410247.681028.77810268.771033.00110321.511032.18310329.981035.053
#Mann= 3 , 0 , 0
9637.824  0.0438       09637.824  0.0438       010329.98  0.0438       0
#XS Ineff= 2 , 0
       09878.143                       0
Bank Sta=9637.824,10329.98
Exp/Cntr=0.3,0.1

Type RM Length L Ch R = 1 ,48552.25,247.787800,247.787800,247.787800
XS GIS Cut Line= 6
513405.790510279799288.251171947513515.756346447799623.504905004
513554.173603309799722.725607332 513598.13205773799821.306217407
513621.323544581799867.901917541513654.530288675799927.881287463
#Sta/Elev= 30
9681.6641043.9289688.7661035.8029743.3241008.2879772.956989.17999804.528978.5804
9825.575978.23299836.099974.72599846.622966.44769878.194964.32719888.717960.9365
9899.241955.28869909.765954.87439941.336939.6828 9951.86936.92169962.384931.2291
9972.907929.6213    9999930.420910046.82936.924310068.27937.226610078.99940.1352
10089.71947.711510121.88966.291610132.61970.215910143.38978.645610154.33984.0972
10192.03986.825710252.95997.075610297.631002.55710320.37 999.96210369.44999.1204
#Mann= 3 , 0 , 0
9681.664    0.12       09681.664    0.12       010369.44    0.12       0
#XS Ineff= 2 , 0
       0                               0
Bank Sta=9681.664,10369.44
Exp/Cntr=0.3,0.1

Type RM Length L Ch R = 1 ,48304.46,291.470500,291.470500,291.470500
XS GIS Cut Line= 6
513125.685961306799424.968868452513309.036689685799742.276427299
513377.335365922799841.632433017513419.998626068799890.311029454
513468.678427423799937.210876068513582.390948435800032.082556726
#Sta/Elev= 30
9653.3371074.8919699.6861025.5079711.2641011.3689731.341994.4378 9734.42992.1615
9745.998989.60489769.154987.65059792.311968.43369815.467953.79369850.387942.5062
9908.091935.9682 9919.67933.67049931.248935.60089949.592934.68399969.433929.3621
10019.84 930.20710030.93931.271810058.66929.899910070.52930.542910082.51934.2547
10107.37949.4269 10119.8955.581210167.28974.284510197.62975.938310333.86976.8944
10346.78 979.66510372.61982.002210385.53 986.62710398.45983.253710420.91989.4071
#Mann= 3 , 0 , 0
9653.337    0.12       09653.337    0.12       010420.91    0.12       0
#XS Ineff= 2 , 0
       0                               0
Bank Sta=9653.337,10420.91
Exp/Cntr=0.3,0.1

Type RM Length L Ch R = 1 ,48012.99,451.893000,451.893000,451.893000
XS GIS Cut Line= 6
   512861.867523799678.551966459513027.824335689799840.406295654
513092.613591869799917.445777834513132.780876553799948.758997447
513183.947236334799976.660999788513436.344628791800077.119369362
#Sta/Elev= 30
9722.256 1063.469726.6321059.5169731.4911057.4959745.8141055.6059754.5691051.503
9768.5371034.8179796.4741025.3599810.4421015.5369846.0711018.2799852.3481015.647
9894.253981.23659932.006952.54249954.072 938.1729986.931923.561310013.05922.5638
10051.49 929.46310099.74 932.35710108.43931.484610131.69924.236510154.21 924.814
10165.31926.927610176.05933.515410197.52949.884310208.26953.847110283.44956.4752
10358.62956.748610369.36964.171510390.83973.660510412.39976.657710435.87977.4222
#Mann= 3 , 0 , 0
9722.256   0.073       09722.256   0.073       010435.87   0.073       0
#XS Ineff= 2 , 0
       0                               0
Bank Sta=9722.256,10435.87
Exp/Cntr=0.3,0.1

Type RM Length L Ch R = 1 , 47561.1,247.787900,247.787900,247.787900
XS GIS Cut Line= 6
 512805.27959104800312.069866463512952.692562324800308.423689464
513265.182666961800265.863348051  513385.6399633800259.881755864
 513500.12959867800269.854214636513612.564183632800298.448184084
#Sta/Elev= 30
9665.0811039.2989684.8471029.0269714.8821016.7959744.8861012.1279805.072 993.739
9855.537960.9799 9865.64 951.7989875.743939.63469885.847930.98479906.054924.2524
9916.157918.59869946.468920.93989966.674918.61169986.881 919.62810007.08916.6432
10027.26917.725910047.44926.269310077.67931.2574 10097.8939.7159   10128943.5184
10148.06948.8496 10158.1 955.15210178.16956.426510318.38954.716210338.53 966.649
10368.81965.223710378.99970.491410399.37973.633910409.67977.306810479.98 984.823
#Mann= 3 , 0 , 0
9665.081  0.0617       09665.081  0.0617       010479.98  0.0617       0
#XS Ineff= 2 , 0
       0                               0
Bank Sta=9665.081,10479.98
Exp/Cntr=0.3,0.1

Type RM Length L Ch R = 1 ,47313.31,247.787800,247.787800,247.787800
XS GIS Cut Line= 6
512812.303715425800509.904198608512985.631782131800537.312188582
513296.668079114800520.099813077513408.834511468800525.587056533
513516.007067895800543.000520293513624.797738672800574.208765834
#Sta/Elev= 30
9636.867 994.6319691.151995.34329721.651 999.5549752.002998.66899792.108993.0742
9812.161980.97729822.163978.10339842.163965.73579872.179942.47889882.191932.2933
9892.204926.14499942.348916.97639972.468917.71969992.548915.109310022.64 916.618
10042.69922.847210092.79928.386410162.81953.387710243.03954.339510253.12958.0958
 10263.2965.100910273.29 968.37210293.53970.017610334.23996.762610344.411001.489
10354.731003.03510385.751002.39110406.43994.691410427.28981.084910458.66 976.308
#Mann= 3 , 0 , 0
9636.867  0.0811       09636.867  0.0811       010458.66  0.0811       0
#XS Ineff= 2 , 0
       0                               0
Bank Sta=9636.867,10458.66
Exp/Cntr=0.3,0.1

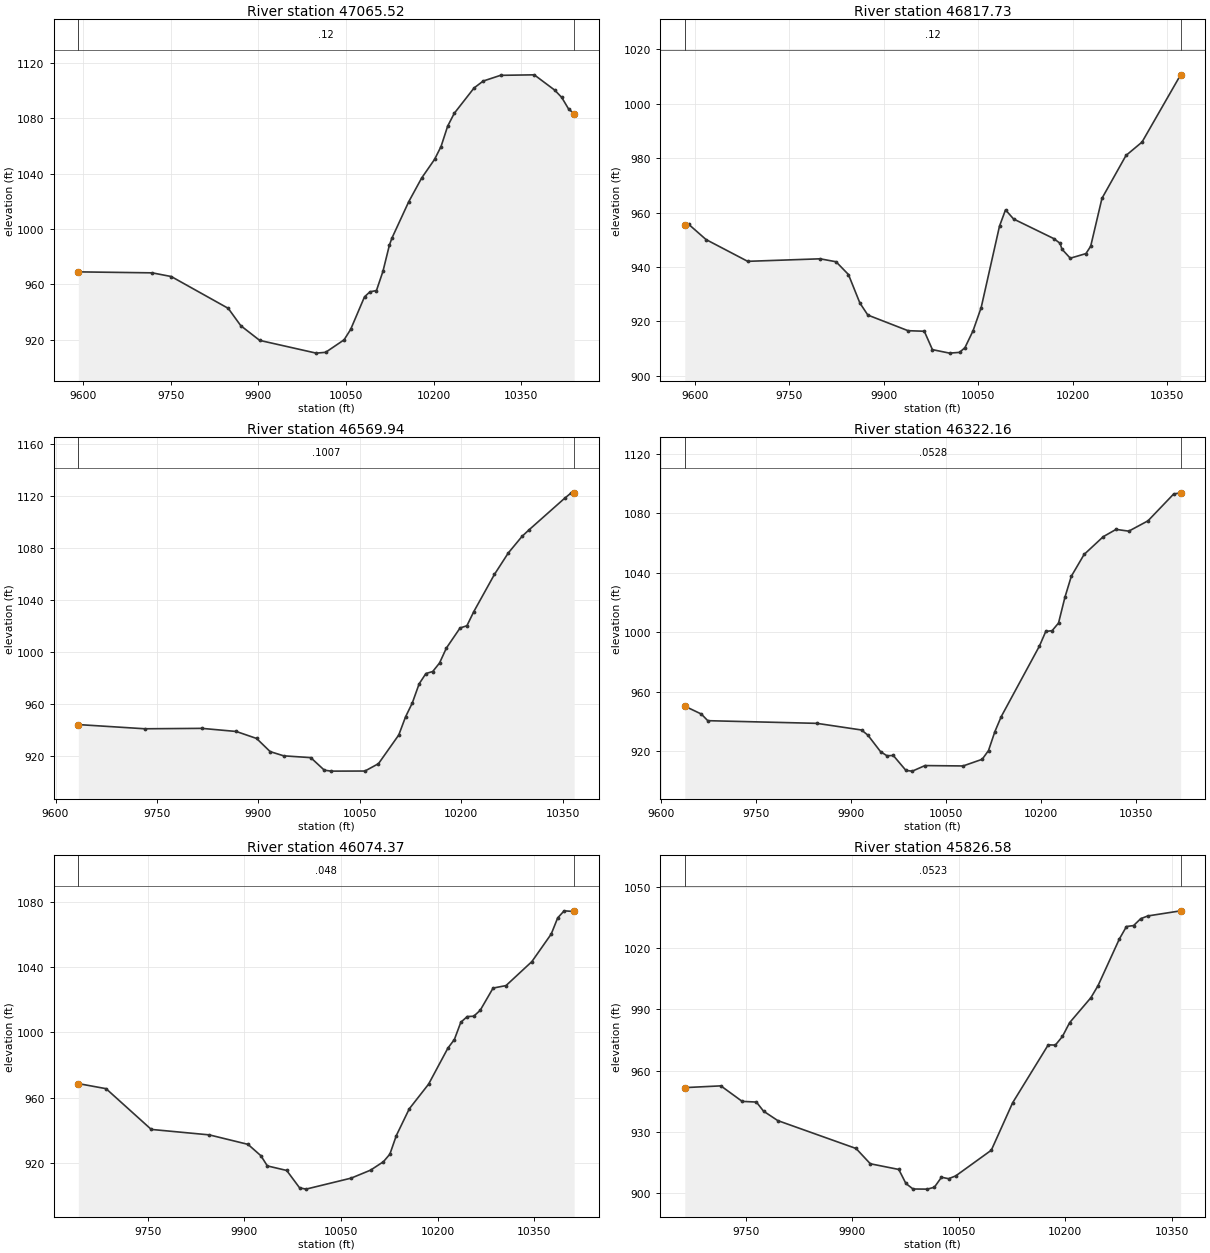
Type RM Length L Ch R = 1 ,47065.52,247.787900,247.787900,247.787900
XS GIS Cut Line= 6
512775.676112912800592.316304257512868.421874444800646.866097947
 513094.74734062800742.835693486513335.193568358800861.167624783
513439.489923818800916.689681955513532.815002075800974.333669898
#Sta/Elev= 30
9591.507 968.9689718.088968.25649750.723965.59259848.342942.57749869.899930.0026
9902.235919.4033    9999910.191610015.15910.770710046.81919.810210058.01927.3219
10081.81950.9247 10091.2954.550810102.26955.452110113.33969.258210124.39988.2059
10128.57   993.210157.581019.71910179.711036.85110201.841050.344 10212.91059.623
10224.221074.32510235.551083.63310269.541102.00210285.111106.97510314.851111.115
 10372.61111.48210407.791100.38110419.721095.11210431.661086.63210440.981083.415
#Mann= 3 , 0 , 0
9591.507    0.12       09591.507    0.12       010440.98    0.12       0
#XS Ineff= 2 , 0
       0                               0
Bank Sta=9591.507,10440.98
Exp/Cntr=0.3,0.1

Type RM Length L Ch R = 1 ,46817.73,247.787800,247.787800,247.787800
XS GIS Cut Line= 6
512749.925871037800650.254348512512784.977079158800688.207403837
 512843.16935083800757.172040113512951.111970152800897.545715226
513096.603952318 801076.52399972513243.128500893 801263.20609371
#Sta/Elev= 30
9584.471955.40199590.931955.62369618.155950.09529684.274942.09019799.318943.0168
9824.547 941.9349844.206937.24289862.391926.76769875.006922.35249938.826916.6137
  9964.6916.41449977.486909.658710004.65908.376310020.51908.651710029.09 910.378
10041.97916.589310054.85925.094110083.97955.031310093.49960.993810106.38957.6298
 10170.3950.419610180.09948.703510183.01946.572710196.29943.237110221.15944.9322
10228.68947.635210246.58965.227910284.71980.973410310.14985.880410371.421010.588
#Mann= 3 , 0 , 0
9584.471    0.12       09584.471    0.12       010371.42    0.12       0
#XS Ineff= 2 , 0
       0                               0
Bank Sta=9584.471,10371.42
Exp/Cntr=0.3,0.1

Type RM Length L Ch R = 1 ,46569.94,247.787900,247.787900,247.787900
XS GIS Cut Line= 6
512701.696229786800678.144693186512745.302855506800759.890538731
 512777.34841469800857.964343187512787.222052314800954.774365461
512782.271481857 801149.18068318512828.732480013801389.631998399
#Sta/Elev= 30
9633.736944.22179731.977940.99019816.412941.30319867.313938.91119897.412933.5316
9917.443923.42069937.476920.16869977.544 918.7749997.578909.1269 10007.6908.3873
10057.69908.4586 10077.7914.132910107.72936.233310117.72 950.12910127.76960.8869
10137.83975.576710147.89983.531810157.95985.064510168.02991.617810178.121003.106
10198.381018.579 10208.51020.28910218.631031.11510249.231059.82410269.641076.275
 10290.11089.12510300.391094.12610353.131118.46710362.331122.37210367.141122.616
#Mann= 3 , 0 , 0
9633.736  0.1007       09633.736  0.1007       010367.14  0.1007       0
#XS Ineff= 2 , 0
       0                               0
Bank Sta=9633.736,10367.14
Exp/Cntr=0.3,0.1

Type RM Length L Ch R = 1 ,46322.16,247.787800,247.787800,247.787800
XS GIS Cut Line= 6
512494.100750891 800689.91557085512513.738992095800776.199917486
512531.565363779800907.697930704512539.895353256801113.829371798
512551.034273877801258.135927666512579.167629538801465.770427362
#Sta/Elev= 30
 9637.85950.32489663.823945.06679674.107940.5826 9846.32938.78679916.605934.3222
 9926.64930.8399 9946.66919.73229956.669917.03969966.678917.20159986.683907.1448
9996.683 906.70510016.69910.438110076.73910.176610106.82914.645610116.84920.5355
10126.87933.2255 10136.9943.327210197.08990.648710207.111000.48810217.171001.044
10227.251006.14710237.33 1023.43 10247.41037.55210267.55 1052.1910297.78 1064.14
10317.931069.03710338.091067.86710368.381074.80510408.911092.83810419.821093.599
#Mann= 3 , 0 , 0
 9637.85  0.0528       0 9637.85  0.0528       010419.82  0.0528       0
#XS Ineff= 2 , 0
       0                               0
Bank Sta=9637.85,10419.82
Exp/Cntr=0.3,0.1

Type RM Length L Ch R = 1 ,46074.37,247.787800,247.787800,247.787800
XS GIS Cut Line= 6
512278.392911466800702.146427722 512282.88485844800758.468338858
512287.165495699800853.433693644512295.211408872801242.548230419
512298.704563428801349.329145588512306.595321745801470.488256719
#Sta/Elev= 30
9642.604968.59579685.593965.49219755.693940.56279845.743937.21849905.756931.4168
 9925.76924.46289935.762918.23929965.769915.44719985.773904.81549995.775 904.029
10065.79910.7662 10095.8915.6289 10115.8920.8073 10125.8925.433110135.81936.8092
10155.81953.115810185.82968.244210215.83990.332810225.84995.552310235.84 1006.14
10245.851009.61610255.851009.81810265.861013.41610285.871027.04210305.911028.556
10345.99 1043.2210376.051060.10110386.081069.986 10396.11074.30110411.621073.891
#Mann= 3 , 0 , 0
9642.604   0.048       09642.604   0.048       010411.62   0.048       0
#XS Ineff= 2 , 0
       0                               0
Bank Sta=9642.604,10411.62
Exp/Cntr=0.3,0.1

Type RM Length L Ch R = 1 ,45826.58,247.787900,247.787900,247.787900
XS GIS Cut Line= 6
512064.915714577800714.253090154512061.353330703800800.913933722
512043.986029546801048.155899173512032.352007012801218.145450024
512025.342275626801346.770818167512024.172055981 801411.23862054
#Sta/Elev= 30
9664.415951.63439715.205952.4972 9745.23944.8777 9765.27944.55199775.294940.0892
9795.344935.45699905.615921.76389925.664914.27229965.762911.47979975.787904.5991
9985.812901.891910005.86901.825210015.88902.743210025.91 907.66210035.93906.9407
10045.95908.315510096.07920.917710126.14944.221810176.25972.619910186.27972.5051
10196.28976.7615 10206.3983.484110236.34995.772110246.361001.662 10276.41024.573
10286.421030.69410296.431031.14810306.431034.52210316.44 1035.8710362.681038.385
#Mann= 3 , 0 , 0
9664.415  0.0523       09664.415  0.0523       010362.68  0.0523       0
#XS Ineff= 2 , 0
       0                               0
Bank Sta=9664.415,10362.68
Exp/Cntr=0.3,0.1

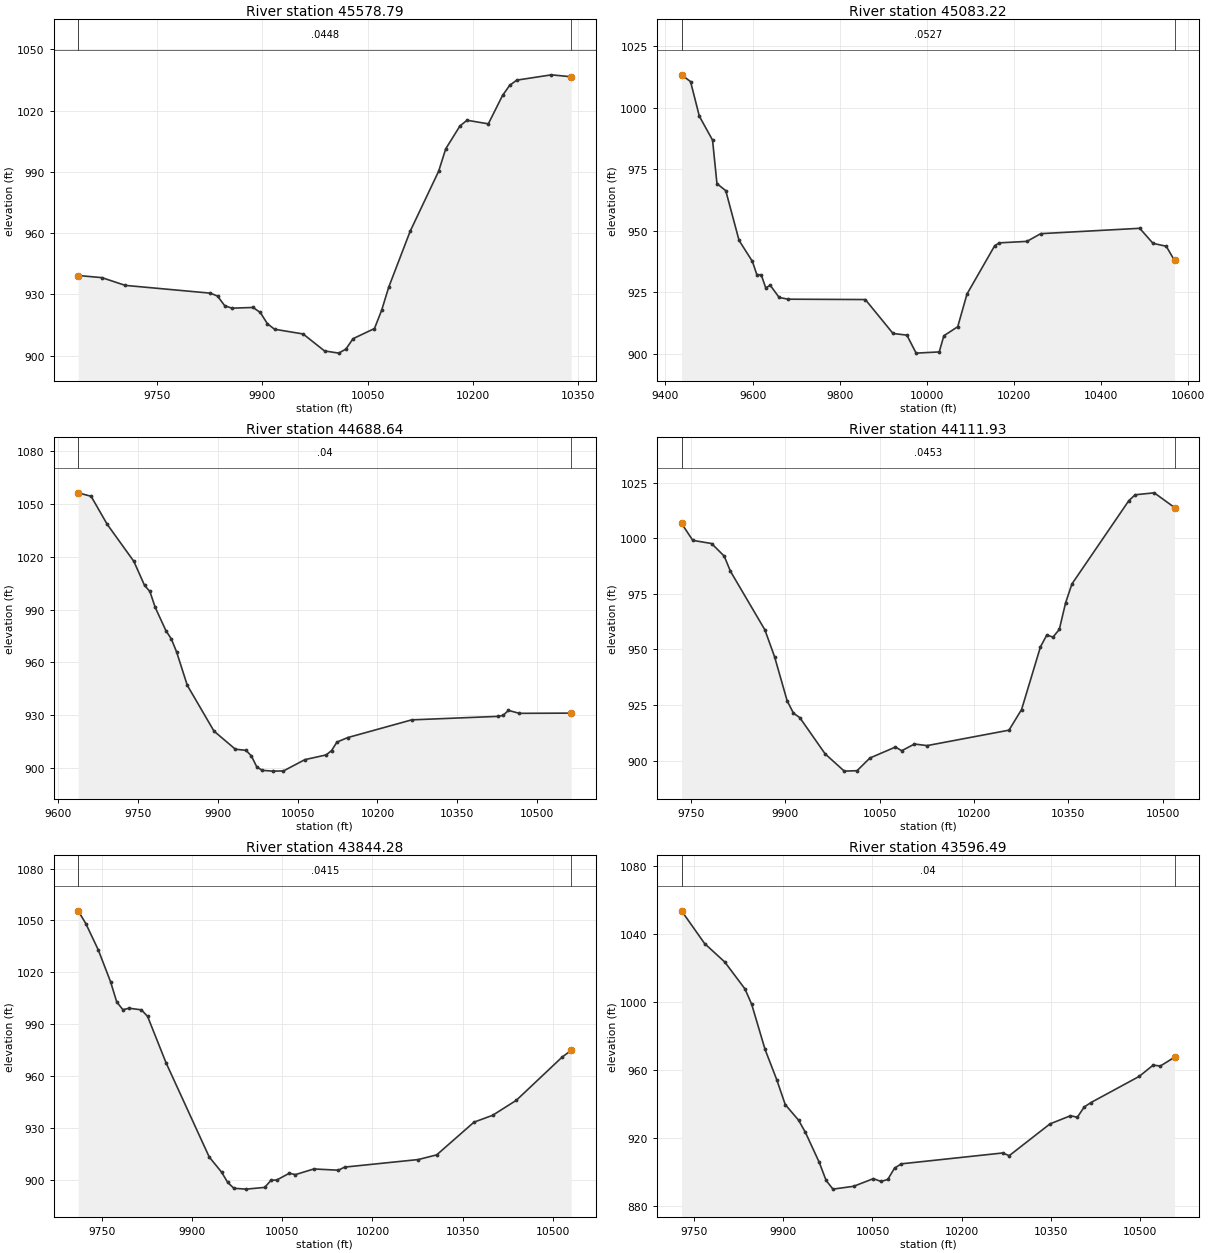
Type RM Length L Ch R = 1 ,45578.79,495.575700,495.575700,495.575700
XS GIS Cut Line= 6
511859.765894263800658.469627201 511843.69050269800771.450462952
511819.101395702800912.053811867511771.984019956801154.457796896
511746.369655186801312.213983062511741.756825158801351.990670021
#Sta/Elev= 30
 9637.03939.19679670.863 938.1529704.231934.35849825.815930.54169835.967929.0957
9846.118924.4171 9856.27923.19739886.726923.53589896.889921.07779907.081915.5817
9917.273912.87079958.042910.55179988.618902.2468   10009901.164410019.18903.1711
10029.36908.242610059.91913.2227 10070.1922.124110080.28933.500710110.83960.8564
10151.51990.299710161.641001.284 10181.91012.46610192.031015.26610222.42 1013.51
10242.691027.40310252.821032.34510262.951034.91910312.541037.52410340.691036.567
#Mann= 3 , 0 , 0
 9637.03  0.0448       0 9637.03  0.0448       010340.69  0.0448       0
#XS Ineff= 2 , 0
       0                               0
Bank Sta=9637.03,10340.69
Exp/Cntr=0.3,0.1

Type RM Length L Ch R = 1 ,45083.22,394.581600,394.581600,394.581600
XS GIS Cut Line= 6
511467.822574992800324.486258401511453.793914223800424.531905156
 511418.02526777   800588.873023511236.920955085801126.575547276
511202.892373569 801248.42856157511171.084211638801413.881372097
#Sta/Elev= 30
 9436.851013.2859457.5241010.5319477.731996.49649508.043986.79219518.147969.1375
9538.358966.28939568.904946.1019 9599.45937.61289609.633932.25259619.872932.1174
9630.154926.84119640.436927.91089661.001922.95549681.566922.26129858.816922.1149
9922.398908.34359954.192907.68269975.388900.378110028.46900.869610039.08907.4188
10070.96911.098610092.22924.366510155.98944.0048 10166.6945.121210229.84 945.716
10261.44948.842610488.77951.022610519.25944.912610549.63943.736610568.71937.9647
#Mann= 3 , 0 , 0
 9436.85  0.0527       0 9436.85  0.0527       010568.71  0.0527       0
#XS Ineff= 2 , 0
       0                               0
Bank Sta=9436.85,10568.71
Exp/Cntr=0.3,0.1

Type RM Length L Ch R = 1 ,44688.64,576.704800,576.704800,576.704800
XS GIS Cut Line= 4
510983.960837394800380.824323773510932.739085586801113.710874914
510910.721070392801231.779017492510901.572407863801301.259080647
#Sta/Elev= 30
9638.5331056.1689662.7681054.2019692.8411038.3689742.9631017.2979763.0121003.692
9773.0361000.2199783.061991.17869803.109978.01099813.134973.39779823.158965.9466
9843.207947.01079893.329 921.0359933.427910.78869953.475910.1452  9963.5906.9354
9973.524900.80899983.548898.8245 10003.6898.361810023.65898.476310063.74904.8661
10103.84907.564310113.87910.012810123.89914.819610143.94917.367210264.23927.4294
10425.38929.402610435.55929.958610445.73932.802910466.07931.133610563.39931.2532
#Mann= 3 , 0 , 0
9638.533    0.04       09638.533    0.04       010563.39    0.04       0
#XS Ineff= 2 , 0
       0                               0
Bank Sta=9638.533,10563.39
Exp/Cntr=0.3,0.1

Type RM Length L Ch R = 1 ,44111.93,267.652800,267.652800,267.652800
XS GIS Cut Line= 6
510402.935903796800447.182480893510398.761166168800638.699460825
510370.510972031 800809.15888072 510361.46707228800926.735403278
510363.065487532801051.743274414 510384.93310303801226.768617463
#Sta/Elev= 30
9734.7911006.6719752.626999.04389782.629997.60439802.632991.95339812.634 985.114
9867.296958.80829882.691946.74939902.746 926.8899912.774 921.3199922.801919.3436
9963.143903.03029993.575895.261710013.93895.4551 10034.3901.154810074.91906.0796
10085.02904.437410105.22907.454910125.32906.739810255.57913.684110275.57922.9673
10305.58951.119110315.59956.4381 10325.6955.5528 10335.6958.990610345.62970.9796
10355.65979.423810446.181016.90310456.281019.53510486.571020.41110518.861013.805
#Mann= 3 , 0 , 0
9734.791  0.0453       09734.791  0.0453       010518.86  0.0453       0
#XS Ineff= 2 , 0
       0                               0
Bank Sta=9734.791,10518.86
Exp/Cntr=0.3,0.1

Type RM Length L Ch R = 1 ,43844.28,247.787800,247.787800,247.787800
XS GIS Cut Line= 6
510057.454928761800442.612438172510129.020533427800746.239144639
510187.682879815801019.103549576510213.060920382801115.065237413
510238.459779844801194.944731911510255.357112577801238.790614507
#Sta/Elev= 30
9709.8411055.5529722.6691048.0839743.2321032.9929763.7751014.5059774.047  1002.8
9784.318998.3313 9794.59 999.1849815.133998.25269825.405 994.4639856.219967.5724
 9928.12913.07089948.663904.32979958.934898.34159969.206894.97129989.749894.4912
10020.53 895.49410030.76899.525810040.99899.844910061.44903.677210071.67902.8997
10102.36 906.16310143.27905.4399 10153.5907.229810276.24911.605310306.99914.3273
10369.06933.244610400.09937.211510439.56945.891110516.19 971.00510530.97  974.75
#Mann= 3 , 0 , 0
9709.841  0.0415       09709.841  0.0415       010530.97  0.0415       0
#XS Ineff= 2 , 0
       0                               0
Bank Sta=9709.841,10530.97
Exp/Cntr=0.3,0.1

Type RM Length L Ch R = 1 ,43596.49,247.787900,247.787900,247.787900
XS GIS Cut Line= 6
509760.731230309800560.627545515509854.222333004 800739.05545037
509910.277786325800834.871038716510047.089396224801089.852381719
510123.075157752 801222.76163621510162.257613328801285.340364131
#Sta/Elev= 30
9729.0711053.3689767.8761034.1329801.744 1023.289835.6131007.5069846.903998.5169
9869.482971.88839889.091954.14579903.351939.5238 9925.93930.26039937.372 923.099
9960.466905.60689972.064894.9488 9983.56889.809310018.39 891.47410051.51895.9663
10064.36894.334710075.71895.472810087.06902.126510098.41904.665510268.64 911.046
10279.99909.490210348.33928.123410382.89932.947710394.41932.066410405.93938.0693
10417.45940.720810498.42956.066210522.02962.725110533.82962.128710557.82967.3324
#Mann= 3 , 0 , 0
9729.071    0.04       09729.071    0.04       010557.82    0.04       0
#XS Ineff= 2 , 0
       0                               0
Bank Sta=9729.071,10557.82
Exp/Cntr=0.3,0.1

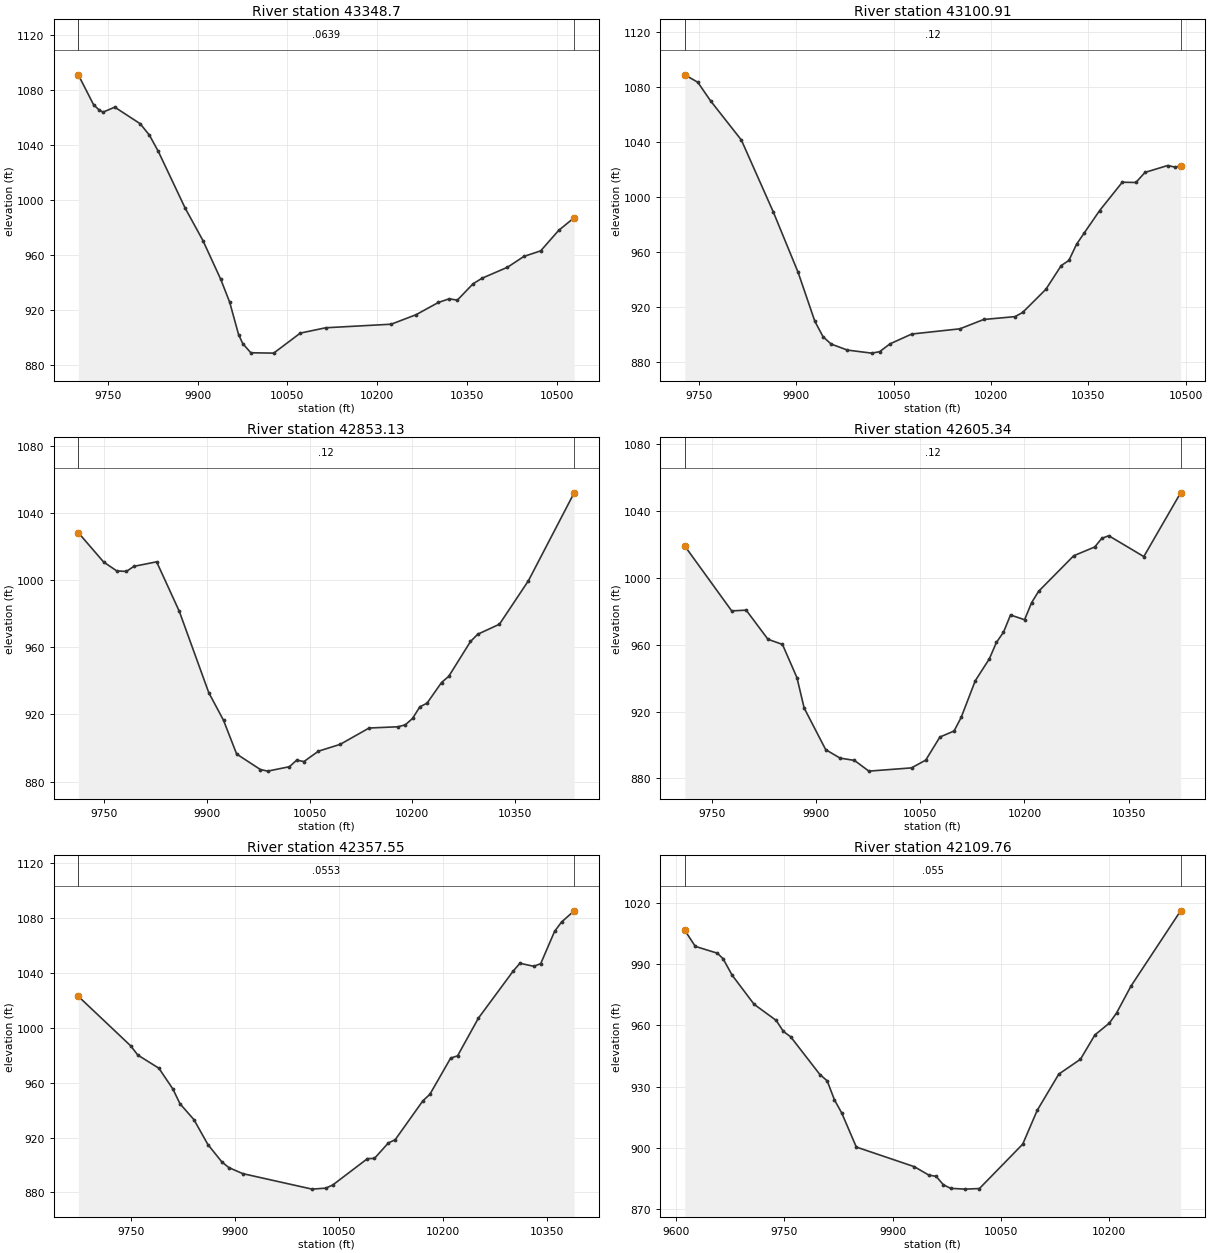
Type RM Length L Ch R = 1 , 43348.7,247.787800,247.787800,247.787800
XS GIS Cut Line= 6
509498.540225715800728.311828804509573.678729214 800817.87604996
509692.218588196800948.860594712509697.005335632800953.938661166
509972.531589298801242.772853136510063.229714008801334.854313782
#Sta/Elev= 30
9700.4541090.9389726.0631069.098 9735.291065.3429741.6221063.7839761.3961067.402
9803.8591055.3719819.3311047.0149834.2341035.1689878.943 994.0519908.749970.3772
9938.555942.14579953.458925.54949968.361901.97969975.328895.39099988.815888.7156
10027.07888.438810071.57903.0028   10114906.886510223.59 909.48510265.05916.3869
10302.34925.291210320.33927.946710334.15927.011410360.29938.854110375.61942.9823
10417.94950.915510445.41958.803310473.48962.862210503.44  977.7210529.42986.9747
#Mann= 3 , 0 , 0
9700.454  0.0639       09700.454  0.0639       010529.42  0.0639       0
#XS Ineff= 2 , 0
       0                               0
Bank Sta=9700.454,10529.42
Exp/Cntr=0.3,0.1

Type RM Length L Ch R = 1 ,43100.91,247.787900,247.787900,247.787900
XS GIS Cut Line= 6
509309.647504959800959.542573179509470.255572477801090.243514474
509659.537530255801229.093527677509724.708797241801272.969389056
509821.945698937801334.419883343509932.100666713801400.418837395
#Sta/Elev= 30
9728.4441088.864 9748.481083.4739768.0631070.0159815.5381041.5499864.582989.5102
9903.097945.31479928.774 909.9029941.442898.66199953.921893.34169978.881888.9822
10016.13886.759710028.51887.777910044.54893.486710078.02900.628810152.28904.4176
10188.91911.194310237.13913.261610248.84916.269510284.67933.113810308.33950.3253
10320.16954.100810331.99965.849910343.82974.053510367.43990.2447 10402.41010.871
10423.361010.68210437.371017.99210472.341023.004   104841021.81410492.281022.774
#Mann= 3 , 0 , 0
9728.444    0.12       09728.444    0.12       010492.28    0.12       0
#XS Ineff= 2 , 0
       0                               0
Bank Sta=9728.444,10492.28
Exp/Cntr=0.3,0.1

Type RM Length L Ch R = 1 ,42853.13,247.787800,247.787800,247.787800
XS GIS Cut Line= 6
509142.165493399801229.775263361509168.313449599801243.682366134
509273.001616025 801293.09122047509385.241371472801337.957583742
509406.620475648801345.870463453509818.139184852801488.381250953
#Sta/Elev= 30
 9711.951028.261 9748.961010.7859768.0831005.4999782.1341005.1759793.192 1008.21
9826.3651010.9119859.481981.42559902.558 932.9419924.097916.50199943.294896.3826
9977.944887.1518 9988.61886.192810020.45888.830310031.03892.723610041.62891.9038
10062.78898.078410094.53902.136210136.86911.878610179.19912.628410189.77913.7872
10200.36917.594210210.94924.486810221.52926.677710242.69938.999710253.27942.6972
10285.02963.4312 10295.6 967.75510327.35973.738910369.68999.6486 10436.51052.013
#Mann= 3 , 0 , 0
 9711.95    0.12       0 9711.95    0.12       0 10436.5    0.12       0
#XS Ineff= 2 , 0
       0                               0
Bank Sta=9711.95,10436.5
Exp/Cntr=0.3,0.1

Type RM Length L Ch R = 1 ,42605.34,247.787900,247.787900,247.787900
XS GIS Cut Line= 6
509061.051212996801503.535959671509219.156145975801553.315376577
509315.133103005801578.482438323 509409.52151387801599.352352428
509560.742325833801625.759071639509757.533486299 801652.16093638
#Sta/Elev= 30
9711.1191019.0469778.622980.23339799.498980.68319830.812963.25469851.689960.1715
9872.565940.27119882.944922.09269913.958897.18079934.635892.11999955.311890.7522
9976.125884.327410037.46 886.26710057.93 890.91510078.37904.737610098.73908.3475
10108.91916.431710129.27938.428810149.59951.597110159.72961.377210169.85 967.416
10179.98977.787410200.24974.945810210.37985.1788 10220.5991.992510270.97 1013.24
10301.241018.49110311.331023.62810321.421025.23110371.871012.74610424.871050.898
#Mann= 3 , 0 , 0
9711.119    0.12       09711.119    0.12       010424.87    0.12       0
#XS Ineff= 2 , 0
       0                               0
Bank Sta=9711.119,10424.87
Exp/Cntr=0.3,0.1

Type RM Length L Ch R = 1 ,42357.55,247.787800,247.787800,247.787800
XS GIS Cut Line= 6
508981.142411707801786.918592283509075.695616655801807.321085796
509142.958967283801817.810158618509209.739293465801824.800442358
509303.321259922801828.017528219 509693.24794252801825.884965408
#Sta/Elev= 30
9673.3691023.0539749.019986.90889759.217980.21899789.662 970.6099809.904955.4017
9820.025944.74219840.253933.06749860.362914.96729880.472902.29359890.526898.1511
9910.613893.736310010.68882.421810030.68883.163510040.68  885.4910090.68 904.689
10100.68904.808710120.68916.058210130.68918.488310170.68946.895710180.68951.5561
10210.68977.993710220.68979.646310250.681007.08510300.681041.30810310.681047.183
10330.681044.95310340.681046.91410360.681070.41210370.681077.24210388.941085.425
#Mann= 3 , 0 , 0
9673.369  0.0553       09673.369  0.0553       010388.94  0.0553       0
#XS Ineff= 2 , 0
       0                               0
Bank Sta=9673.369,10388.94
Exp/Cntr=0.3,0.1

Type RM Length L Ch R = 1 ,42109.76,247.787900,247.787900,247.787900
XS GIS Cut Line= 6
508920.765424573802024.189559293509052.599391587802049.579166969
509189.541415883802068.920954148 509278.61408838802075.554886154
509459.672959412802075.949304112509603.555560021802068.267951492
#Sta/Elev= 30
9611.9471006.7549626.487998.8595 9657.13995.50399664.999992.77989677.539984.7172
9708.017970.39519738.496962.51889748.641957.0623 9758.74954.41419799.137935.9169
9809.236932.82819819.336 923.4569829.435916.98559849.633900.28489930.102890.6227
9950.157886.48239960.185885.90579970.213881.78219980.223880.000610000.22879.6095
10020.22879.899710080.22901.704810100.22918.262710130.22936.118610160.23943.4159
10180.24955.363410200.25961.158410210.26966.145710230.27979.376910299.031016.322
#Mann= 3 , 0 , 0
9611.947   0.055       09611.947   0.055       010299.03   0.055       0
#XS Ineff= 2 , 0
       0                               0
Bank Sta=9611.947,10299.03
Exp/Cntr=0.3,0.1

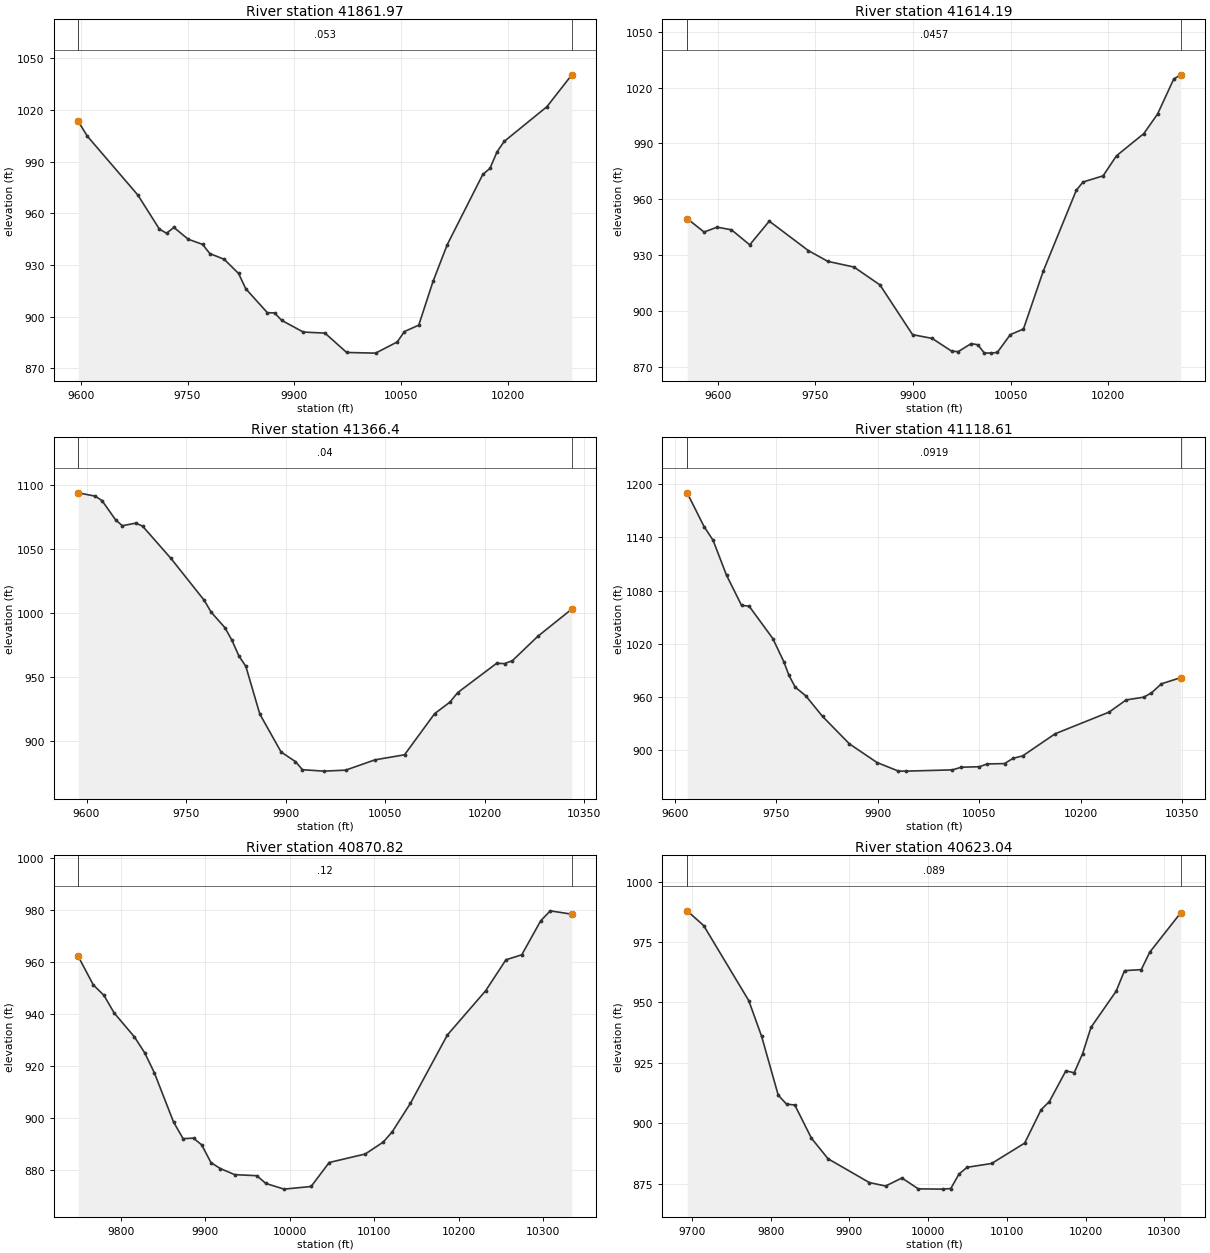
Type RM Length L Ch R = 1 ,41861.97,247.787800,247.787800,247.787800
XS GIS Cut Line= 6
508862.419467145802253.478935816509196.737761244802306.428582244
 509297.92555869802325.745819454509339.790322402802330.428875932
509465.548977159802332.406641487509549.669866422 802324.05029107
#Sta/Elev= 30
9596.2991013.4259609.1131004.7819680.158970.62499710.506950.79869720.622948.4419
9730.738951.8604 9750.97944.97489771.202941.98649781.318936.6726 9801.55933.3321
9821.782 925.1159831.898 916.2439862.246902.35119872.362   902.29882.478897.8671
9912.826891.09859943.228890.50839973.772879.2583 10014.5878.876110044.95885.3896
10055.01891.403710075.14895.117310095.19920.467710115.22941.849710165.25982.6288
10175.25 986.06510185.25995.725310195.251001.72810255.421021.92110290.361040.389
#Mann= 3 , 0 , 0
9596.299   0.053       09596.299   0.053       010290.36   0.053       0
#XS Ineff= 2 , 0
       0                               0
Bank Sta=9596.299,10290.36
Exp/Cntr=0.3,0.1

Type RM Length L Ch R = 1 ,41614.19,247.787800,247.787800,247.787800
XS GIS Cut Line= 6
 508819.05948906802567.139154086509021.403728853802573.951719773
509331.682325149802560.636283011509405.415483239802549.193707886
 509488.27115293 802528.55334729509568.557484021802500.907074203
#Sta/Elev= 30
9553.118949.72229579.114 942.4929599.157945.12249621.199  943.699649.219935.6338
9679.236948.34379739.238932.55139769.242926.75649809.252923.73199849.266914.1207
9899.307887.46049929.332885.43619959.357878.59399969.365878.32479989.382882.6619
 9999.39882.042210009.41877.683110019.44877.538410029.47877.924710049.53887.4864
10069.62890.468610099.98921.468110150.75964.859110161.06969.319410191.97 972.653
10212.59983.438310254.45995.294810275.54 1005.7610300.491024.605 10311.21026.832
#Mann= 3 , 0 , 0
9553.118  0.0457       09553.118  0.0457       0 10311.2  0.0457       0
#XS Ineff= 2 , 0
       0                               0
Bank Sta=9553.118,10311.2
Exp/Cntr=0.3,0.1

Type RM Length L Ch R = 1 , 41366.4,247.787900,247.787900,247.787900
XS GIS Cut Line= 6
508929.385682801802919.248623914509066.809250467802894.092825864
509162.223545805802866.501062488509273.840278084802824.827806971
 509428.07818623802751.443927939509608.961678552802635.972079203
#Sta/Elev= 30
9587.4421093.974  9613.3 1091.359623.3951087.8289643.6311072.927 9653.851068.234
9674.2871070.2659684.5061067.8849727.2291042.6299777.3941009.8359787.8041000.572
9808.623988.40519819.033978.66469829.497966.45189840.101958.14249861.118920.8495
9893.182891.18349914.695883.71079925.451877.30289957.853876.20469990.479876.9693
10034.51885.011310079.24889.006410124.61921.200210147.69930.210410159.23937.5965
10218.09960.592410229.92 960.33110241.75962.6237 10280.1981.698510331.321003.017
#Mann= 3 , 0 , 0
9587.442    0.04       09587.442    0.04       010331.32    0.04       0
#XS Ineff= 2 , 0
       0                               0
Bank Sta=9587.442,10331.32
Exp/Cntr=0.3,0.1

Type RM Length L Ch R = 1 ,41118.61,247.787800,247.787800,247.787800
XS GIS Cut Line= 6
509161.673361349803229.495865828509244.068292784803192.230291061
509287.170416953803166.117980693 509386.45657423803086.143371244
509460.256893604  803007.0138776509682.781361037802733.103240357
#Sta/Elev= 30
9618.134 1190.319643.1521152.2099656.4231136.8319676.3281097.3599698.553  1063.3
 9709.72 1062.449744.7951025.865 9760.92 999.9059768.722984.19839777.869971.0331
9793.493 961.2169818.263938.03349858.114906.95649898.798885.97019930.408876.3159
9941.572 876.25410010.39877.6705 10023.2880.656610050.26881.237110061.66884.3703
 10087.3884.750610100.12890.7714 10114.2 893.46310162.15918.407710242.07942.9052
10267.07956.579610293.16959.714510304.54964.542410319.25974.783110347.81981.7554
#Mann= 3 , 0 , 0
9618.134  0.0919       09618.134  0.0919       010347.81  0.0919       0
#XS Ineff= 2 , 0
       0                               0
Bank Sta=9618.134,10347.81
Exp/Cntr=0.3,0.1

Type RM Length L Ch R = 1 ,40870.82,247.787900,247.787900,247.787900
XS GIS Cut Line= 6
509562.039751756803338.503708529509609.014675397803273.585649822
509629.104461877803236.596105889509728.234972617802986.566669457
509771.896451695  802887.8641173509811.310821109802812.751061885
#Sta/Elev= 30
9749.463962.21489767.363951.23769779.974947.22559791.989940.49079816.019931.2754
9828.034925.24089839.504917.56569862.263898.62549873.584892.22299885.909892.3939
9895.607889.82299906.619882.9901 9917.63880.74059934.631878.39289960.831 877.982
9971.573875.01229993.056872.824310025.12873.840510046.48883.045710089.19 886.314
10110.54890.899510121.22894.891810142.61905.760910186.35932.010810231.78949.0468
10255.71960.905410274.45962.819910296.86975.894110308.22979.707310333.67978.4116
#Mann= 3 , 0 , 0
9749.463    0.12       09749.463    0.12       010333.67    0.12       0
#XS Ineff= 2 , 0
       0                               0
Bank Sta=9749.463,10333.67
Exp/Cntr=0.3,0.1

Type RM Length L Ch R = 1 ,40623.04,247.787800,247.787800,247.787800
XS GIS Cut Line= 6
509820.766392916803494.973629311509888.986571223803287.627300218
509926.971075892803144.489991397509961.625932813803032.224549592
509995.173727363802940.678660572510012.732370436802898.699670881
#Sta/Elev= 30
9693.864987.89999714.871981.79949772.105950.77179788.491935.95649809.525911.6857
9820.058907.98189830.597907.60049851.677 893.9039872.756885.38379925.222875.5357
9945.934874.09649966.645877.43249987.357872.936110018.37872.8165 10028.7873.0646
10039.04879.019210049.38  881.8410080.64883.4277 10122.5 891.84710143.43905.6653
 10153.9 909.02610174.83921.727210185.43920.941710196.08928.823110206.73939.6955
10238.68954.650510249.33963.171510270.63963.587210281.39970.791210320.74987.0902
#Mann= 3 , 0 , 0
9693.864   0.089       09693.864   0.089       010320.74   0.089       0
#XS Ineff= 2 , 0
       0                               0
Bank Sta=9693.864,10320.74
Exp/Cntr=0.3,0.1