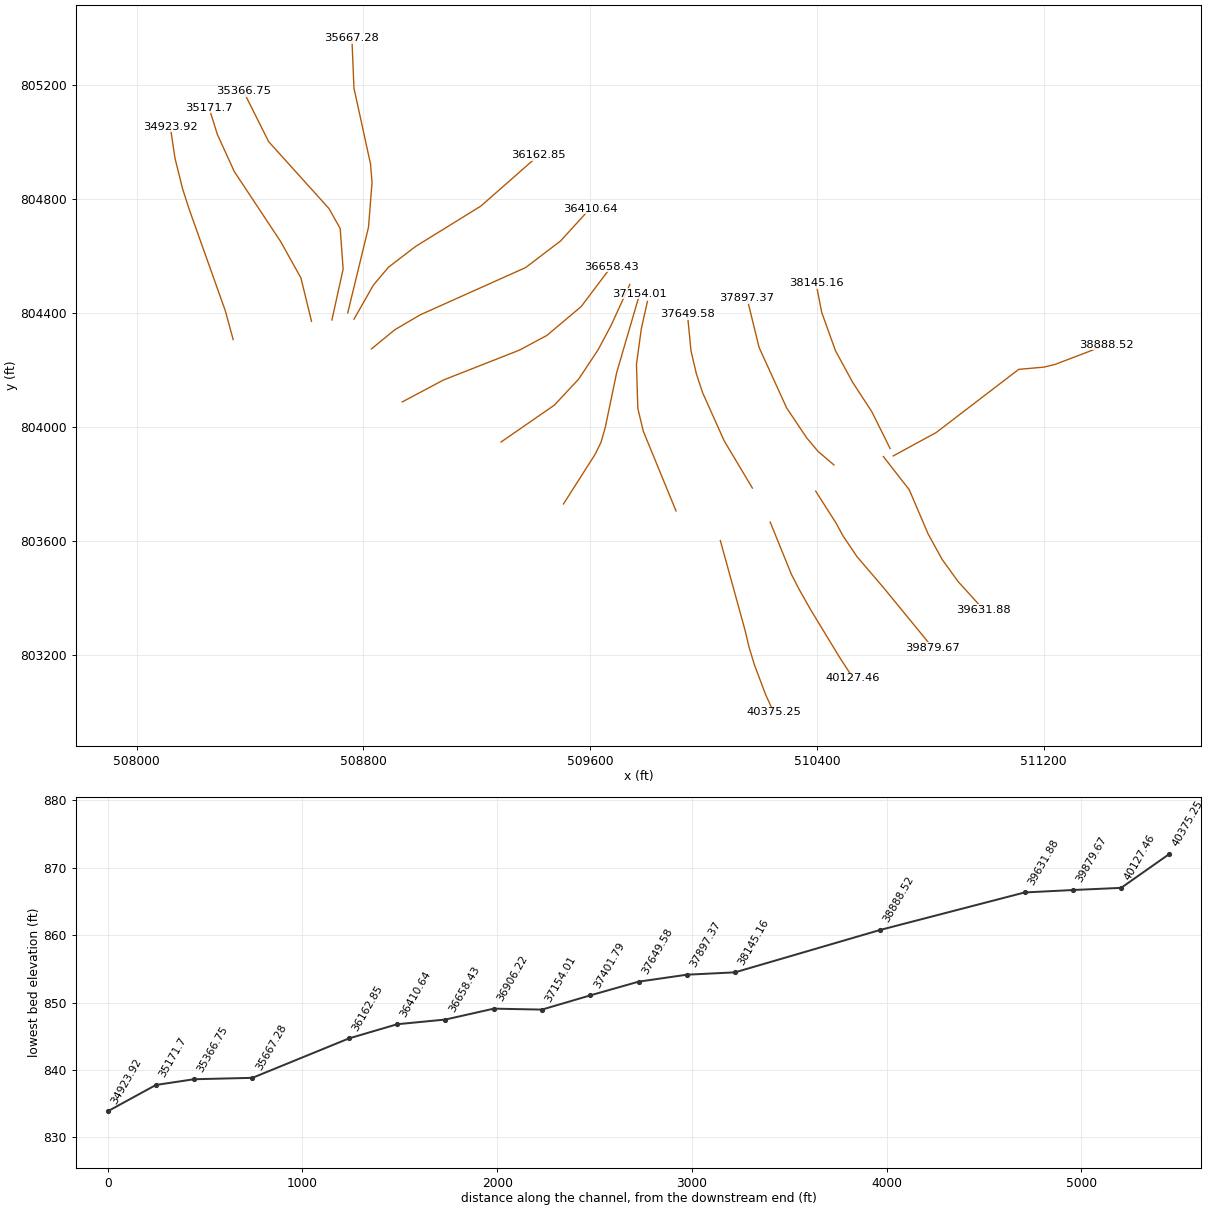
HEC-RAS study 5238_ras.prj: 5238

--- 5238_ras.g01 (geometry) --- (continued)

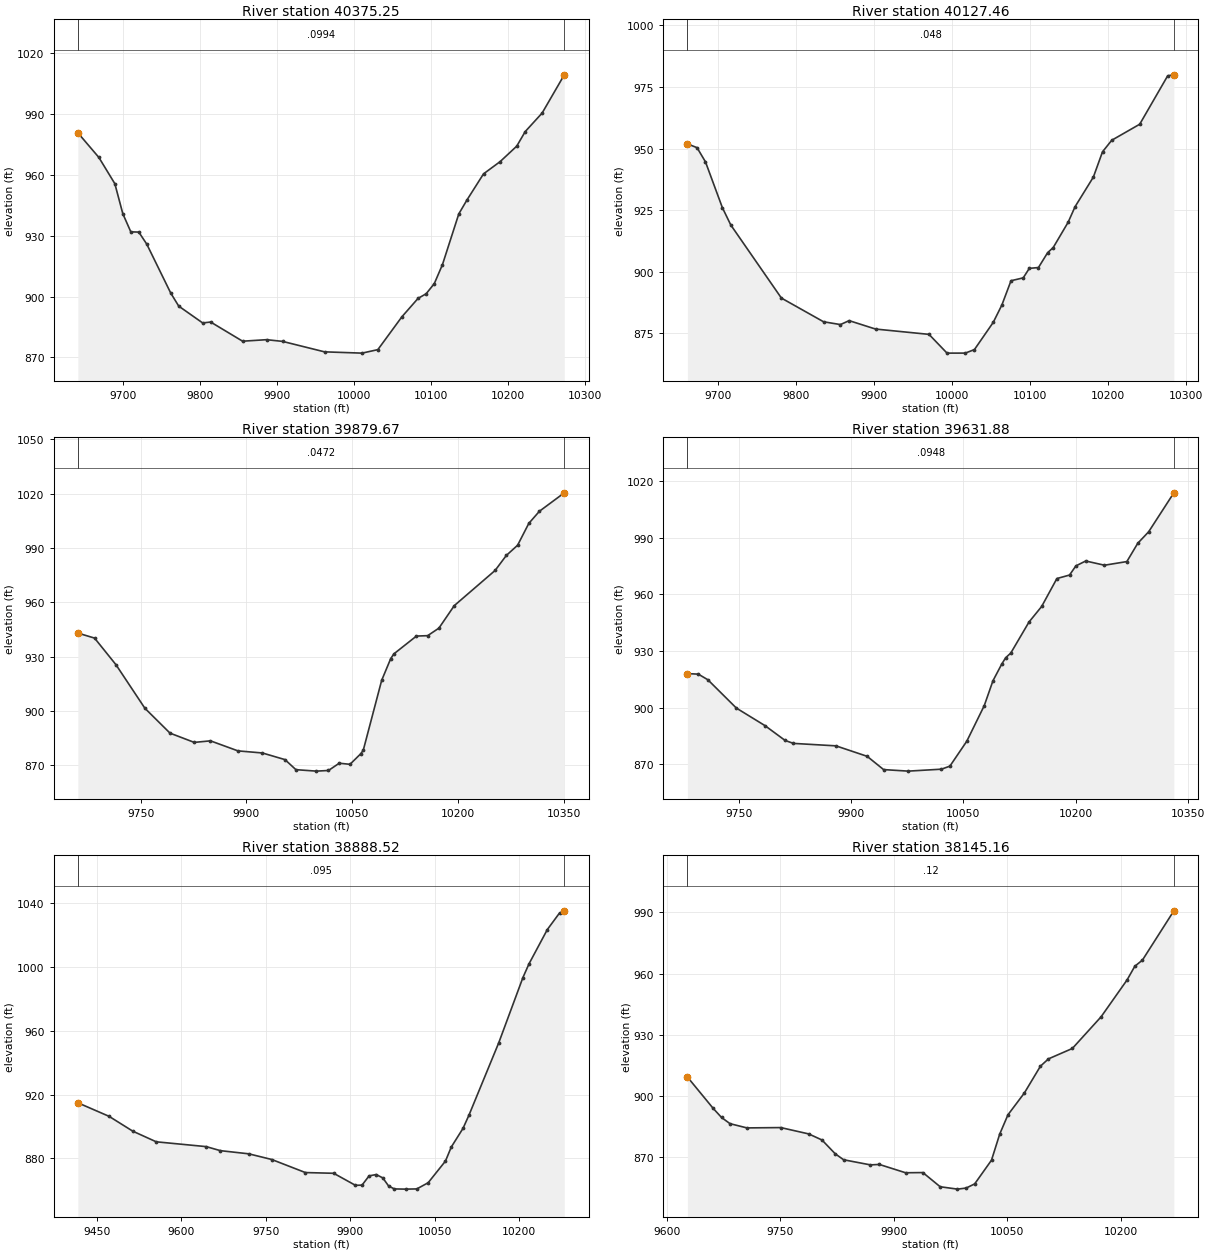
Type RM Length L Ch R = 1 ,40375.25,247.787900,247.787900,247.787900
XS GIS Cut Line= 6
510059.481670707803601.310434878510146.817188829803285.701686591
510161.384640455803224.561828837510179.464968771803165.723478869
510219.225895047 803060.28708604 510247.39265427 802998.83158353
#Sta/Elev= 30
9641.084980.7976 9668.39 968.6479689.147955.68789699.525940.85469709.903931.9172
9720.282931.8051 9730.66925.83829761.795901.70239772.174895.26519803.309886.9569
9813.687 887.4129855.201877.94579886.336878.69529907.088877.85659961.651872.6943
10010.37872.060710030.96873.780710062.33890.047310083.26 899.09510093.73901.3664
10104.34906.376610114.95 915.76810136.17940.781510146.81947.672710168.32960.5458
10189.84 966.57210211.48974.220310222.48981.404210244.48990.559310273.271009.422
#Mann= 3 , 0 , 0
9641.084  0.0994       09641.084  0.0994       010273.27  0.0994       0
#XS Ineff= 2 , 0
       0                               0
Bank Sta=9641.084,10273.27
Exp/Cntr=0.3,0.1

Type RM Length L Ch R = 1 ,40127.46,247.787800,247.787800,247.787800
XS GIS Cut Line= 6
510235.262920707803666.414601535510310.071365625803482.977886528
 510338.07587108803428.864482403510378.105261326803358.481711969
510480.898062944803190.087327227510527.842811555803118.502497539
#Sta/Elev= 30
9660.993951.9392 9673.32950.3988 9684.12944.62929705.719926.07439716.519919.0257
9781.316889.37329835.314 879.7529856.913878.6192 9868.08880.21469901.859876.8021
9970.344 874.6439993.441867.0301 10016.8867.043310028.51868.463610052.62879.5222
10063.66886.554710075.37896.4069   10091897.572310098.81901.427210110.52901.7606
10122.24907.783710129.39909.859810148.58920.174710157.39926.445710180.82938.4633
10192.53948.719210204.36 953.41110240.18 959.913   10276979.5671 10283.9979.9602
#Mann= 3 , 0 , 0
9660.993   0.048       09660.993   0.048       0 10283.9   0.048       0
#XS Ineff= 2 , 0
       0                               0
Bank Sta=9660.993,10283.9
Exp/Cntr=0.3,0.1

Type RM Length L Ch R = 1 ,39879.67,247.787900,247.787900,247.787900
XS GIS Cut Line= 6
510395.853198469803774.921545982510467.571593046803662.902749211
510492.042274624803618.235028878510541.602874398803544.818952724
510635.513395786  803435.6320979510808.435078979803225.397645116
#Sta/Elev= 30
9661.191942.94349684.846940.16949715.247925.42339756.089901.43469791.711887.6866
9826.017 882.5749848.967 883.431 9887.89  877.899922.495876.7356  9954.5873.0632
9969.987867.50929998.992866.709210016.11867.067910031.33871.076610046.55870.4687
10061.77876.289210065.35878.229810091.44 916.85610104.29928.8807 10108.8931.4824
10140.64941.286710156.56941.513410172.48945.663310194.25958.094810252.08977.5261
   10268985.825410283.92991.441110299.791003.50610314.821010.21110350.041020.387
#Mann= 3 , 0 , 0
9661.191  0.0472       09661.191  0.0472       010350.04  0.0472       0
#XS Ineff= 2 , 0
       0                               0
Bank Sta=9661.191,10350.04
Exp/Cntr=0.3,0.1

Type RM Length L Ch R = 1 ,39631.88,743.363500,743.363500,743.363500
XS GIS Cut Line= 6
 510634.56847626803896.449323773510725.904204041803779.836175755
510792.637528777803624.286814451510841.934005529803535.096148416
510898.785269827803456.731143788 510988.50043273803358.582078382
#Sta/Elev= 30
9681.595918.02999696.139917.74579708.841914.77649746.947 899.7559785.054890.4765
9812.036882.58959823.161 881.0429879.843879.74269921.495874.19239943.416867.1601
9976.297866.347210020.66867.379410031.92868.997410054.45882.183710077.76901.0337
10089.42914.253410101.08923.048210106.37926.438710113.22928.938910137.51945.3656
 10154.4953.607110174.73968.407810191.62970.262610200.08975.110910213.22977.7124
10238.25975.470710268.13977.403910282.67987.091910297.21993.188210330.851013.836
#Mann= 3 , 0 , 0
9681.595  0.0948       09681.595  0.0948       010330.85  0.0948       0
#XS Ineff= 2 , 0
       0                               0
Bank Sta=9681.595,10330.85
Exp/Cntr=0.3,0.1

Type RM Length L Ch R = 1 ,38888.52,743.363500,743.363500,743.363500
XS GIS Cut Line= 6
510669.290698469803898.619462669510821.200420707 803981.08474043
 511111.86557957804202.588179725511201.319215485804210.622003081
511240.727110346804220.160065191511422.654578894804289.341397841
#Sta/Elev= 30
9416.167914.93929471.462906.46429513.691 897.1339555.303890.46179644.085887.4381
 9669.23884.90999719.521882.92859760.461879.36119820.103871.17049870.394870.7112
9908.946863.17599920.685863.27369933.257869.0812 9945.83869.92679957.644 867.808
9967.797862.77839977.949 860.9059997.955860.772710017.97860.900510038.14864.7847
10068.87878.387310079.16887.177210100.04898.911310110.55907.168510163.48952.6106
10206.39993.535710217.221002.15310249.691023.61510271.431034.04510279.821035.378
#Mann= 3 , 0 , 0
9416.167   0.095       09416.167   0.095       010279.82   0.095       0
#XS Ineff= 2 , 0
       0                               0
Bank Sta=9416.167,10279.82
Exp/Cntr=0.3,0.1

Type RM Length L Ch R = 1 ,38145.16,247.787900,247.787900,247.787900
XS GIS Cut Line= 6
510658.440004021803924.661129296510593.088977128804055.348830119
510527.005937189804155.712455168510465.695760787 804267.94678013
510417.090734065804402.748243868510396.841493845804505.953470185
#Sta/Elev= 30
9627.582909.34869661.502894.05999672.683889.55679683.864886.52889706.225884.4565
9750.947884.61599787.877881.51679805.405878.55039822.932871.7869 9834.02868.8671
9869.441866.36189881.248866.57529915.935862.50689938.788862.60079961.641855.6621
9984.494854.4982 9995.92855.016910007.24857.064110029.47868.662610040.35881.4597
10051.23890.873810072.93901.559110094.17914.673610104.79918.244410136.32 923.331
10174.29938.815510208.69956.884910218.86963.546910228.99966.587110270.49990.6858
#Mann= 3 , 0 , 0
9627.582    0.12       09627.582    0.12       010270.49    0.12       0
#XS Ineff= 2 , 0
       0                               0
Bank Sta=9627.582,10270.49
Exp/Cntr=0.3,0.1

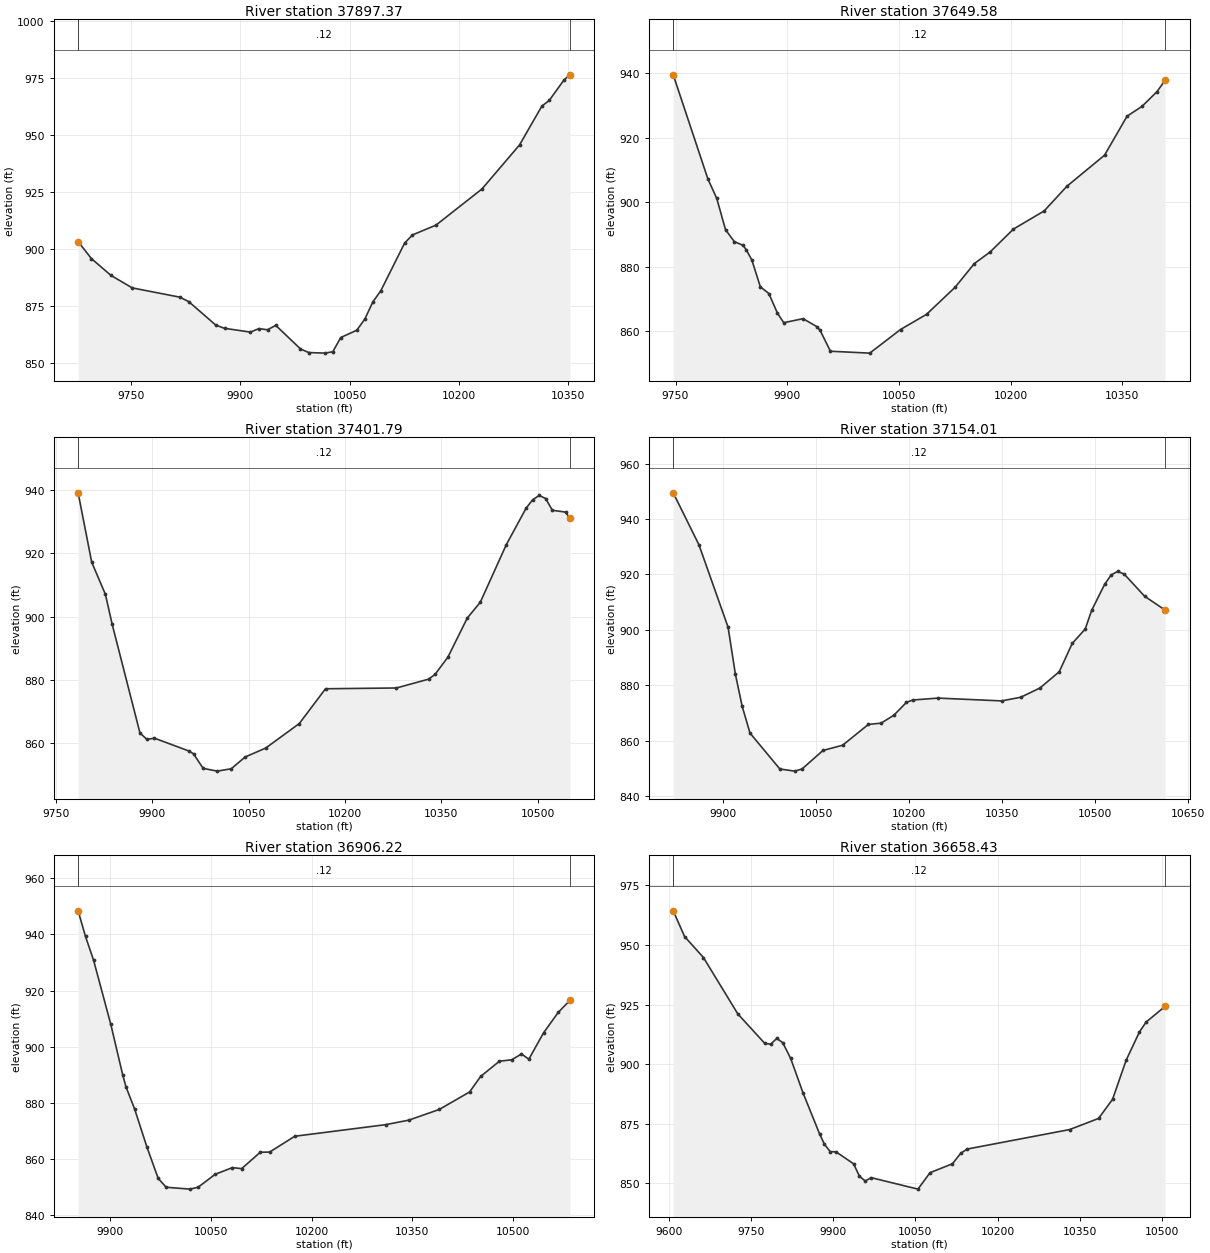
Type RM Length L Ch R = 1 ,37897.37,247.787800,247.787800,247.787800
XS GIS Cut Line= 6
510460.205959772803866.945186696510404.037186009803914.705077323
510364.299699934803961.800921959510293.498232545804066.975351735
510196.117433898804279.737753336510153.446037295804453.016034165
#Sta/Elev= 30
9677.246903.08789695.477895.63359722.457888.23159751.587 882.7689816.777878.7144
9829.141876.76149866.234866.46289878.295865.03159913.726863.37979925.536864.8959
9937.346864.40219948.729866.32359982.565856.01129993.844854.407910015.98854.1457
10026.98854.739710037.98861.000310059.98864.202610070.98869.069910081.98876.5866
10092.99881.5374 10125.7 902.45310136.46906.017910168.73910.317310231.85926.1643
10283.46945.4898 10314.2962.554910324.31965.041610344.53973.998910352.64976.2692
#Mann= 3 , 0 , 0
9677.246    0.12       09677.246    0.12       010352.64    0.12       0
#XS Ineff= 2 , 0
       0                               0
Bank Sta=9677.246,10352.64
Exp/Cntr=0.3,0.1

Type RM Length L Ch R = 1 ,37649.58,247.787900,247.787900,247.787900
XS GIS Cut Line= 6
510172.437293365803785.849981101 510073.35425952803951.039907629
 509996.95384644804120.513117251509974.669461919804187.905036068
509955.920610419804267.907854975509943.395673167804395.842562271
#Sta/Elev= 30
 9746.95939.51169793.525907.17829805.366901.16049817.207891.42789829.047887.7146
9840.888  886.579845.113885.14059852.487882.06299863.952873.70339875.418871.6033
9886.883865.54169895.415862.55739921.278863.80639939.668861.3738 9944.11860.2413
9958.106853.698810010.94853.110810052.23860.441110087.23865.159610125.66873.5794
10151.45880.927110172.51884.492110203.98891.626710245.21897.254610275.86904.9385
10326.33914.564810356.58926.671910376.62929.716810396.64934.260510407.49937.7567
#Mann= 3 , 0 , 0
 9746.95    0.12       0 9746.95    0.12       010407.49    0.12       0
#XS Ineff= 2 , 0
       0                               0
Bank Sta=9746.95,10407.49
Exp/Cntr=0.3,0.1

Type RM Length L Ch R = 1 ,37401.79,247.787800,247.787800,247.787800
XS GIS Cut Line= 6
509903.229189688 803705.13921195509787.668030183803985.351039805
509768.368468169804065.383637251509763.557509537 804220.49604713
509780.651595107804345.281256587509802.226919718804441.552139844
#Sta/Elev= 30
 9784.62939.15759805.771 917.1949827.069907.04079837.719 897.4879880.905863.1622
9891.732861.11299903.442861.51469957.415857.42599964.312856.55239979.362851.9473
 10001.3851.079310023.13851.835510044.65855.550610076.77858.385310129.08866.1451
10169.86877.147510280.22877.393410330.26880.179610340.32881.676810360.44887.1509
10390.65899.539310410.91904.526810451.45922.760310482.12934.248310492.35936.9479
10502.58938.3155 10512.8937.347810523.03933.641910543.65933.057410550.41931.1534
#Mann= 3 , 0 , 0
 9784.62    0.12       0 9784.62    0.12       010550.41    0.12       0
#XS Ineff= 2 , 0
       0                               0
Bank Sta=9784.62,10550.41
Exp/Cntr=0.3,0.1

Type RM Length L Ch R = 1 ,37154.01,247.787800,247.787800,247.787800
XS GIS Cut Line= 6
509506.080358561803730.004439649509617.705658261803904.316658232
509638.261353059803946.092954263509653.596698453803999.278276906
509693.622583776804190.964656776509774.831158618804467.767049177
#Sta/Elev= 30
9819.142949.46729860.566930.73269907.634 900.9459919.401 884.0019930.326872.4233
9942.975862.72139991.172849.742310015.08 848.97210026.94849.7502 10060.7856.4275
10092.45858.328910133.97865.840910154.41866.288710174.84869.104610195.27873.7653
10205.48874.650110246.35875.343610348.82874.333310379.86875.6562 10410.9879.0063
10441.94884.871110462.85895.077910483.81900.280810494.29907.066910515.26916.4673
10525.74919.825510536.22921.1013 10546.7920.111610579.68912.116510612.49907.1528
#Mann= 3 , 0 , 0
9819.142    0.12       09819.142    0.12       010612.49    0.12       0
#XS Ineff= 2 , 0
       0                               0
Bank Sta=9819.142,10612.49
Exp/Cntr=0.3,0.1

Type RM Length L Ch R = 1 ,36906.22,247.787900,247.787900,247.787900
XS GIS Cut Line= 6
509285.907647438803947.642484466509473.777158901804076.912794456
509559.708607847 804168.61643704509628.246903623804271.493729447
509673.466696906 804355.92394126509740.205118885804500.900587203
#Sta/Elev= 30
9851.762948.44069862.754939.29529874.844930.76829900.444 907.9419918.239889.8582
9923.202885.55589936.033877.66329954.156864.25489971.108852.95359982.984849.7794
10018.68849.109410030.74849.806310056.12854.401810081.65 856.78310095.55856.4312
10123.36862.283710137.27862.336610174.72867.981510310.09872.113110344.77873.7364
10390.15877.5499 10435.3  883.7810451.86889.337110479.68894.743210498.15895.2773
10512.73897.355410523.67895.484810545.56904.880310567.45 912.17610584.85 916.475
#Mann= 3 , 0 , 0
9851.762    0.12       09851.762    0.12       010584.85    0.12       0
#XS Ineff= 2 , 0
       0                               0
Bank Sta=9851.762,10584.85
Exp/Cntr=0.3,0.1

Type RM Length L Ch R = 1 ,36658.43,247.787800,247.787800,247.787800
XS GIS Cut Line= 6
508937.432646125804088.354253101509083.363049529804165.623413072
509350.221210405804270.003482713509447.172060065804321.632025806
509568.534326411804423.236347962509674.699586205804563.582605554
#Sta/Elev= 30
9608.439964.32569629.139953.52899663.547944.71899726.296 921.0339775.471908.6508
9786.364908.37199797.257910.7772 9808.15908.96999822.553902.40359845.109887.9019
9875.255870.72479883.882866.43829894.631863.22869905.379863.13979937.417858.1214
9948.038852.86589958.659850.9216 9969.28 852.322 10054.7847.497210076.75854.4082
10117.57858.141110132.97 862.61110144.56864.327810331.24872.499210384.03877.1723
10409.56885.207110434.42901.666610458.63913.507310470.74917.622610505.14924.1818
#Mann= 3 , 0 , 0
9608.439    0.12       09608.439    0.12       010505.14    0.12       0
#XS Ineff= 2 , 0
       0                               0
Bank Sta=9608.439,10505.14
Exp/Cntr=0.3,0.1

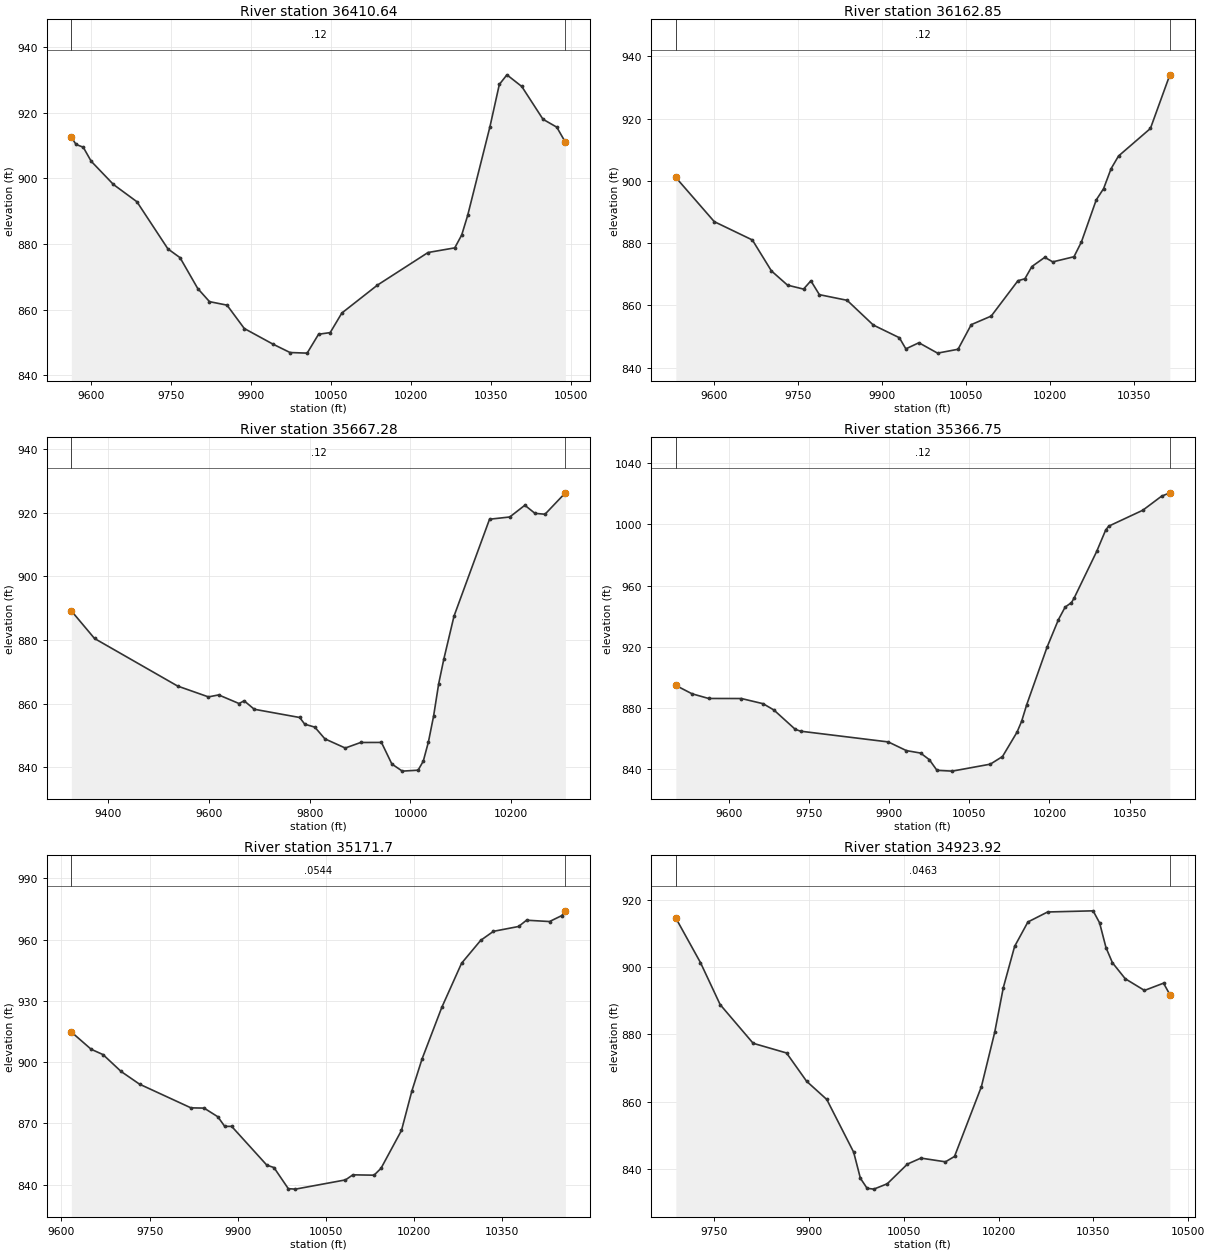
Type RM Length L Ch R = 1 ,36410.64,247.787900,247.787900,247.787900
XS GIS Cut Line= 6
508828.541701214804274.458777147508910.928082288804341.741872139
509001.166879573804394.440127361509372.551630505804560.190322286
509496.016029947804653.765830435509599.997670934804767.484275375
#Sta/Elev= 30
9562.672912.55539571.428910.36839584.985909.51099599.881905.24419641.632898.1674
9685.729892.91319744.001878.53649766.693875.88399799.977866.47989822.036862.4799
9854.927861.41499887.364854.29999941.196849.53989973.286846.982410005.39846.7995
10026.85852.553810048.67853.052210070.57859.016610137.46867.527210232.38877.4436
10282.54878.859510295.58882.772810306.76888.718410348.63915.763810366.25928.6354
10380.49931.561610408.41928.007310448.24918.029210474.12915.622410490.27911.0352
#Mann= 3 , 0 , 0
9562.672    0.12       09562.672    0.12       010490.27    0.12       0
#XS Ineff= 2 , 0
       0                               0
Bank Sta=9562.672,10490.27
Exp/Cntr=0.3,0.1

Type RM Length L Ch R = 1 ,36162.85,495.575700,495.575700,495.575700
XS GIS Cut Line= 6
508767.247997862804379.215288344 508835.62652178804498.896583255
508888.690712818 804561.32905831508984.422933865804634.423168591
509214.743547046804776.204371467509418.833146865804954.837400644
#Sta/Elev= 30
9531.232901.1082 9599.93886.92179668.005881.03679702.099 871.0939730.851866.5286
9759.476865.26319772.591867.92059787.787863.4708 9837.33861.6619 9884.13853.7173
9930.702849.64559942.345846.06489965.631848.0294    9999844.695810035.61 845.934
10059.17853.837310094.93856.601610142.64867.943810155.09868.577310167.55872.5066
10190.61875.459610204.92874.003810242.84 875.65610256.09 880.39510282.59893.9038
10295.83897.556510309.08903.920110322.43908.005910379.41916.842210414.18934.0787
#Mann= 3 , 0 , 0
9531.232    0.12       09531.232    0.12       010414.18    0.12       0
#XS Ineff= 2 , 0
       0                               0
Bank Sta=9531.232,10414.18
Exp/Cntr=0.3,0.1

Type RM Length L Ch R = 1 ,35667.28,300.528000,300.528000,300.528000
XS GIS Cut Line= 6
508745.016870368 804401.29619645508818.219646757 804701.79296797
508830.685999586804859.173051445508825.382592571804923.840325102
508766.904766843 805190.50399335508759.622082122 805365.43940789
#Sta/Elev= 30
 9326.51889.18829372.521880.52169537.658865.56829598.712862.17369619.063862.7915
9659.545 860.0869669.626860.94159689.786858.28419780.008855.69799790.009853.5956
 9810.03852.67289830.058848.98679870.471846.1057 9901.12 847.8479942.409847.8616
9963.053841.08169983.773838.847410015.13839.142210025.43 841.97810035.66  848.02
10045.89856.095910056.12866.373310066.26874.047710086.48887.541310157.05917.9933
10197.19918.696210227.22922.385510247.23 919.84110267.24919.560610307.68926.2869
#Mann= 3 , 0 , 0
 9326.51    0.12       0 9326.51    0.12       010307.68    0.12       0
#XS Ineff= 2 , 0
       0                               0
Bank Sta=9326.51,10307.68
Exp/Cntr=0.3,0.1

Type RM Length L Ch R = 1 ,35366.75,195.047700,195.047700,195.047700
XS GIS Cut Line= 6
508689.127422071804376.035451771508728.719251056804554.891713278
508718.452375515804697.030414281508678.849159247804767.397189554
508465.965799068805002.405503531508376.803626303805179.713460524
#Sta/Elev= 30
9500.683894.6805 9531.01889.21649562.001886.1616 9623.38886.12129664.051882.7282
9684.235878.60969724.297865.93839734.313 864.7499898.335857.72929932.188 852.058
9958.751850.4536 9975.09846.13689989.418839.161710018.03838.6375 10089.2843.1856
10112.07848.184910139.27864.1318 10147.8871.173410157.46882.1681 10195.4919.6421
10216.77937.724710229.28 945.89810241.19948.876210246.39952.000510288.37982.3195
 10305.3996.399810310.95998.874610374.691009.273 10409.71018.43510425.311020.654
#Mann= 3 , 0 , 0
9500.683    0.12       09500.683    0.12       010425.31    0.12       0
#XS Ineff= 2 , 0
       0                               0
Bank Sta=9500.683,10425.31
Exp/Cntr=0.3,0.1

Type RM Length L Ch R = 1 , 35171.7,247.787800,247.787800,247.787800
XS GIS Cut Line= 6
508617.185431516 804371.58099357508579.821796057804523.680622172
508508.663482713804650.987967192508344.648451585804897.633834581
508284.914713213805028.099381269508255.753706303805121.001110998
#Sta/Elev= 30
9616.814914.72519650.455906.29199670.704903.67699701.484895.40169732.873889.1868
9820.324877.5902 9842.66 877.4729866.053873.23619877.824868.50999889.595868.5326
9949.442849.53539961.626848.34359985.995838.00669998.179837.787510083.33842.3119
10095.88844.790610131.93844.613910143.77847.986210178.63866.555810196.22 885.807
10213.49901.437510247.24926.825510280.87948.4132 10313.4959.629210335.08964.0445
10377.95966.4189 10391.4969.495210430.55968.842610451.32971.744510457.53974.0874
#Mann= 3 , 0 , 0
9616.814  0.0544       09616.814  0.0544       010457.53  0.0544       0
#XS Ineff= 2 , 0
       0                               0
Bank Sta=9616.814,10457.53
Exp/Cntr=0.3,0.1

Type RM Length L Ch R = 1 ,34923.92,247.787800,247.787800,247.787800
XS GIS Cut Line= 6
508340.790890475804307.331385331508313.087598283804408.507528955
508186.422647338804762.645549319508162.228305329804837.387881923
508135.610424134 804943.93110299508118.938077992805054.912205799
#Sta/Elev= 30
9689.243914.69789728.199901.4389 9759.36888.90569811.586877.36699864.402874.4807
 9896.18866.0426 9928.09860.61519970.637844.88899981.274837.11889991.911834.1226
10002.55833.877810023.83835.478910055.75841.355710077.03843.129210115.91842.0211
10130.23843.626110172.76864.448910193.78880.621310207.38893.935510225.32906.2686
10246.34913.544110277.49916.524210349.53916.869510359.78913.281910369.93905.8839
10380.07901.396710400.37896.615410430.78 893.13310460.98895.298510470.96891.8834
#Mann= 3 , 0 , 0
9689.243  0.0463       09689.243  0.0463       010470.96  0.0463       0
#XS Ineff= 2 , 0
       0                               0
Bank Sta=9689.243,10470.96
Exp/Cntr=0.3,0.1