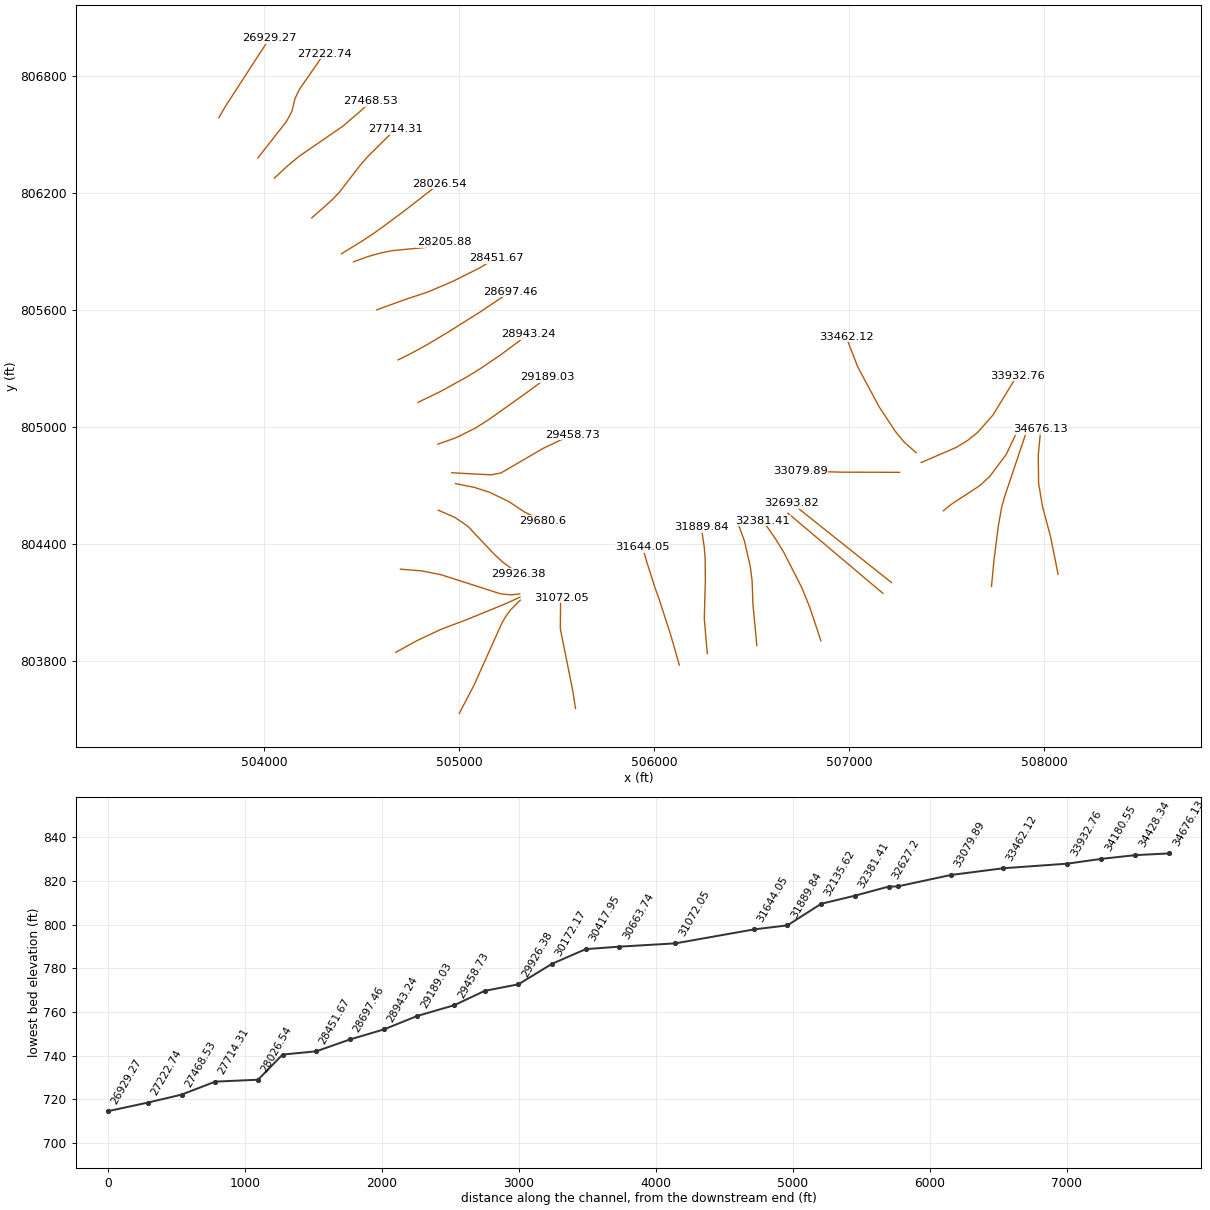
HEC-RAS study 5238_ras.prj: 5238

--- 5238_ras.g01 (geometry) --- (continued)

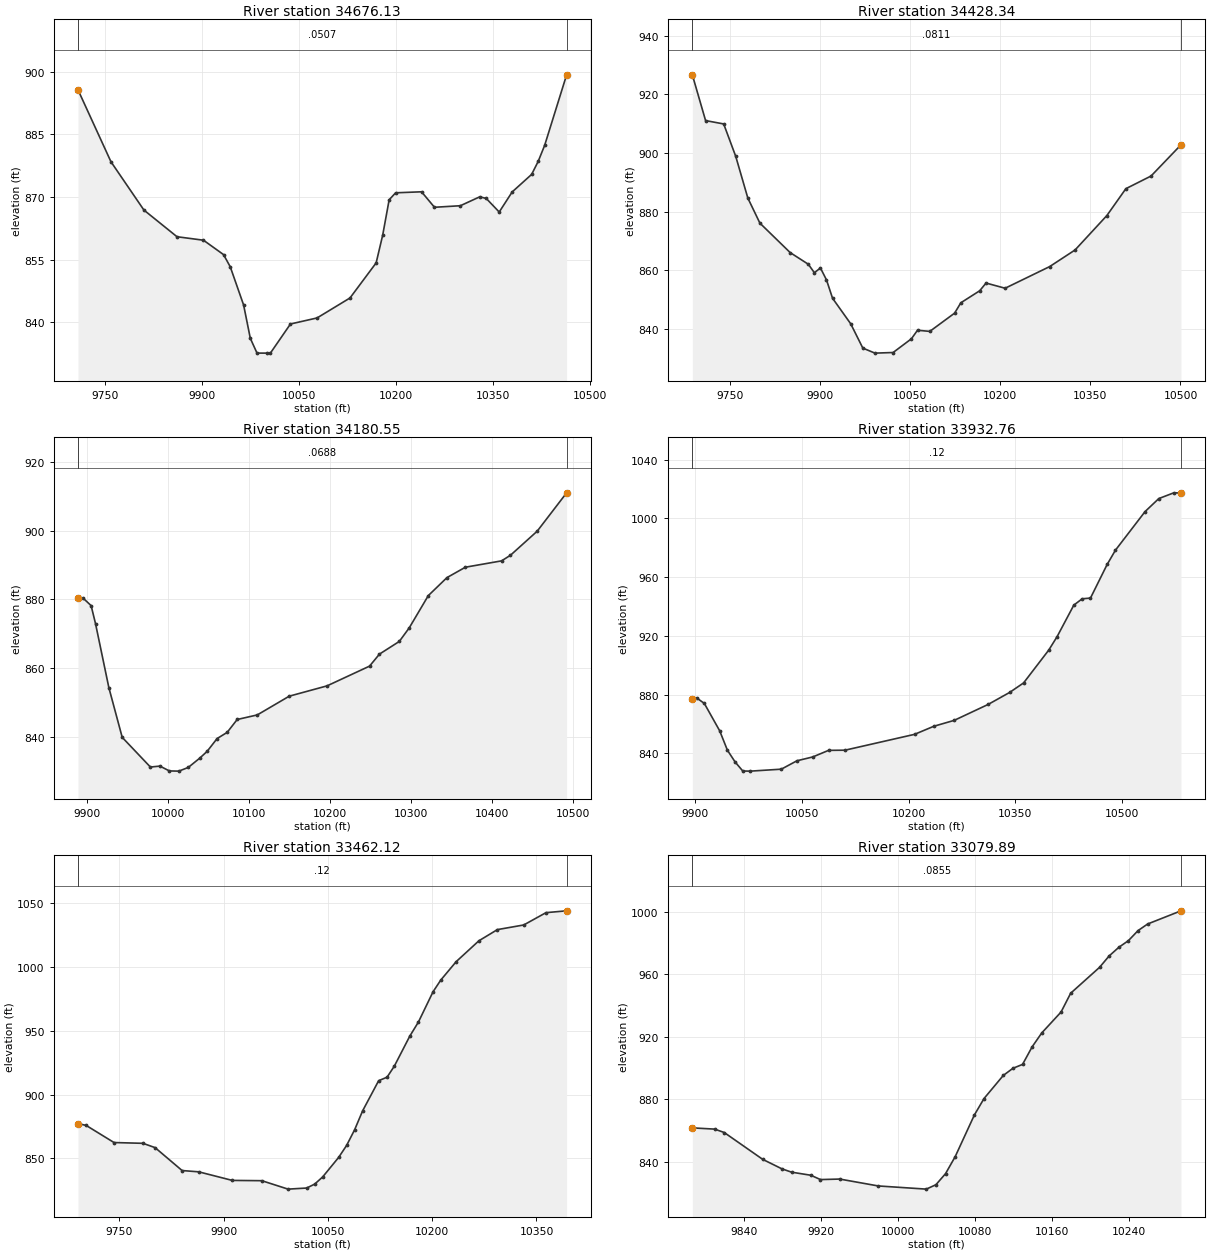
Type RM Length L Ch R = 1 ,34676.13,247.787900,247.787900,247.787900
XS GIS Cut Line= 6
508071.259990199 804244.67727254508032.817286354804437.038246246
507991.190308188804593.130862221507971.273303372804712.334052768
 507969.67330553804855.868969799507982.049472452804988.788048912
#Sta/Elev= 30
 9708.49895.64859759.518878.40799810.494 866.8449861.678860.45729902.624859.6235
9933.663856.17669944.017853.27079964.725844.10529975.079836.13169985.433832.5964
   10001832.586710006.15 832.59210037.17839.560910078.35841.011210129.29845.7956
10169.72854.1914 10179.8860.802410189.86869.307610199.88870.974910239.95 871.216
10259.95867.509410299.97867.880510329.98870.013210340.02869.627210360.09866.3745
10380.16 871.18310410.27875.384910420.31878.472110430.35882.318610464.36899.2246
#Mann= 3 , 0 , 0
 9708.49  0.0507       0 9708.49  0.0507       010464.36  0.0507       0
#XS Ineff= 2 , 0
       0                               0
Bank Sta=9708.49,10464.36
Exp/Cntr=0.3,0.1

Type RM Length L Ch R = 1 ,34428.34,247.787800,247.787800,247.787800
XS GIS Cut Line= 6
507729.842891177 804183.00777643507741.872049847804311.597830464
507765.093801112804494.499658468507781.822069432804588.501690309
 507797.55087196804644.673412022507907.788054275804972.599372506
#Sta/Elev= 30
9687.466926.66349709.509911.06689739.656 909.9219759.754898.84649779.852884.6526
 9799.95876.10779850.301866.07469880.542862.09199890.623859.19899900.703  860.83
9910.784856.75789920.864850.50049951.106 841.7959971.267833.51369991.428831.7967
10021.69832.006410052.09 836.67410062.31839.596610082.74839.204710124.06845.4283
10134.44848.960710165.81 853.05110176.39855.685610208.16853.916710282.27861.2937
10324.62866.969210377.56878.704510409.13887.8538 10451.1892.175810500.88 902.801
#Mann= 3 , 0 , 0
9687.466  0.0811       09687.466  0.0811       010500.88  0.0811       0
#XS Ineff= 2 , 0
       0                               0
Bank Sta=9687.466,10500.88
Exp/Cntr=0.3,0.1

Type RM Length L Ch R = 1 ,34180.55,247.787900,247.787900,247.787900
XS GIS Cut Line= 6
 507482.82582328804570.969388576507526.689248549804605.892173552
507669.981654012804699.833989928507721.664781853804747.851214398
 507805.06811817804859.142553385 507876.15203756805008.814286397
#Sta/Elev= 30
9888.986880.47359895.028880.44419905.212878.20849910.666 872.9599927.141854.3488
9943.616839.9123 9978.41 831.2839990.181831.554910001.89830.150410013.54830.0939
10025.19831.168210039.38833.870310048.49835.847110060.79839.5662 10073.2 841.354
 10085.6845.1033 10110.4 846.43210149.85851.881110196.55854.879910249.05 860.621
10261.28 864.11410285.76867.794510297.99871.7267 10321.6881.124910344.57886.3451
10367.38889.375510412.07891.220310423.08892.859110456.03899.845710492.38911.0003
#Mann= 3 , 0 , 0
9888.986  0.0688       09888.986  0.0688       010492.38  0.0688       0
#XS Ineff= 2 , 0
       0                               0
Bank Sta=9888.986,10492.38
Exp/Cntr=0.3,0.1

Type RM Length L Ch R = 1 ,33932.76,470.641600,470.641600,470.641600
XS GIS Cut Line= 6
507369.432741702804818.111861065507550.458232641804896.342429414
507606.420107335804930.674618647507658.366649419804972.051153883
507736.710629493805060.982212603 507861.13097626805263.636823773
#Sta/Elev= 30
9896.527877.36149902.541877.78159913.343874.03079934.947855.34279945.749842.1522
9956.551834.15679967.353827.96439978.155827.897310021.42829.226910043.37834.9475
10065.56 837.56210087.75842.039510110.87842.1638 10208.4852.947110235.43858.4445
10264.12862.485410311.68873.313110341.82881.479310361.48887.975910396.92910.4186
10408.61919.5826   10432940.974710443.69 945.28910455.39945.789210478.78968.6878
10490.47978.440210532.021004.71310551.311013.58110572.331017.48810582.431017.381
#Mann= 3 , 0 , 0
9896.527    0.12       09896.527    0.12       010582.43    0.12       0
#XS Ineff= 2 , 0
       0                               0
Bank Sta=9896.527,10582.43
Exp/Cntr=0.3,0.1

Type RM Length L Ch R = 1 ,33462.12,382.235400,382.235400,382.235400
XS GIS Cut Line= 6
507343.757533431804868.376032665507281.053013086804924.113384068
 507236.75402936804978.104381456507154.063573798805103.348316215
507044.234398654805308.295968112506984.020509619805462.994935174
#Sta/Elev= 30
9690.746877.18979702.464875.78269742.602862.32489784.185861.7199 9801.66858.3212
9840.465840.3521 9864.41839.34469912.597832.61559955.048832.38979992.835825.7739
10019.55826.627710031.05829.706810042.55 835.33610065.55850.668310077.06860.1281
10088.56  872.4110100.06887.266810123.06910.852810135.16913.617610145.49922.1742
 10167.8945.791610180.33956.979610201.25980.618610212.41989.840210234.531004.273
10267.171020.62810293.761029.40510331.681033.04910363.671042.70910393.311044.144
#Mann= 3 , 0 , 0
9690.746    0.12       09690.746    0.12       010393.31    0.12       0
#XS Ineff= 2 , 0
       0                               0
Bank Sta=9690.746,10393.31
Exp/Cntr=0.3,0.1

Type RM Length L Ch R = 1 ,33079.89,386.062200,386.062200,386.062200
XS GIS Cut Line= 3
507258.160886616804767.849738151506959.567932665804768.845047981
506750.401638279804774.313785736
#Sta/Elev= 30
 9785.85861.82139809.011861.03989819.011 858.8619859.011841.69569879.011835.6242
9889.011833.51499909.011831.54619919.011828.77949939.011829.11459979.012 824.712
10029.01822.678610039.01825.503810049.01832.577910059.01 843.42710079.01870.1225
10089.01880.599710109.02895.346310119.02899.900410129.03902.393210139.03913.6662
10149.03922.537110169.04935.864110179.04947.881710209.05964.430610219.06971.7356
10229.06977.226810239.07981.497210249.07987.925310259.07992.145910293.681000.551
#Mann= 3 , 0 , 0
 9785.85  0.0855       0 9785.85  0.0855       010293.68  0.0855       0
#XS Ineff= 2 , 0
       0                               0
Bank Sta=9785.85,10293.68
Exp/Cntr=0.3,0.1

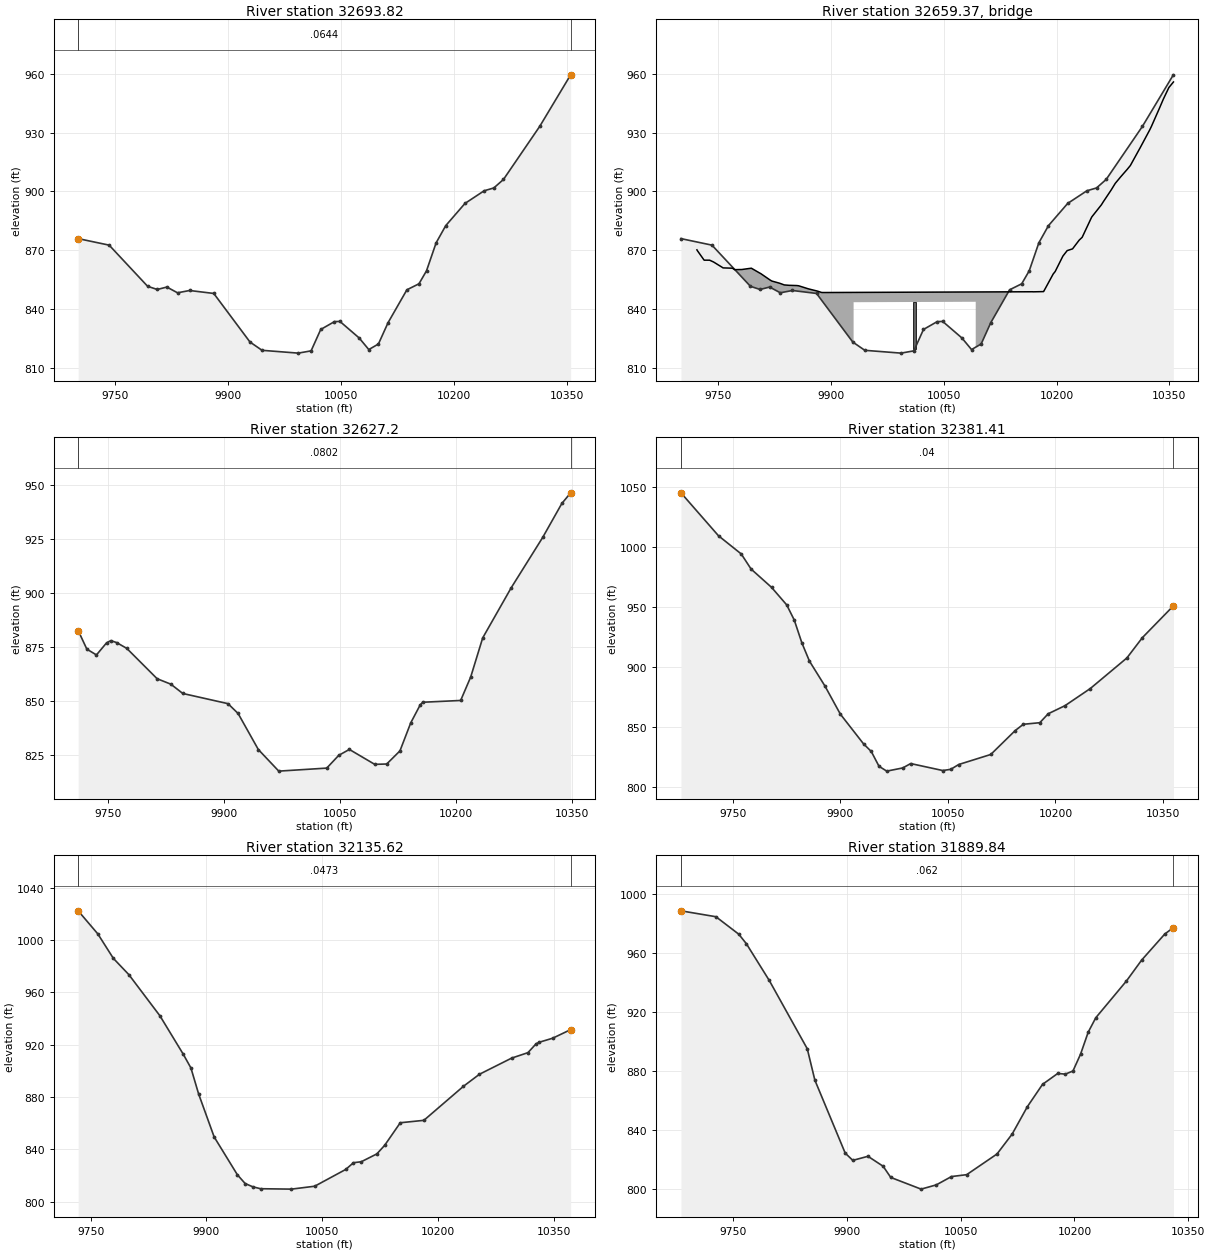
Type RM Length L Ch R = 1 ,32693.82,66.629500,66.629500,66.629500
XS GIS Cut Line= 2
507217.238658965804202.670903146506705.085881144804610.657014236
#Sta/Elev= 30
 9700.41875.88989741.627872.55949792.768 851.5669805.553849.94659818.338 851.179
9832.543848.24959848.592849.42739880.691847.92279928.839 823.1519944.889818.9141
9993.037817.479810010.11818.6381 10022.9829.550910041.18833.554710048.47833.6462
10074.04825.203310086.82819.295210099.61822.1314 10112.4832.988710137.48849.7856
10153.53852.845510163.54859.466410176.32873.730210189.11882.500810214.68893.8389
10240.25900.300510253.03901.731610265.88906.073910314.02933.1113 10355.2959.4371
#Mann= 3 , 0 , 0
 9700.41  0.0644       0 9700.41  0.0644       0 10355.2  0.0644       0
#XS Ineff= 2 , 0
       0                               0
Bank Sta=9700.41,10355.2
Exp/Cntr=0.3,0.1

Type RM Length L Ch R = 3 ,32659.37,,,
BEGIN DESCRIPTION:
END DESCRIPTION:
Bridge Culvert--1,0,-1,-1, 0
Deck Dist Width WeirC Skew NumUp NumDn MinLoCord MaxHiCord MaxSubmerge Is_Ogee
22.980150,20.669200,2.6,0, 60, 60, , , 0.95, 0, 0,0,,
 9721.65 9722.04 9731.22 9738.57 9743.77 9755.11 9756.33 9768.88 9771.64 9781.44
 9788.18 9794.00 9804.71 9806.55 9819.11 9821.25 9831.67 9837.79 9844.22 9854.32
 9856.78 9869.33 9870.86 9881.89 9887.39 9889.28 9929.99 9929.9910092.3910092.39
10165.2310167.2810169.0910182.2610182.6510195.4210198.0310198.7410208.3210213.99
10221.1410229.9910233.9510245.9810246.7610259.5810261.9810272.3910277.9710285.20
10293.9610298.0210309.9610310.8310323.6410325.9510336.4610341.9510349.2710355.34
  870.17  869.86  864.90  864.88  863.96  861.28  860.96  860.80  860.06  860.13
  860.50  860.80  858.42  858.04  854.73  854.25  853.13  852.27  852.07  851.95
  851.85  850.33  850.17  849.12  848.42  848.39  848.45  848.45  848.68  848.68
  848.78  848.79  848.75  848.86  848.86  857.85  859.09  859.64  866.98  869.77
  870.66  875.12  876.56  886.37  886.96  893.17  894.65  900.62  904.09  907.42
  911.27  913.17  921.48  922.07  931.24  933.05  942.18  947.09  952.96  955.79
 -129.83 -130.14 -135.10 -135.12 -136.04 -138.72 -139.04 -139.20 -139.94 -139.87
 -139.50 -139.20 -141.58 -141.96 -145.27 -145.75 -146.87 -147.73 -147.93 -148.05
 -148.15 -149.67 -149.83 -150.88 -151.58 -151.61 -151.55  843.45  843.68 -151.32
 -151.22 -151.21 -151.25 -151.14 -151.14 -142.15 -140.91 -140.36 -133.02 -130.23
 -129.34 -124.88 -123.44 -113.63 -113.04 -106.83 -105.35  -99.38  -95.91  -92.58
  -88.73  -86.83  -78.52  -77.93  -68.76  -66.95  -57.82  -52.91  -47.04  -44.21
 9721.65 9722.04 9731.22 9738.57 9743.77 9755.11 9756.33 9768.88 9771.64 9781.44
 9788.18 9794.00 9804.71 9806.55 9819.11 9821.25 9831.67 9837.79 9844.22 9854.32
 9856.78 9869.33 9870.86 9881.89 9887.39 9889.28 9945.84 9945.8410108.2410108.24
10165.2310167.2810169.0910182.2610182.6510195.4210198.0310198.7410208.3210213.99
10221.1410229.9910233.9510245.9810246.7610259.5810261.9810272.3910277.9710285.20
10293.9610298.0210309.9610310.8310323.6410325.9510336.4610341.9510349.2710355.34
  870.17  869.86  864.90  864.88  863.96  861.28  860.96  860.80  860.06  860.13
  860.50  860.80  858.42  858.04  854.73  854.25  853.13  852.27  852.07  851.95
  851.85  850.33  850.17  849.12  848.42  848.39  848.47  848.47  848.70  848.70
  848.78  848.79  848.75  848.86  848.86  857.85  859.09  859.64  866.98  869.77
  870.66  875.12  876.56  886.37  886.96  893.17  894.65  900.62  904.09  907.42
  911.27  913.17  921.48  922.07  931.24  933.05  942.18  947.09  952.96  955.79
 -129.83 -130.14 -135.10 -135.12 -136.04 -138.72 -139.04 -139.20 -139.94 -139.87
 -139.50 -139.20 -141.58 -141.96 -145.27 -145.75 -146.87 -147.73 -147.93 -148.05
 -148.15 -149.67 -149.83 -150.88 -151.58 -151.61 -151.53  843.47  843.70 -151.30
 -151.22 -151.21 -151.25 -151.14 -151.14 -142.15 -140.91 -140.36 -133.02 -130.23
 -129.34 -124.88 -123.44 -113.63 -113.04 -106.83 -105.35  -99.38  -95.91  -92.58
  -88.73  -86.83  -78.52  -77.93  -68.76  -66.95  -57.82  -52.91  -47.04  -44.21
Pier Skew, UpSta & Num, DnSta & Num=  ,10011.19, 2 ,10027.04, 2 , 0 , 0 , 0 ,,
    4.00    4.00
 -151.44  848.56
    4.00    4.00
 -151.41  848.59
BR Coef=-1 , 0 , 0 ,, 0 ,,,0.8,0,1,0,
WSPro=,,,, 1 ,,,, 0 ,,,, 0 ,,,,-1 ,-1 ,-1 , 0 , 0 , 0 , 0 , 0
BC Design=,, 0 ,, 0 ,,,,,,

Type RM Length L Ch R = 1 , 32627.2,245.785500,245.785500,245.785500
XS GIS Cut Line= 2
507173.070552695804147.760838146506686.264699669804558.340863649
#Sta/Elev= 30
9711.321882.45719722.549873.8329 9734.96871.14899748.042876.7461 9753.57877.7686
9761.124876.86419774.206874.17769813.452860.13579831.123857.62779846.634853.3132
9905.025848.60629918.106844.0715 9944.27827.38669970.718817.378910032.76818.7783
10048.27824.690410062.01827.4204 10094.8820.514810110.31 820.67710127.42826.7481
10141.33839.693110153.58 848.01610156.84849.255410205.91850.083610218.89860.9298
 10234.4879.023210271.32902.266210311.95925.506510336.73941.236710348.15 946.176
#Mann= 3 , 0 , 0
9711.321  0.0802       09711.321  0.0802       010348.15  0.0802       0
#XS Ineff= 2 , 0
       0                               0
Bank Sta=9711.321,10348.15
Exp/Cntr=0.3,0.1

Type RM Length L Ch R = 1 ,32381.41,245.785600,245.785600,245.785600
XS GIS Cut Line= 6
506855.199941746803904.970272742506798.379228848804075.632081054
506757.724878302804176.055141829506664.888979703804358.333437758
506623.714546911804425.234466322506557.738017135804520.347970523
#Sta/Elev= 30
9677.4491045.3559729.8211009.5289761.537994.37649775.297981.76859803.824966.5116
9824.968951.8826 9835.54939.23749846.112920.24119856.683905.01789878.246884.3016
9899.823860.75879932.188835.96729942.977829.60659953.765817.26079964.553813.2148
9986.825815.85719997.981819.527310042.66813.720610053.82814.702510064.99818.7375
 10109.7827.105610143.77847.037810155.13 852.293 10178.1853.605210189.84861.0621
10213.33867.835910248.56882.106510299.66907.639110321.26924.569910364.59951.1427
#Mann= 3 , 0 , 0
9677.449    0.04       09677.449    0.04       010364.59    0.04       0
#XS Ineff= 2 , 0
       0                               0
Bank Sta=9677.449,10364.59
Exp/Cntr=0.3,0.1

Type RM Length L Ch R = 1 ,32135.62,245.785500,245.785500,245.785500
XS GIS Cut Line= 6
506526.976778048803879.722337091506506.658193693804095.281097371
506502.731546301804210.992054595506493.240303654 804285.01499989
 506463.82538203804414.349836549506430.576938671 804506.60082692
#Sta/Elev= 30
9733.8731022.1969759.3031004.5869779.423 985.8869799.544973.41429839.781941.9479
9869.876 912.7249879.908902.10589889.939882.14869910.003849.39359940.098 820.468
9950.129813.80939960.132811.27189970.133809.824110010.14809.516910040.19 811.732
10080.38824.556610090.46829.706110100.54830.4405 10120.7836.433910130.79842.9585
10151.05860.2432 10181.6862.087910232.92888.130310253.59897.304710295.34 909.658
10316.39913.810710326.92920.554110330.84 921.733 10348.4924.845410371.71931.4066
#Mann= 3 , 0 , 0
9733.873  0.0473       09733.873  0.0473       010371.71  0.0473       0
#XS Ineff= 2 , 0
       0                               0
Bank Sta=9733.873,10371.71
Exp/Cntr=0.3,0.1

Type RM Length L Ch R = 1 ,31889.84,245.785500,245.785500,245.785500
XS GIS Cut Line= 6
506272.876893171803839.204787189506257.638940646804017.096312502
506262.969933346804217.366062325506261.896226984804327.281550139
506257.490195935804383.138047633 506242.34679897804486.251622612
#Sta/Elev= 30
9681.345988.69949727.412984.69379757.565972.81599767.616966.3215 9797.77941.3742
9847.838  894.999857.851873.68499897.855 824.1069907.855819.17489927.865821.9429
9947.878 815.1619957.884 807.593 9997.91 799.64110017.93802.525710037.95808.1865
10057.97809.456410097.97823.520510117.97837.085210137.98855.646610157.99870.8248
10178.02878.227210188.05 877.77210198.08 879.89410208.12891.360410218.15906.2263
10228.19916.080610268.54941.010510288.72955.288310319.12972.936110330.55977.3472
#Mann= 3 , 0 , 0
9681.345   0.062       09681.345   0.062       010330.55   0.062       0
#XS Ineff= 2 , 0
       0                               0
Bank Sta=9681.345,10330.55
Exp/Cntr=0.3,0.1

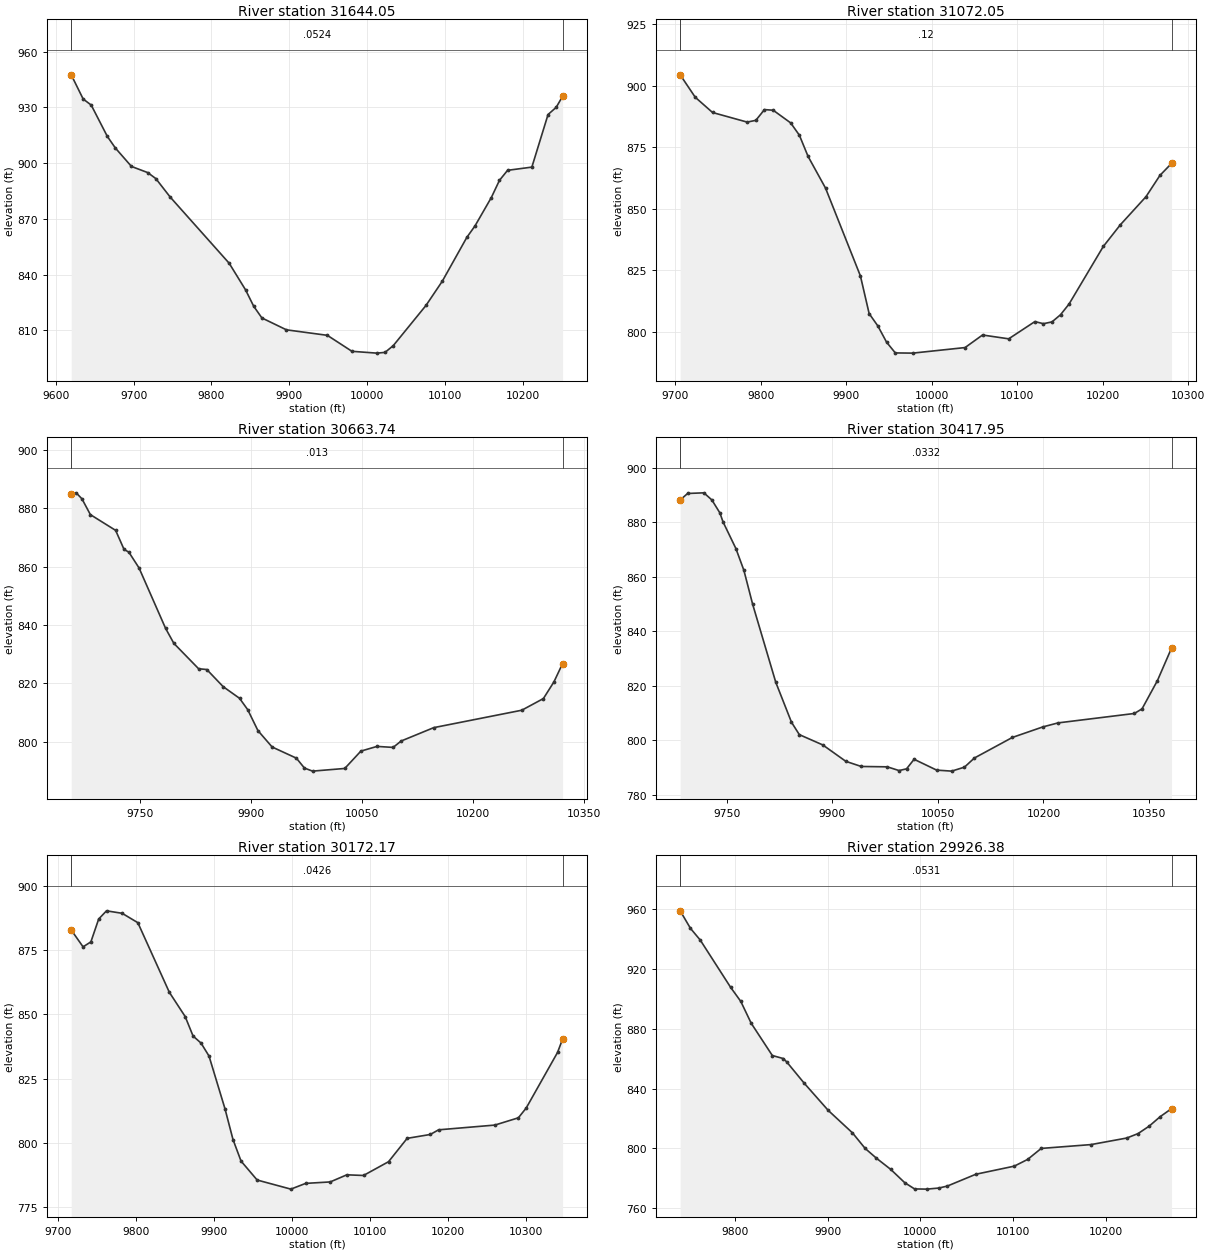
Type RM Length L Ch R = 1 ,31644.05,572.000400,572.000400,572.000400
XS GIS Cut Line= 6
506129.214673719 803780.18077454 506085.08737907803935.564789988
506025.603955749804118.681301413506003.960301872804178.854451658
505963.864157205804304.630860379505941.499314459 804382.98983661
#Sta/Elev= 30
9619.755947.51659635.091934.4934 9645.44931.24099666.137914.38819676.486908.1335
9697.184898.21339718.066894.91329728.508 891.6799746.841881.79649822.767846.1287
9843.796831.8323 9854.31822.97269864.825816.69179896.368810.3066 9948.94 807.347
9980.561798.746210012.47797.770110023.08798.1641 10033.7  801.8210075.73823.4349
10096.72836.4901 10128.2860.0374 10138.7866.210110159.69881.473810170.18890.7478
10180.59896.132910211.81897.858810232.62926.160910243.02929.997710251.29935.9192
#Mann= 3 , 0 , 0
9619.755  0.0524       09619.755  0.0524       010251.29  0.0524       0
#XS Ineff= 2 , 0
       0                               0
Bank Sta=9619.755,10251.29
Exp/Cntr=0.3,0.1

Type RM Length L Ch R = 1 ,31072.05,408.312800,408.312800,408.312800
XS GIS Cut Line= 5
505597.228349209803557.581384704 505582.98595041803650.156976849
505519.519594193803965.708543763505520.829051882804111.250474781
505524.456088126804124.325662747
#Sta/Elev= 30
9705.824 904.4019723.448 895.2939743.683889.10419784.154 885.2079794.271 885.918
9804.429890.28269814.629890.0247 9835.03 884.888 9845.23879.8851 9855.43871.2632
9875.831858.39979916.632822.73469926.832807.45219937.032802.42699947.232 795.836
9957.433791.48249977.833791.396310039.03793.654310059.44798.757910090.04 797.203
10120.64804.194210130.65803.354110140.65804.069710150.65806.979810160.65811.3393
10200.65834.693110220.66843.522510250.66854.937910266.91863.553710280.48868.4227
#Mann= 3 , 0 , 0
9705.824    0.12       09705.824    0.12       010280.48    0.12       0
#XS Ineff= 2 , 0
       0                               0
Bank Sta=9705.824,10280.48
Exp/Cntr=0.3,0.1

Type RM Length L Ch R = 1 ,30663.74,245.785500,245.785500,245.785500
XS GIS Cut Line= 6
505001.825097734803532.263730773505077.313676356803677.419220078
505220.490384505803996.040599126505238.388707064804026.749952585
505263.469649548804061.676068627505314.163362981804112.609858179
#Sta/Elev= 30
9657.259885.1178 9663.93885.36239671.741883.30429683.111877.88389717.221872.4827
9728.591865.9431 9735.03865.02349748.783859.61189784.626838.89369795.812833.7308
9829.269825.00859840.322824.74869862.427818.86489884.533 814.8769895.585810.9651
9909.372803.79219928.543798.16659961.282794.33979972.195790.93629983.108789.8892
10026.64790.8042 10048.4796.757710070.16798.367810091.92 798.028 10102.8800.2205
10146.79804.808310265.65810.782510294.86814.782910309.12820.517510320.76826.7915
#Mann= 3 , 0 , 0
9657.259   0.013       09657.259   0.013       010320.76   0.013       0
#XS Ineff= 2 , 0
       0                               0
Bank Sta=9657.259,10320.76
Exp/Cntr=0.3,0.1

Type RM Length L Ch R = 1 ,30417.95,245.785500,245.785500,245.785500
XS GIS Cut Line= 6
504675.900668453803845.179440524504787.810272162803906.802731152
504905.416740821803961.838888839505042.021275988804013.714879934
 505239.19879114 804094.36370351505312.802167069804128.036745302
#Sta/Elev= 30
9684.098888.20219694.663890.57929717.762890.81869729.126888.2004 9740.49883.4545
9744.918880.18359763.218870.38949774.582862.39569787.021849.95929819.879821.3223
9842.163806.69749853.305802.14099886.552798.3767 9919.39792.34129941.282790.4631
9978.159790.33219994.915788.967910005.61789.597710016.29 793.10410048.33789.1278
10069.69788.757110087.86790.222710101.89793.559410155.91801.115710199.12804.9724
10220.73806.444710329.07809.899110339.99811.590310361.83 821.94510381.87833.8705
#Mann= 3 , 0 , 0
9684.098  0.0332       09684.098  0.0332       010381.87  0.0332       0
#XS Ineff= 2 , 0
       0                               0
Bank Sta=9684.098,10381.87
Exp/Cntr=0.3,0.1

Type RM Length L Ch R = 1 ,30172.17,245.785600,245.785600,245.785600
XS GIS Cut Line= 6
 504699.81511596804271.591072537504810.478205479804262.459119538
504906.632542959804243.346816301505213.681625424804145.049552997
 505265.41397371804139.795469468505311.356344359804144.422735983
#Sta/Elev= 30
9716.817882.70929732.006876.17599742.017 878.0989752.042886.99269762.066890.1672
9782.131889.20499802.272885.55559842.667858.51599862.965849.09919873.114841.5221
9883.325838.78719893.574833.73769914.072813.23449924.321801.30899934.643792.9459
9955.315785.58149998.549782.045810017.53784.276310049.04784.842710070.33787.6045
10091.74787.351310123.86792.702110147.72801.772910177.38  803.2810188.05805.0862
10260.23806.9282 10290.4809.753910300.42813.551510340.63 835.146 10347.1840.3269
#Mann= 3 , 0 , 0
9716.817  0.0426       09716.817  0.0426       0 10347.1  0.0426       0
#XS Ineff= 2 , 0
       0                               0
Bank Sta=9716.817,10347.1
Exp/Cntr=0.3,0.1

Type RM Length L Ch R = 1 ,29926.38,245.785500,245.785500,245.785500
XS GIS Cut Line= 6
504894.478158649804573.831059917504979.966380191804536.278223585
505045.251608064804491.681765444505177.093921597804351.673887571
505224.053469525804307.950981328 505305.12355025804248.001528711
#Sta/Elev= 30
9740.917959.04399752.014947.30779762.625939.42649795.253907.90549806.322898.3871
9817.585883.73319840.371 862.1289852.149860.10969855.788857.92029874.715843.6352
9900.764825.33259926.888810.2994 9940.54799.90779952.774793.31929968.101785.8874
9983.272776.95189993.875772.774610007.04 772.63710020.15 773.36410029.39774.7203
   10060782.6014 10101.5788.0322 10115.9 792.52910130.57799.903610184.31802.4693
10222.81806.852310235.04809.823410247.04814.806610259.05821.2167 10271.2826.5413
#Mann= 3 , 0 , 0
9740.917  0.0531       09740.917  0.0531       0 10271.2  0.0531       0
#XS Ineff= 2 , 0
       0                               0
Bank Sta=9740.917,10271.2
Exp/Cntr=0.3,0.1

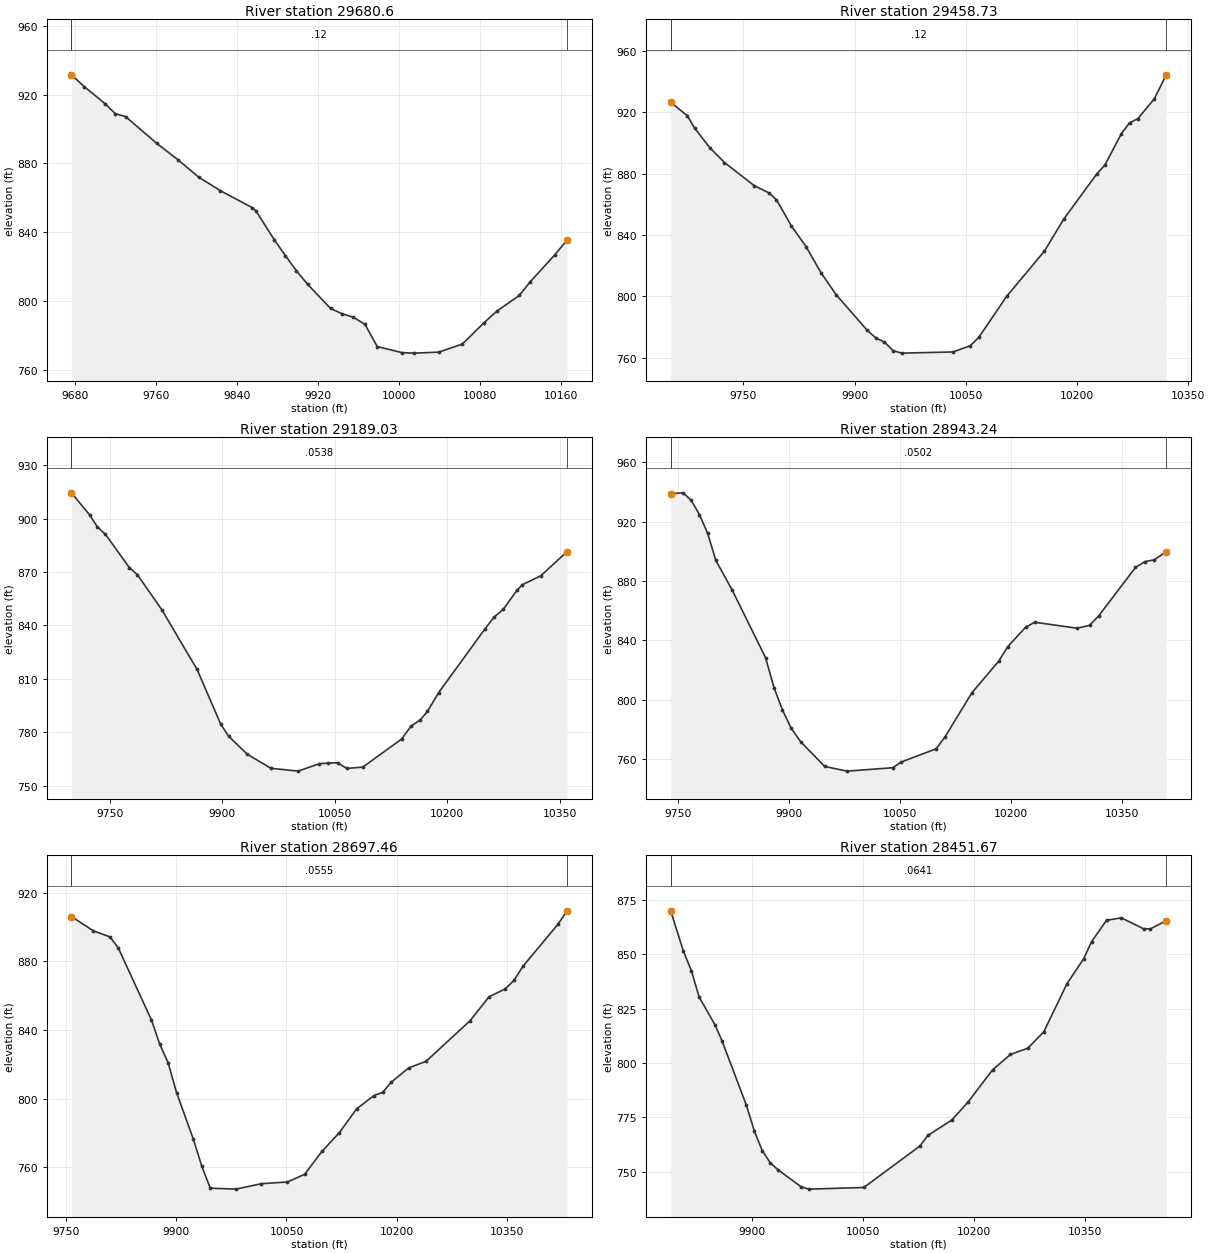
Type RM Length L Ch R = 1 , 29680.6,221.867300,221.867300,221.867300
XS GIS Cut Line= 6
504982.338481584804710.245771821505078.392628582804690.884549987
505158.775273199804664.867549992505254.463752717804618.598022152
505337.451827503804563.595415788505428.113558771804520.718504173
#Sta/Elev= 30
9676.592931.50399689.442924.51729709.739914.76789719.887908.91589730.036907.1854
9760.859 891.6029781.505882.1817 9802.33871.92729823.341864.21089855.144 854.198
9858.747852.28899876.777835.51959887.643826.3942 9898.51817.55069909.613809.6852
9932.219795.66899943.522792.54269954.826790.51879966.174786.40479978.323773.4685
 10002.7769.946510014.98769.6478 10038.9770.212510062.27774.8875 10083.6787.2807
10096.27794.045510118.46803.182210129.45 811.26210153.62 826.87810165.51835.3473
#Mann= 3 , 0 , 0
9676.592    0.12       09676.592    0.12       010165.51    0.12       0
#XS Ineff= 2 , 0
       0                               0
Bank Sta=9676.592,10165.51
Exp/Cntr=0.3,0.1

Type RM Length L Ch R = 1 ,29458.73,269.703800,269.703800,269.703800
XS GIS Cut Line= 5
504962.537304043804765.620330352505164.520489812804755.113360852
 505215.77866137804765.000000015505431.323617578  804890.6324099
 505579.59259023 804961.47611856
#Sta/Elev= 30
9652.021926.63019674.514917.78559684.528909.63249704.555 897.1069724.582887.3489
9764.636872.30759784.663867.49249794.677863.07199814.704846.09419834.731832.4159
9854.766815.46429875.135801.20339917.154777.91289928.729772.95679940.303770.2967
9951.878 764.7479963.453763.0754 10032.9763.839410056.05767.928110067.62 773.365
10105.06800.079910155.97829.518610182.21850.507610226.54879.819910237.62 885.728
10259.79 906.06910270.87 913.23610281.95915.905510304.12928.761610320.29944.5148
#Mann= 3 , 0 , 0
9652.021    0.12       09652.021    0.12       010320.29    0.12       0
#XS Ineff= 2 , 0
       0                               0
Bank Sta=9652.021,10320.29
Exp/Cntr=0.3,0.1

Type RM Length L Ch R = 1 ,29189.03,245.785500,245.785500,245.785500
XS GIS Cut Line= 6
504891.870774056804912.475520652504981.901137527804944.062617056
505079.828614478804992.400117363505151.708866407805037.515505064
505363.634355759805188.298617102505452.901204674805254.971866375
#Sta/Elev= 30
9698.751 914.4499722.912902.07419733.505895.23729744.171 891.1449776.171872.3708
9786.838868.43119819.545848.6312 9866.38815.25149897.995784.45299908.353777.8164
9933.182 767.6899964.786759.769410001.21758.1559 10029.2762.291910041.47762.6896
10053.74762.838310066.01759.673810087.47760.413910139.22776.164910151.92783.4768
10164.19786.924710173.73791.697310188.74802.298510250.13837.870410262.61844.6558
10275.09849.101310293.04859.659810300.05862.796410325.01867.867810359.84 881.389
#Mann= 3 , 0 , 0
9698.751  0.0538       09698.751  0.0538       010359.84  0.0538       0
#XS Ineff= 2 , 0
       0                               0
Bank Sta=9698.751,10359.84
Exp/Cntr=0.3,0.1

Type RM Length L Ch R = 1 ,28943.24,245.785500,245.785500,245.785500
XS GIS Cut Line= 6
504789.698209764 805126.39932715504908.359326602805184.019365784
505036.614768891805254.559214597505103.470290907805295.436526152
505210.627152731805368.064091834505357.623199782805477.287211097
#Sta/Elev= 30
9739.871938.88479756.678939.45659767.662934.39329778.646924.8015 9789.63912.3951
 9800.75894.02879823.181 873.7259868.044828.35699879.385808.23429890.789793.2206
9902.193781.18989915.458771.76469947.809755.12739977.866751.950110039.74754.2444
10051.46758.1291 10098.4766.987710110.48775.056710146.72804.754610182.96826.0437
10195.04835.7922 10219.2848.833210231.41852.2771 10288.7848.243610305.66850.1623
10318.03856.591910367.68889.184410380.39 893.121 10393.1894.335610409.15899.7418
#Mann= 3 , 0 , 0
9739.871  0.0502       09739.871  0.0502       010409.15  0.0502       0
#XS Ineff= 2 , 0
       0                               0
Bank Sta=9739.871,10409.15
Exp/Cntr=0.3,0.1

Type RM Length L Ch R = 1 ,28697.46,245.785600,245.785600,245.785600
XS GIS Cut Line= 6
504688.090375706805344.320462907 504753.87431241805376.999340681
504838.621679744 805423.53607414504936.821615348805481.971828089
505112.123432885805592.238507133505264.482220098805694.616163697
#Sta/Elev= 30
9757.068906.12159787.115897.73819809.447 894.2849820.613888.07529866.032845.9286
 9877.44831.70869888.849820.90379900.257803.60839923.074776.60579934.609760.8122
9946.217747.94619981.038747.395510015.95750.563910051.14751.536110074.77756.0282
 10098.4769.361310122.02780.248910145.65794.150410169.28801.882210181.09803.7551
10192.91809.703210216.54817.994210240.16821.794110300.03845.397110325.95859.3565
10348.02863.977810360.02868.925910372.02 877.076 10420.5901.899810432.15 909.437
#Mann= 3 , 0 , 0
9757.068  0.0555       09757.068  0.0555       010432.15  0.0555       0
#XS Ineff= 2 , 0
       0                               0
Bank Sta=9757.068,10432.15
Exp/Cntr=0.3,0.1

Type RM Length L Ch R = 1 ,28451.67,245.785500,245.785500,245.785500
XS GIS Cut Line= 6
504578.988835261805601.029969827504713.959884699805650.323393169
504839.417788801805692.010639032504967.470158431805746.300219306
505100.614854184805812.839613189505190.835085871805866.459476888
#Sta/Elev= 30
9790.348869.98139807.495 851.4689818.176842.5097 9828.81830.30689850.078817.5741
9859.582810.22769892.613780.48479903.247768.69979913.881759.69859924.515754.1883
9935.136750.86089966.667742.98769977.178741.960310051.01742.717710126.62761.7676
10137.48766.641210170.07773.815110191.79782.047410224.73 796.817   10249803.9167
10272.22 806.75410293.89814.292110325.33836.516910347.88 847.98610358.54855.8403
10378.62865.631210398.69866.748810428.61861.733310437.75861.675710459.18 865.414
#Mann= 3 , 0 , 0
9790.348  0.0641       09790.348  0.0641       010459.18  0.0641       0
#XS Ineff= 2 , 0
       0                               0
Bank Sta=9790.348,10459.18
Exp/Cntr=0.3,0.1

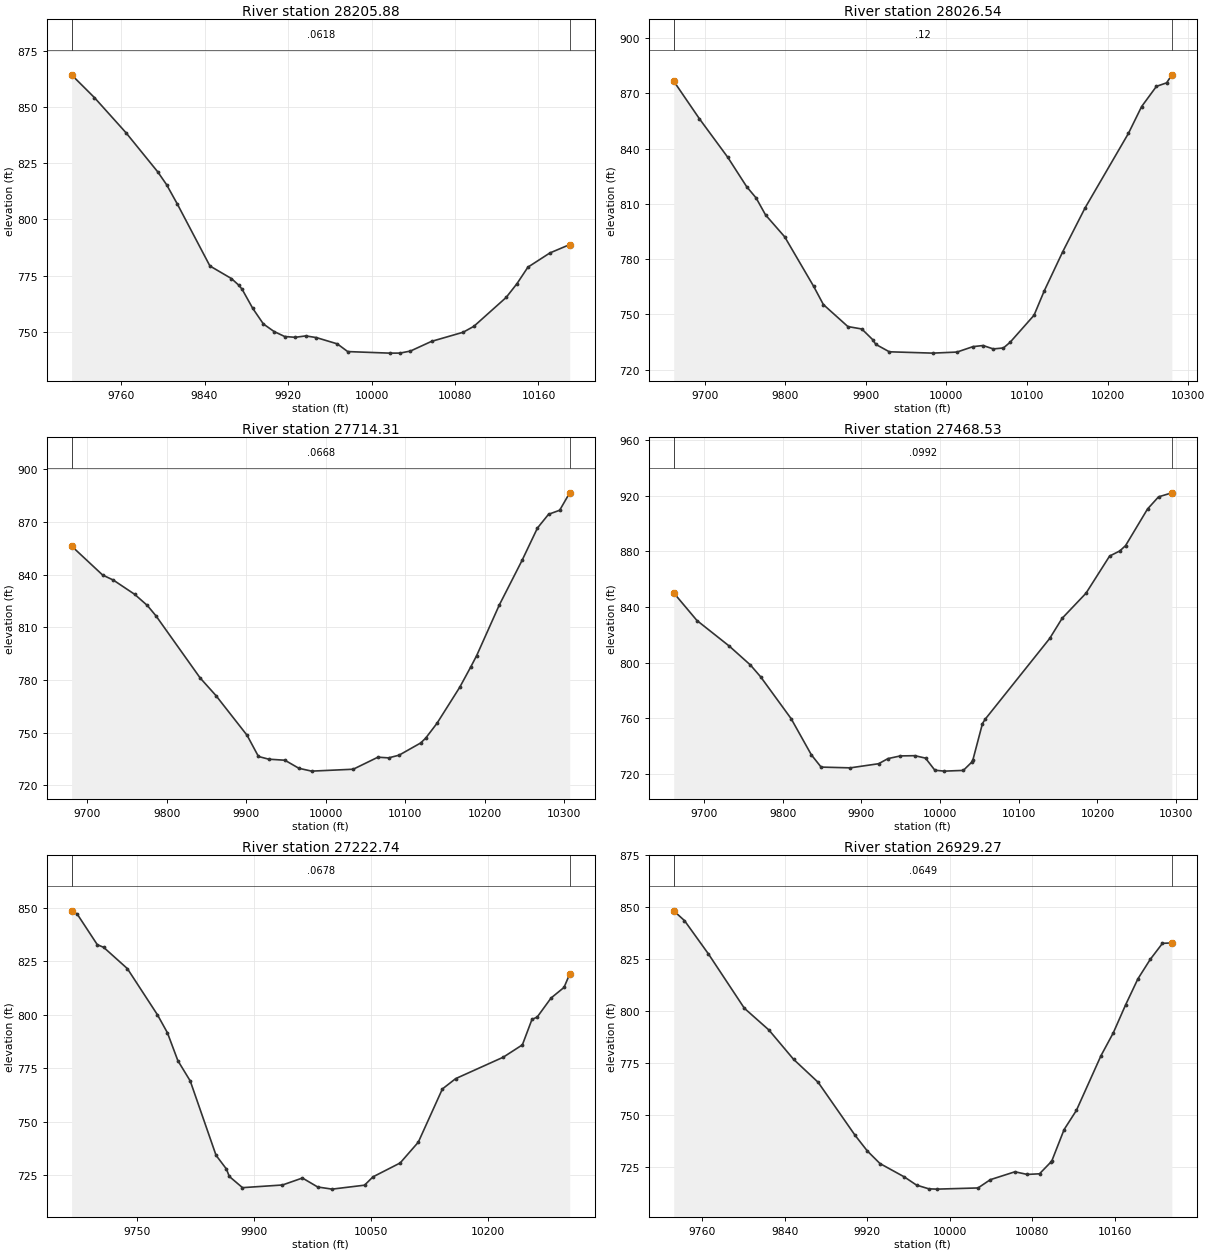
Type RM Length L Ch R = 1 ,28205.88,179.343900,179.343900,179.343900
XS GIS Cut Line= 6
504459.201626956805847.069400751 504535.93039497805874.725874236
504598.426220729805892.298362136504658.148705075805904.303197799
504824.362259766805920.329657667504923.005970329805948.672872134
#Sta/Elev= 30
9712.626864.30999734.465854.2101 9764.75838.55599795.218821.11719803.627815.4536
9814.014806.76789845.178779.2501 9865.83773.63819872.834770.6944 9876.03768.8829
 9886.23760.3782 9896.43753.4293 9906.63750.0871 9916.83747.8559 9926.94747.5076
9937.008748.12919947.077747.39529967.203744.58929977.213741.154610017.26740.4659
10027.27740.480910037.29741.3897 10057.5745.698310087.84749.764510098.13752.4152
   10129765.236710139.37771.372310149.84778.716310170.92785.042610189.91788.7712
#Mann= 3 , 0 , 0
9712.626  0.0618       09712.626  0.0618       010189.91  0.0618       0
#XS Ineff= 2 , 0
       0                               0
Bank Sta=9712.626,10189.91
Exp/Cntr=0.3,0.1

Type RM Length L Ch R = 1 ,28026.54,312.227200,312.227200,312.227200
XS GIS Cut Line= 6
504397.921817863 805888.50259038504504.440909572805954.087238845
504558.591672318805989.913323557504608.305261944806025.143670556
504716.011149672806105.192669032504900.110118099806247.982040592
#Sta/Elev= 30
9661.566876.65069693.365 856.2819728.596835.32279752.083819.34479763.826813.2138
 9775.57803.98229799.318 792.0819835.289765.17159847.279755.32999877.679743.3815
9894.974742.05689908.466736.27669912.269733.73129929.106729.67829983.002728.9515
10013.07729.530110032.95732.483110045.45733.083310058.09731.235610070.74731.7666
10079.03734.860210108.71749.536110121.37762.7787 10144.3784.019610171.99807.8017
10225.88848.3359 10242.2862.856410260.57 873.82110273.23875.7291 10279.7880.0791
#Mann= 3 , 0 , 0
9661.566    0.12       09661.566    0.12       0 10279.7    0.12       0
#XS Ineff= 2 , 0
       0                               0
Bank Sta=9661.566,10279.7
Exp/Cntr=0.3,0.1

Type RM Length L Ch R = 1 ,27714.31,245.785500,245.785500,245.785500
XS GIS Cut Line= 6
504245.275122567806072.023044562504344.510854463806159.822524132
504385.715492283806202.079651775504486.788352102806333.553702998
504531.024412952806385.161183316504674.045038231806526.940233159
#Sta/Elev= 30
9680.288856.21129719.435839.70039732.867836.84179759.733828.7201 9775.63822.3911
9786.598816.43099842.155781.0893 9861.94  771.129901.202748.44829915.471736.4177
9928.343734.87649948.757734.27989966.351729.69419982.392728.072510034.74729.1539
10065.81736.005210079.25735.621810092.42737.151610119.56744.0879 10125.8746.7821
10140.11755.272810168.69 775.74410182.67787.411410189.98793.734810218.59822.6716
 10247.2848.038210266.58866.473910280.56874.302210294.55876.6011 10307.2886.5217
#Mann= 3 , 0 , 0
9680.288  0.0668       09680.288  0.0668       0 10307.2  0.0668       0
#XS Ineff= 2 , 0
       0                               0
Bank Sta=9680.288,10307.2
Exp/Cntr=0.3,0.1

Type RM Length L Ch R = 1 ,27468.53,245.785500,245.785500,245.785500
XS GIS Cut Line= 6
504053.654640524806275.622245706504119.026353495806336.992843664
504179.508575436806387.118919584 504404.34950402 806542.00117742
504499.722280926806623.587206273504547.132660522806669.808292658
#Sta/Elev= 30
9661.495850.16879691.031830.3154 9732.01811.98939758.928798.38859771.916789.9144
9810.731759.8066  9836.5733.7683 9848.84725.01419885.861724.47569921.895727.4411
9933.816731.12219949.527 733.048  9967.9733.21269981.497731.46469993.418722.7625
10005.41722.1208 10029.6722.642110040.05728.4474 10041.7730.109610053.91756.3166
10057.39759.4406 10139.3817.402410155.15 831.90110185.47 849.92710215.49876.6191
10228.38880.280810235.75884.114310263.68910.434110277.64919.138210294.59  922.04
#Mann= 3 , 0 , 0
9661.495  0.0992       09661.495  0.0992       010294.59  0.0992       0
#XS Ineff= 2 , 0
       0                               0
Bank Sta=9661.495,10294.59
Exp/Cntr=0.3,0.1

Type RM Length L Ch R = 1 ,27222.74,293.469700,293.469700,293.469700
XS GIS Cut Line= 6
503969.056945061806379.322646579504115.775789438806566.490123091
 504143.43834052806618.178490669504159.884143442806685.296651235
504183.718023563806733.645333665504309.246792303806914.490899935
#Sta/Elev= 30
  9665.6848.63539672.906847.07939698.643832.80789706.818831.5651 9737.25821.6226
9775.856 800.0599788.725791.61629802.146 778.5669818.034 769.0779851.199734.3064
9864.535727.88269868.189724.43149885.179719.16799936.544 720.417 9962.18723.6782
9981.821719.476310000.27718.481310041.96720.327210052.81  724.2210087.71730.7118
10111.02740.426210141.97765.322610159.02770.156510220.17780.181110244.75785.9583
10257.04797.826510263.84798.986210281.61807.871410298.25812.813910305.56819.0919
#Mann= 3 , 0 , 0
  9665.6  0.0678       0  9665.6  0.0678       010305.56  0.0678       0
#XS Ineff= 2 , 0
       0                               0
Bank Sta=9665.6,10305.56
Exp/Cntr=0.3,0.1

Type RM Length L Ch R = 1 ,26929.27,365.250400,365.250400,365.250400
XS GIS Cut Line= 6
503769.211488273806585.792032701503773.051412361806593.149225047
503804.337385004806646.253190492503905.616379845806802.513757702
504026.983184217806989.758762874504028.775216179806992.640879301
#Sta/Elev= 30
9732.581 848.3619743.028843.65949766.241827.6232 9801.06801.49449824.855791.0368
9848.689776.96499872.522765.90439908.272740.43659920.189732.87269932.435726.8279
9955.939720.42059967.856716.45899979.773714.66659987.593  714.5210027.44715.0865
10039.36719.065410063.19722.858910075.11721.590810087.03721.8946 10097.9727.4656
10098.94728.080510110.86743.168210122.78752.398710146.61778.717110158.53789.6978
10170.44803.138510182.36815.643910194.28824.983910206.19832.737110215.26832.9164
#Mann= 3 , 0 , 0
9732.581  0.0649       09732.581  0.0649       010215.26  0.0649       0
#XS Ineff= 2 , 0
       0                               0
Bank Sta=9732.581,10215.26
Exp/Cntr=0.3,0.1