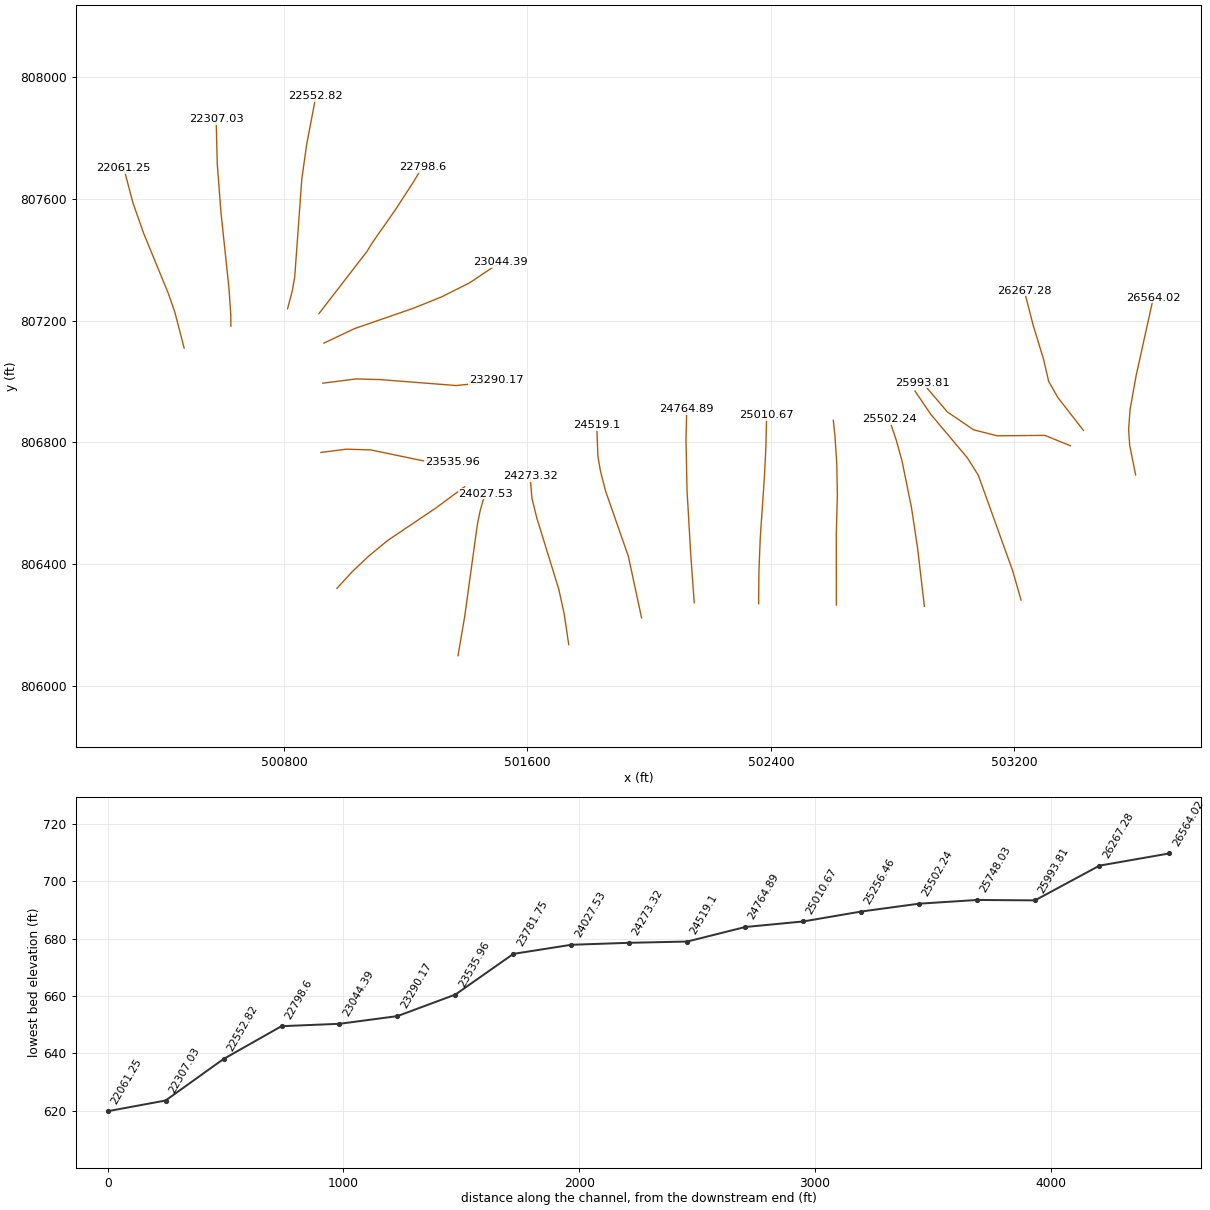
HEC-RAS study 5238_ras.prj: 5238

--- 5238_ras.g01 (geometry) --- (continued)

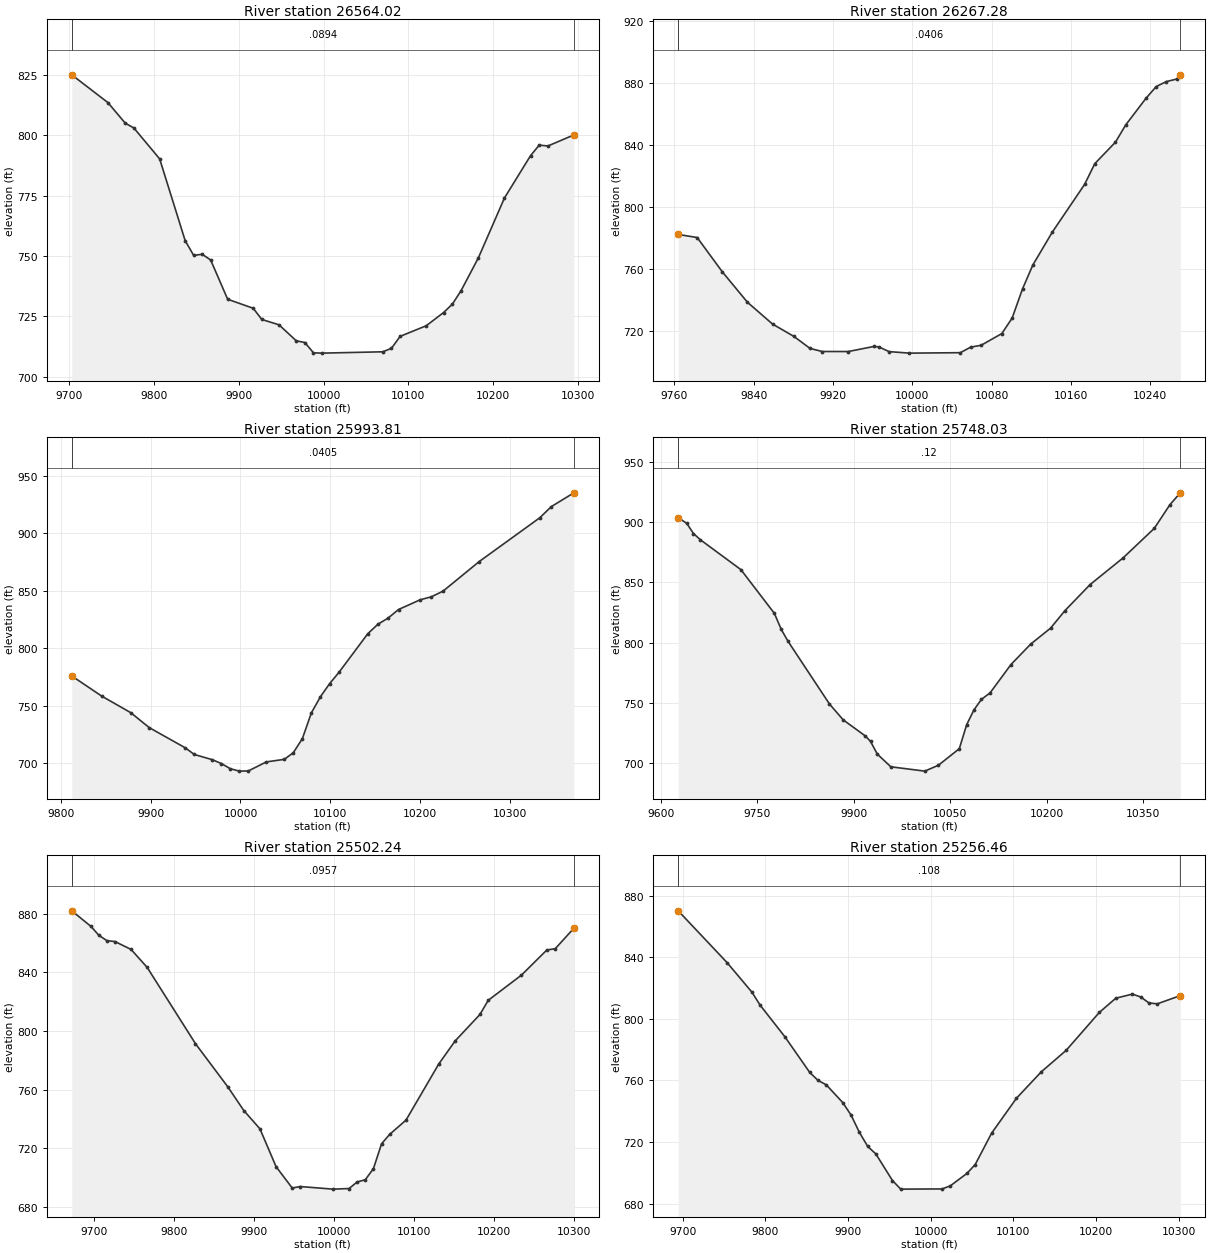
Type RM Length L Ch R = 1 ,26564.02,296.740400,296.740400,296.740400
XS GIS Cut Line= 6
 503598.20123584 806693.40517075503578.689811547806790.689660177
503575.207216162806841.482342123  503579.9386844806908.288324739
503600.068782397807020.498927834 503656.30245477807274.911009377
#Sta/Elev= 30
9703.234 824.9979745.877813.48819766.306804.96179776.446802.97839806.815 790.193
9836.885756.33249846.909750.21889856.925750.68499866.929748.32669886.968732.0561
9917.116728.31859927.232723.69049947.528721.46649967.823714.84829977.971714.1402
9988.119709.86979998.267709.746310069.78710.297510080.02711.732310090.27716.6978
   10121721.078310141.49726.570910151.74730.000410161.98735.552110182.47749.2025
10213.21 774.00110243.94791.511110254.19795.886610264.43795.531610294.99800.1067
#Mann= 3 , 0 , 0
9703.234  0.0894       09703.234  0.0894       010294.99  0.0894       0
#XS Ineff= 2 , 0
       0                               0
Bank Sta=9703.234,10294.99
Exp/Cntr=0.3,0.1

Type RM Length L Ch R = 1 ,26267.28,273.467200,273.467200,273.467200
XS GIS Cut Line= 6
503426.627910967806839.787801099503343.539672384806946.634730026
 503312.61290297807000.287545261503295.562427968807073.831069781
503261.632413704807184.783451176503232.398172585807298.671850698
#Sta/Elev= 30
9763.794782.15119782.906780.16549808.278757.99839833.649738.3266 9859.02724.2357
9880.525716.27269896.777708.52719909.099706.5244 9935.36706.51239961.183709.7838
 9966.12709.52619976.597706.44979997.033705.479210048.44705.766910058.89709.3593
10069.35710.527710090.27718.091310100.72728.109410111.18746.985310121.64762.4745
10141.27783.682310173.77814.427210184.15827.931510204.92841.7386 10215.3852.9041
10235.86870.183610246.12877.716110256.38  880.9310266.63882.5197 10270.4885.2779
#Mann= 3 , 0 , 0
9763.794  0.0406       09763.794  0.0406       0 10270.4  0.0406       0
#XS Ineff= 2 , 0
       0                               0
Bank Sta=9763.794,10270.4
Exp/Cntr=0.3,0.1

Type RM Length L Ch R = 1 ,25993.81,245.785500,245.785500,245.785500
XS GIS Cut Line= 6
503383.875784641806789.134133328503299.993225742806823.206102318
503143.435725985806821.711455931503065.784310982806841.539595632
502979.437306479806900.397922167502898.510374043806995.778340805
#Sta/Elev= 30
9812.183776.09869845.504758.59859877.807744.20189898.394731.21249938.574713.6019
9948.595707.85179968.632703.3057 9978.65699.98949988.669695.47679998.687693.3644
10008.71693.511710028.75 701.36510048.75703.601410058.75709.319510068.85721.5194
10078.96744.079110089.07 758.11410099.26769.442110109.66779.266410141.72812.8126
   10153 821.08110164.28826.368410175.91833.845410199.95842.297210212.51844.9206
 10225.5849.829310265.74875.541810333.29 913.67710345.95923.277610371.11935.2999
#Mann= 3 , 0 , 0
9812.183  0.0405       09812.183  0.0405       010371.11  0.0405       0
#XS Ineff= 2 , 0
       0                               0
Bank Sta=9812.183,10371.11
Exp/Cntr=0.3,0.1

Type RM Length L Ch R = 1 ,25748.03,245.785600,245.785600,245.785600
XS GIS Cut Line= 6
503221.818747481806282.139348008503194.299657478806378.128663335
503081.445539696806691.949667145503045.407635464806749.273759796
502925.327969205806892.213967204502873.422085482806968.745823919
#Sta/Elev= 30
9626.881903.55489640.116898.95359650.538890.51659660.961885.46679724.272860.5711
 9776.42824.24159787.015810.99639797.638801.06949861.754749.33229883.127736.0854
9917.606 722.699 9925.76718.17579936.302707.64029957.385697.090510010.11693.5015
10031.26698.360510063.81712.103310075.26732.011610086.71744.408110098.28753.0356
10111.67758.388710144.14 781.88910174.88798.877710205.62812.006810227.85826.4736
10267.11848.179410318.27870.230110366.96894.806110391.12 914.35310407.36924.2425
#Mann= 3 , 0 , 0
9626.881    0.12       09626.881    0.12       010407.36    0.12       0
#XS Ineff= 2 , 0
       0                               0
Bank Sta=9626.881,10407.36
Exp/Cntr=0.3,0.1

Type RM Length L Ch R = 1 ,25502.24,245.785500,245.785500,245.785500
XS GIS Cut Line= 6
502904.123201478806261.297228542502882.060688745 806451.20257693
502861.913169007806585.276807611 502830.90835133806738.041830739
502812.022057341806806.915597382502788.309650089806877.037561606
#Sta/Elev= 30
9672.217881.89789696.079871.34569706.147 865.2069716.214861.55439726.281860.9592
9746.416855.5746 9766.55843.33229826.954791.35859867.235762.06929887.432745.7982
9907.629733.30139927.826707.49239948.023 692.9579958.121693.97449998.719692.2079
10019.08692.602710029.27 697.09410039.45698.619810049.63706.227610059.81723.1502
   10070729.571110090.36739.244610131.29777.453110151.78793.190210182.85811.2528
10193.22820.900710234.84838.097510266.51855.188510277.07 856.09210300.33870.0129
#Mann= 3 , 0 , 0
9672.217  0.0957       09672.217  0.0957       010300.33  0.0957       0
#XS Ineff= 2 , 0
       0                               0
Bank Sta=9672.217,10300.33
Exp/Cntr=0.3,0.1

Type RM Length L Ch R = 1 ,25256.46,245.785500,245.785500,245.785500
XS GIS Cut Line= 6
502615.030231459 806265.88600585502614.704708056 806498.66635642
502618.259875936806626.216589921502616.521637626 806726.14982186
502610.459277337806819.903554419502604.981983887 806872.67021181
#Sta/Elev= 30
9694.549870.15579753.666836.51839783.667817.37619793.667808.88199823.669788.3039
 9853.67765.2087 9863.67760.0488 9873.67757.17999893.671745.58449903.671 737.479
9913.671 726.3339923.672717.27419933.675 712.2559953.683695.04919963.687689.4669
10013.71689.597510023.71691.595310043.72699.655710053.72 705.39510073.72725.8714
10103.73748.499810133.73765.628610163.76779.547510203.84804.144210223.88813.4315
10243.92816.092210253.96814.234910264.01810.326710274.07809.773610301.89815.1132
#Mann= 3 , 0 , 0
9694.549   0.108       09694.549   0.108       010301.89   0.108       0
#XS Ineff= 2 , 0
       0                               0
Bank Sta=9694.549,10301.89
Exp/Cntr=0.3,0.1

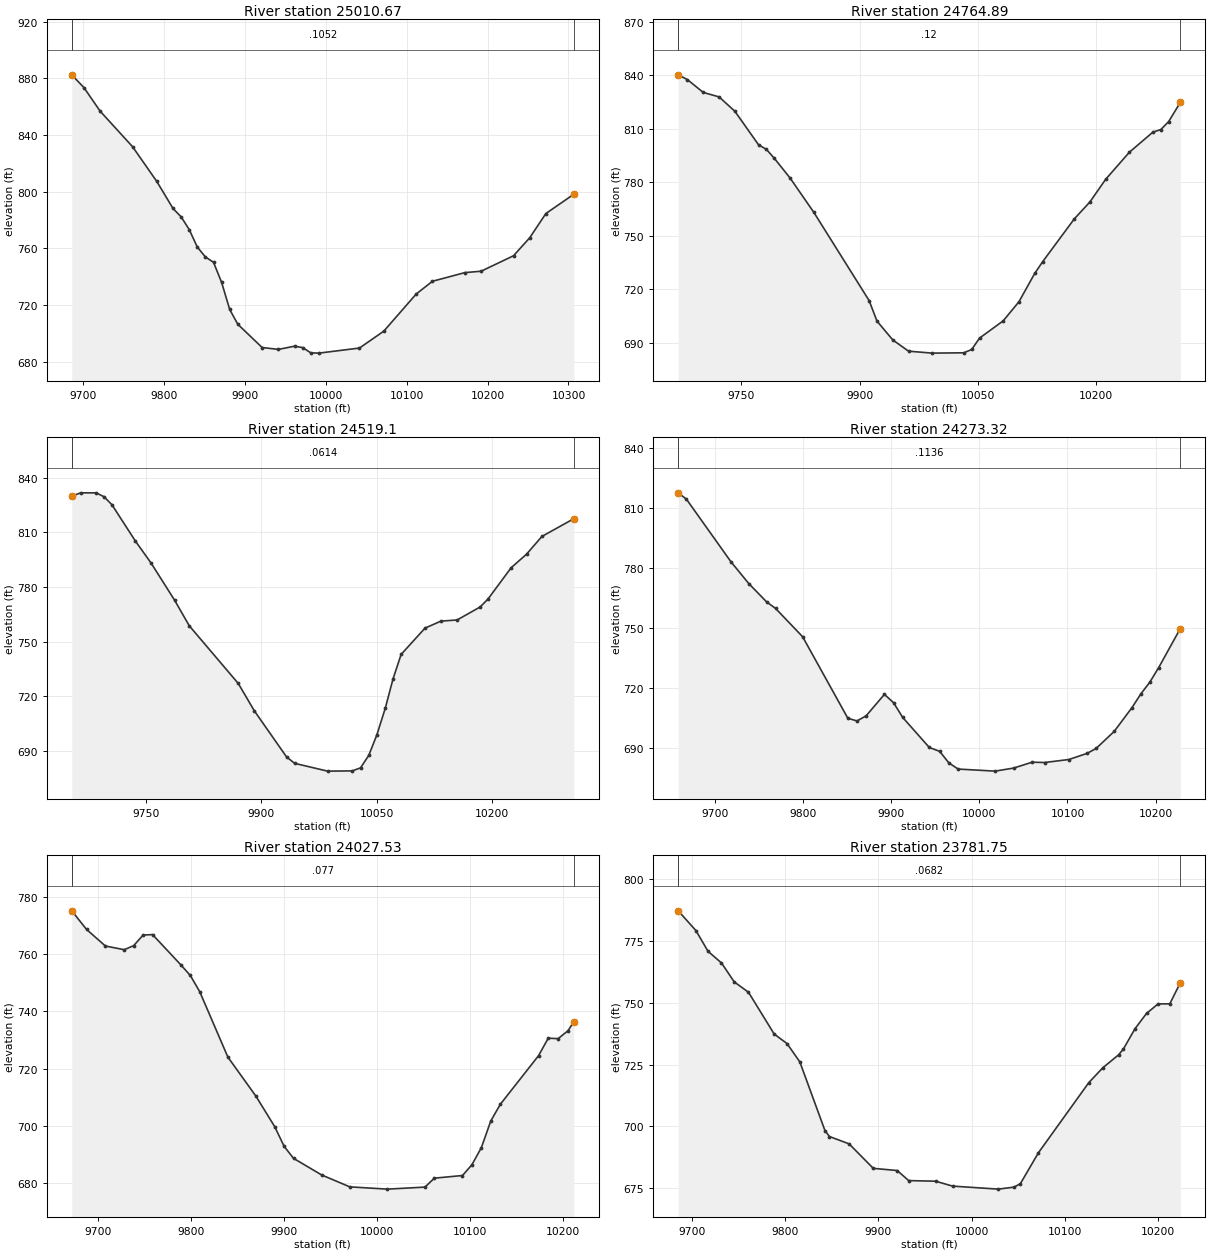
Type RM Length L Ch R = 1 ,25010.67,245.785600,245.785600,245.785600
XS GIS Cut Line= 6
502359.574461727 806269.94085936502360.596072415806378.762239792
502364.959472271806486.968828449502378.737241381806689.172113963
502383.599718977806788.775512179502385.660731028 806889.54107743
#Sta/Elev= 30
9686.321882.41319701.381873.38389721.382856.76259761.384831.71139791.385807.1591
9811.398788.08939821.407782.19899831.415773.23289841.423760.85449851.431753.8638
9861.439750.12519871.447735.91629881.455716.80139891.463706.36069921.513689.9749
9941.557688.63539961.601690.91399971.623689.90649981.646686.21039991.668686.0069
10041.79689.596210071.86  701.5310111.95727.772610131.97736.722110172.02742.8335
10192.04743.808410232.07754.720210252.07767.392610272.07784.532810306.62798.1541
#Mann= 3 , 0 , 0
9686.321  0.1052       09686.321  0.1052       010306.62  0.1052       0
#XS Ineff= 2 , 0
       0                               0
Bank Sta=9686.321,10306.62
Exp/Cntr=0.3,0.1

Type RM Length L Ch R = 1 ,24764.89,245.785500,245.785500,245.785500
XS GIS Cut Line= 6
502148.025125999806273.298785321502136.375745354 806433.32619727
502126.745225197806601.673938595502124.293663843806640.434643375
502120.968361802806808.389052182502123.263980818 806909.72544285
#Sta/Elev= 30
9669.926840.20089681.658837.48499701.711830.31679721.764827.81789741.817819.7555
9771.896800.92819781.923798.34959791.949793.33219812.002782.2306 9842.07763.0203
9912.184 713.5579922.201702.02279942.233691.47329962.266 685.1619992.315684.0653
10032.39 684.25510042.41686.111310052.41692.508810082.41702.182910102.42712.9123
10122.42728.801310132.42735.328610172.43759.271810192.43768.874510212.44781.5745
10242.45796.745610272.45808.063910282.46809.491710292.46814.004610307.19 824.727
#Mann= 3 , 0 , 0
9669.926    0.12       09669.926    0.12       010307.19    0.12       0
#XS Ineff= 2 , 0
       0                               0
Bank Sta=9669.926,10307.19
Exp/Cntr=0.3,0.1

Type RM Length L Ch R = 1 , 24519.1,245.785500,245.785500,245.785500
XS GIS Cut Line= 6
501975.005716125806223.459663889501931.600085984 806425.68340165
501856.545729066806640.619005443501839.923133662806705.532036505
501831.337663839806755.732738044501827.816601713 806856.48987396
#Sta/Elev= 30
9653.144829.87829664.821831.67659685.059831.64519695.223829.51199705.427825.1417
9736.041805.1763 9756.45793.11229787.138772.68999806.083 758.7529869.866727.1088
9890.828712.06889932.752686.80039943.309683.26969986.136679.001710018.32679.1267
10029.06680.801510039.76687.607710050.31698.892710061.19713.377710071.39729.6228
10081.94743.050410113.03757.465410133.68761.282610154.87761.939610184.77769.0572
10194.91773.361210225.12790.572610245.17798.021910265.22807.758710306.76 817.493
#Mann= 3 , 0 , 0
9653.144  0.0614       09653.144  0.0614       010306.76  0.0614       0
#XS Ineff= 2 , 0
       0                               0
Bank Sta=9653.144,10306.76
Exp/Cntr=0.3,0.1

Type RM Length L Ch R = 1 ,24273.32,245.785600,245.785600,245.785600
XS GIS Cut Line= 6
 501735.64276861806135.772247449501720.657637803806236.781284427
501702.799558221806318.313324031501630.770060866806551.660295561
 501614.73764192806616.711186175501608.507616836806689.555034959
#Sta/Elev= 30
9658.037817.55159667.331814.38499717.903783.10859738.131772.2371 9758.36763.0941
9768.575759.81479799.286745.67029850.576704.99089860.968703.61539871.361 706.168
9892.147716.9032 9902.54712.70699912.933705.36869943.097690.37429954.853688.4418
9965.358682.65099975.863  679.5910017.88678.561310038.88680.091610059.88683.0291
10073.99682.861810101.61684.367710122.21687.410110132.51 689.895 10153.1698.4278
 10173.3710.331310183.38717.176310193.45722.969610203.53730.2508 10228.1749.7896
#Mann= 3 , 0 , 0
9658.037  0.1136       09658.037  0.1136       0 10228.1  0.1136       0
#XS Ineff= 2 , 0
       09910.047                       0
Bank Sta=9658.037,10228.1
Exp/Cntr=0.3,0.1

Type RM Length L Ch R = 1 ,24027.53,245.785500,245.785500,245.785500
XS GIS Cut Line= 6
501371.759422563 806099.36474081501393.695450829806227.100766818
501435.155703107806528.604588398501444.790691238806576.415864627
501453.615694375806607.501058166501462.422199947806630.834426195
#Sta/Elev= 30
9672.163775.11939688.027768.62519708.319762.83099728.612761.53269738.759762.9624
9748.905766.65549759.051766.8133 9789.49756.23579799.637752.53729809.743 746.892
9840.027724.02349870.312710.31269890.502 699.6549900.597692.79329910.692688.6241
9940.977682.81069971.262678.657210011.64677.872810052.01678.5775 10062.1681.7011
10092.38682.632310102.47686.376110112.63692.335810122.83701.699410133.04 707.507
 10174.2724.5179 10184.6730.618510195.21730.4515 10205.9733.231810212.14736.4076
#Mann= 3 , 0 , 0
9672.163   0.077       09672.163   0.077       010212.14   0.077       0
#XS Ineff= 2 , 0
       0                               0
Bank Sta=9672.163,10212.14
Exp/Cntr=0.3,0.1

Type RM Length L Ch R = 1 ,23781.75,245.785500,245.785500,245.785500
XS GIS Cut Line= 6
500973.971350005806320.673753515501026.925848626806378.030857579
501078.024735545806426.162144074501141.026171517806478.104245345
501299.148683939806584.577608821501393.796536982806654.652997667
#Sta/Elev= 30
9685.481787.11949704.497779.12619717.415770.7759 9731.87766.06369745.519758.4151
9760.781754.24479788.394737.34269802.132733.5027 9815.87   726.19842.803698.3604
9847.656695.94339868.724692.98019894.645683.0839 9920.31682.20899932.626678.1439
9961.489677.89749979.637675.918710028.61674.695810045.58675.500810052.41676.9109
10071.72689.375810125.74717.708310140.74723.7084 10157.7728.944510162.88731.3145
10175.27739.472110187.65745.673210200.03749.509910212.63749.552910223.89 758.077
#Mann= 3 , 0 , 0
9685.481  0.0682       09685.481  0.0682       010223.89  0.0682       0
#XS Ineff= 2 , 0
       0                               0
Bank Sta=9685.481,10223.89
Exp/Cntr=0.3,0.1

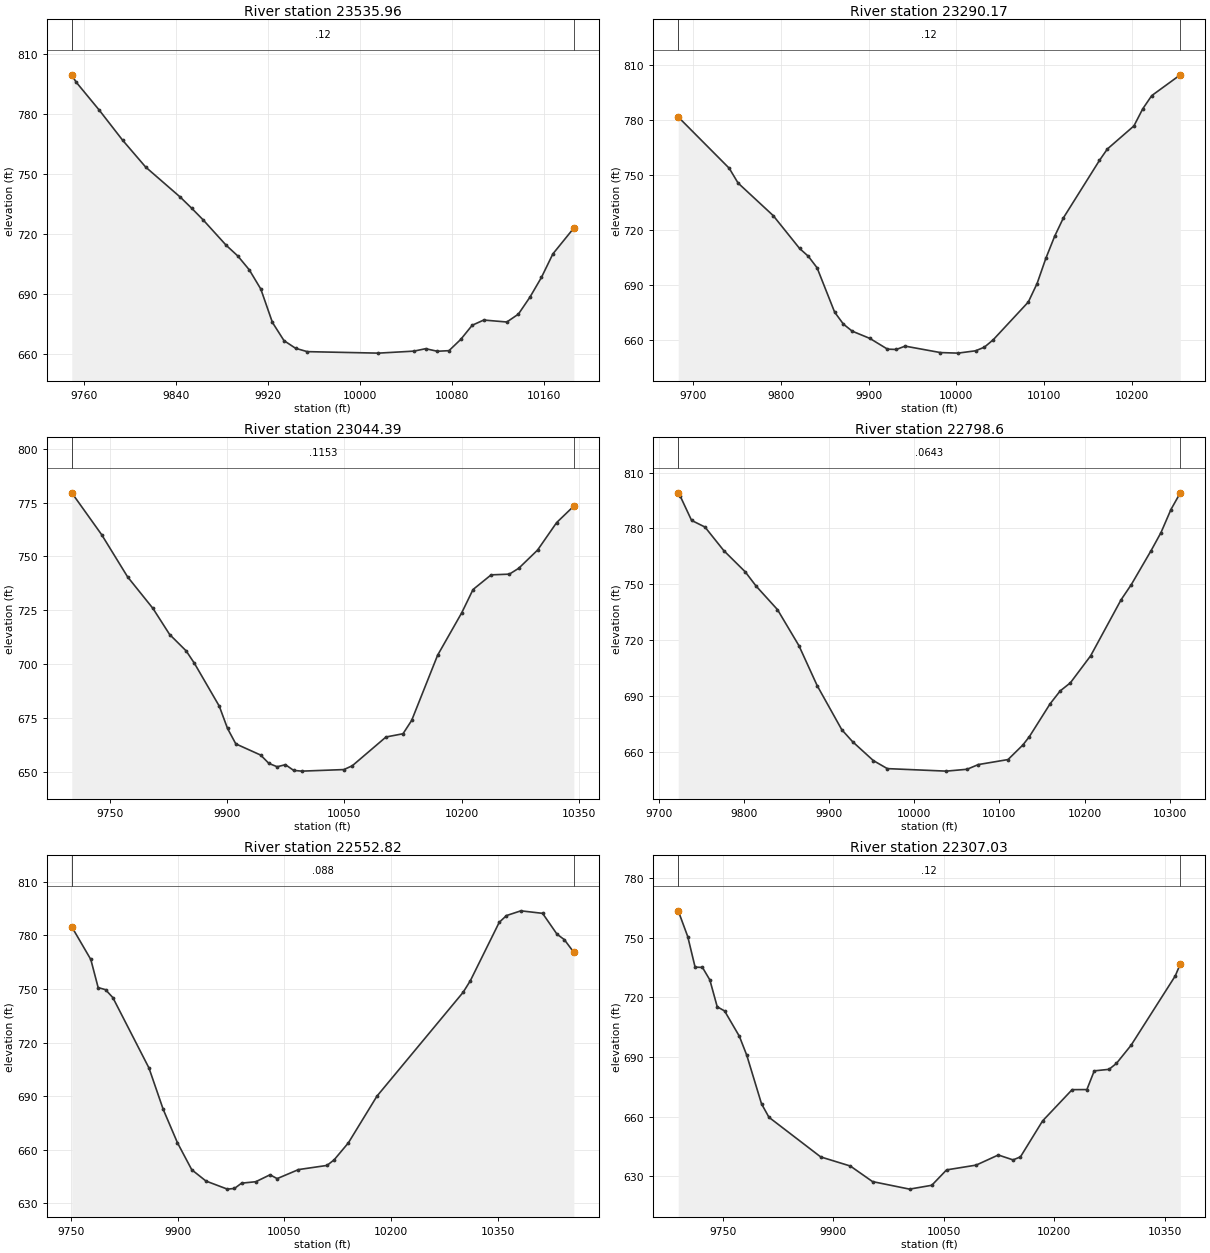
Type RM Length L Ch R = 1 ,23535.96,245.785600,245.785600,245.785600
XS GIS Cut Line= 6
 500921.43911907 806767.10150543501004.628850666806777.852996996
501085.023152498806775.426612726501255.060652154806740.097583063
501307.853700538806735.262546472501353.224331107806736.289701589
#Sta/Elev= 30
9749.481799.79919753.109796.28049773.488782.06249793.651767.1228 9813.74753.6459
9843.827738.61619853.827733.01729863.827 727.1649883.848714.46549893.871709.1628
9903.893702.20449913.915692.59449924.014675.88899934.112666.75659944.211662.9252
9954.309661.252710016.27660.508410047.13661.510110057.29 662.72410067.46 661.446
10077.62661.737610087.85667.377910097.83674.463610107.87 677.06710127.95676.0862
10137.99680.025810148.01688.490710158.01698.360810168.01710.183410186.24723.1269
#Mann= 3 , 0 , 0
9749.481    0.12       09749.481    0.12       010186.24    0.12       0
#XS Ineff= 2 , 0
       0                               0
Bank Sta=9749.481,10186.24
Exp/Cntr=0.3,0.1

Type RM Length L Ch R = 1 ,23290.17,245.785500,245.785500,245.785500
XS GIS Cut Line= 6
 500927.72838224806994.772833172501037.918505423 807008.69571084
501115.506988813 807006.47698653501365.778144461806986.974615549
501459.326658023 806996.43437027501496.590974968807005.932057268
#Sta/Elev= 30
9682.941 781.4639741.097753.57019751.206745.51669791.278727.80589821.295709.9659
9831.299705.69159841.303699.41059861.311675.29869871.315668.77489881.369 664.941
9901.483660.99839921.597655.16129931.654654.97539941.711 656.7999981.939653.2949
10002.03652.989910022.08 654.25910032.11656.234510042.14660.225710082.22680.8025
10092.22690.854610102.23704.579210112.23716.536610122.23726.572210163.39757.8679
10172.37764.039910202.66776.597210212.76785.923610222.98793.088110255.58804.4005
#Mann= 3 , 0 , 0
9682.941    0.12       09682.941    0.12       010255.58    0.12       0
#XS Ineff= 2 , 0
       0                               0
Bank Sta=9682.941,10255.58
Exp/Cntr=0.3,0.1

Type RM Length L Ch R = 1 ,23044.39,245.785500,245.785500,245.785500
XS GIS Cut Line= 6
500931.364355189807126.395054282501032.047530314807174.017572448
501226.143653344807241.187941105 501318.46520199807278.483758393
501409.131003687807323.977760044501512.429525696807392.845225225
#Sta/Elev= 30
  9701.3779.49729739.466760.09929772.696740.49369805.172725.81869826.497713.7295
9847.654706.11159858.232700.32179889.967680.47069900.545 670.1049911.124662.9541
9942.858657.76749953.437653.89239964.015652.33169974.593653.29649985.171650.6282
 9995.75 650.30410049.31651.024710060.09652.789110103.23666.150910124.98 667.657
10136.04673.831710169.24704.110910200.11723.820210214.55734.605510237.71741.4188
10261.01741.7466   10273744.4672 10297.1752.923810321.48765.6778 10343.5773.3664
#Mann= 3 , 0 , 0
  9701.3  0.1153       0  9701.3  0.1153       0 10343.5  0.1153       0
#XS Ineff= 2 , 0
       0                               0
Bank Sta=9701.3,10343.5
Exp/Cntr=0.3,0.1

Type RM Length L Ch R = 1 , 22798.6,245.785600,245.785600,245.785600
XS GIS Cut Line= 6
500914.945446149807223.219179921501072.110139096 807426.77949219
501092.157588083807458.833778959501167.462775851807566.491922484
501224.738705569807654.807996654501254.430328157807704.443991136
#Sta/Elev= 30
9722.926798.76269725.249797.32179738.582784.26559754.325780.68729776.507 767.972
9801.679756.56739814.265749.00319839.437736.3083 9864.61716.94719886.072695.4295
9914.954671.7432 9927.54665.35029951.946655.17039968.414650.824910037.67649.4753
10062.08650.475210075.24653.003110110.14655.691710127.58663.5326 10135.3668.0857
10159.47685.616710171.39   692.610183.31696.922310207.14711.4617 10242.9741.6029
10254.81749.694110278.12768.013210289.77777.739710301.42790.107210312.43 799.079
#Mann= 3 , 0 , 0
9722.926  0.0643       09722.926  0.0643       010312.43  0.0643       0
#XS Ineff= 2 , 0
       0                               0
Bank Sta=9722.926,10312.43
Exp/Cntr=0.3,0.1

Type RM Length L Ch R = 1 ,22552.82,245.785500,245.785500,245.785500
XS GIS Cut Line= 6
500811.794464993807239.078869535 500827.53155841807299.134359189
500835.406044279807344.761372333500858.576663211807664.642238345
500874.455751454807778.499073244500904.982476001 807938.13724227
#Sta/Elev= 30
9750.722784.73839777.526766.46839787.862750.74529798.198  749.599808.533745.1576
9859.348 705.8099879.443682.62059899.537663.91519919.632648.85969939.682642.5412
9969.717638.03359979.728638.4164 9989.74641.370510009.76642.178410029.79 646.052
10039.81643.912710069.85648.964110109.96651.2916   10120654.404410140.09 663.932
10180.27690.034910301.48748.070210311.65754.536710352.35787.227410362.53791.0255
10382.88 793.682 10413.4792.278110433.75   780.610443.93777.600510457.41770.4659
#Mann= 3 , 0 , 0
9750.722   0.088       09750.722   0.088       010457.41   0.088       0
#XS Ineff= 2 , 0
       0                               0
Bank Sta=9750.722,10457.41
Exp/Cntr=0.3,0.1

Type RM Length L Ch R = 1 ,22307.03,245.785500,245.785500,245.785500
XS GIS Cut Line= 6
500625.642487679 807182.09434406500625.351015455807218.886694331
500619.414511379807305.095600141 500593.01145593807556.097907563
500580.768073826807716.390849432500577.127493305 807861.83666856
#Sta/Elev= 30
9689.586763.41059702.492750.47399712.492735.11889722.493734.97039732.507728.6902
9742.531715.19329752.555 713.0899772.602 700.3699782.626690.86039802.673 666.444
9812.792659.65749883.076639.73529923.293635.15789953.455627.334710003.74623.5483
10033.91625.484410054.02633.216110094.17635.617410124.26640.703910144.32638.2399
10154.34639.763510184.43657.841110224.55673.543110244.56673.581910254.57682.9831
10274.58683.747910284.58686.684610304.59695.847610364.61730.713910371.45736.7368
#Mann= 3 , 0 , 0
9689.586    0.12       09689.586    0.12       010371.45    0.12       0
#XS Ineff= 2 , 0
       0                               0
Bank Sta=9689.586,10371.45
Exp/Cntr=0.3,0.1

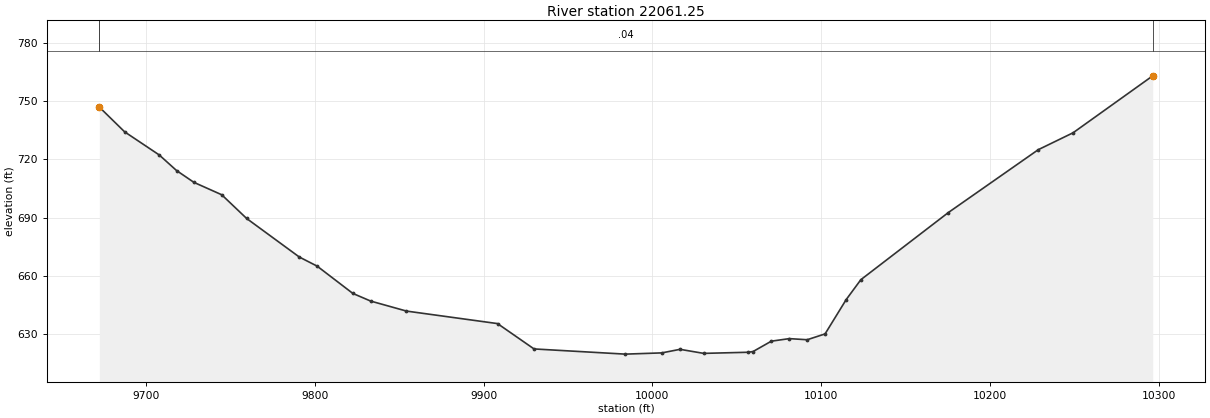
Type RM Length L Ch R = 1 ,22061.25,245.785600,245.785600,245.785600
XS GIS Cut Line= 6
500471.978710504807110.384581403500441.360734118807228.139643761
500420.090307242807289.482477649500339.048652939807486.747344643
500303.708790334807587.538054983500273.777894777807700.835587152
#Sta/Elev= 30
9672.458746.80669687.438734.09399707.938722.19939718.188714.1948 9728.47708.1182
9744.944701.74179759.692689.56149790.914669.71939801.442665.0569 9822.61651.0103
9833.194647.07169854.363641.93849908.309635.50229929.928622.47069983.976619.8032
10005.61620.439610016.42622.269710030.42620.187610056.72620.765110059.67621.1391
10070.48626.460110081.12627.774310091.71627.197110102.31630.202310114.83647.8614
 10123.5 658.07310175.27  692.5610228.59 724.91610249.23733.616910296.39762.8871
#Mann= 3 , 0 , 0
9672.458    0.04       09672.458    0.04       010296.39    0.04       0
#XS Ineff= 2 , 0
       0                               0
Bank Sta=9672.458,10296.39
Exp/Cntr=0.3,0.1