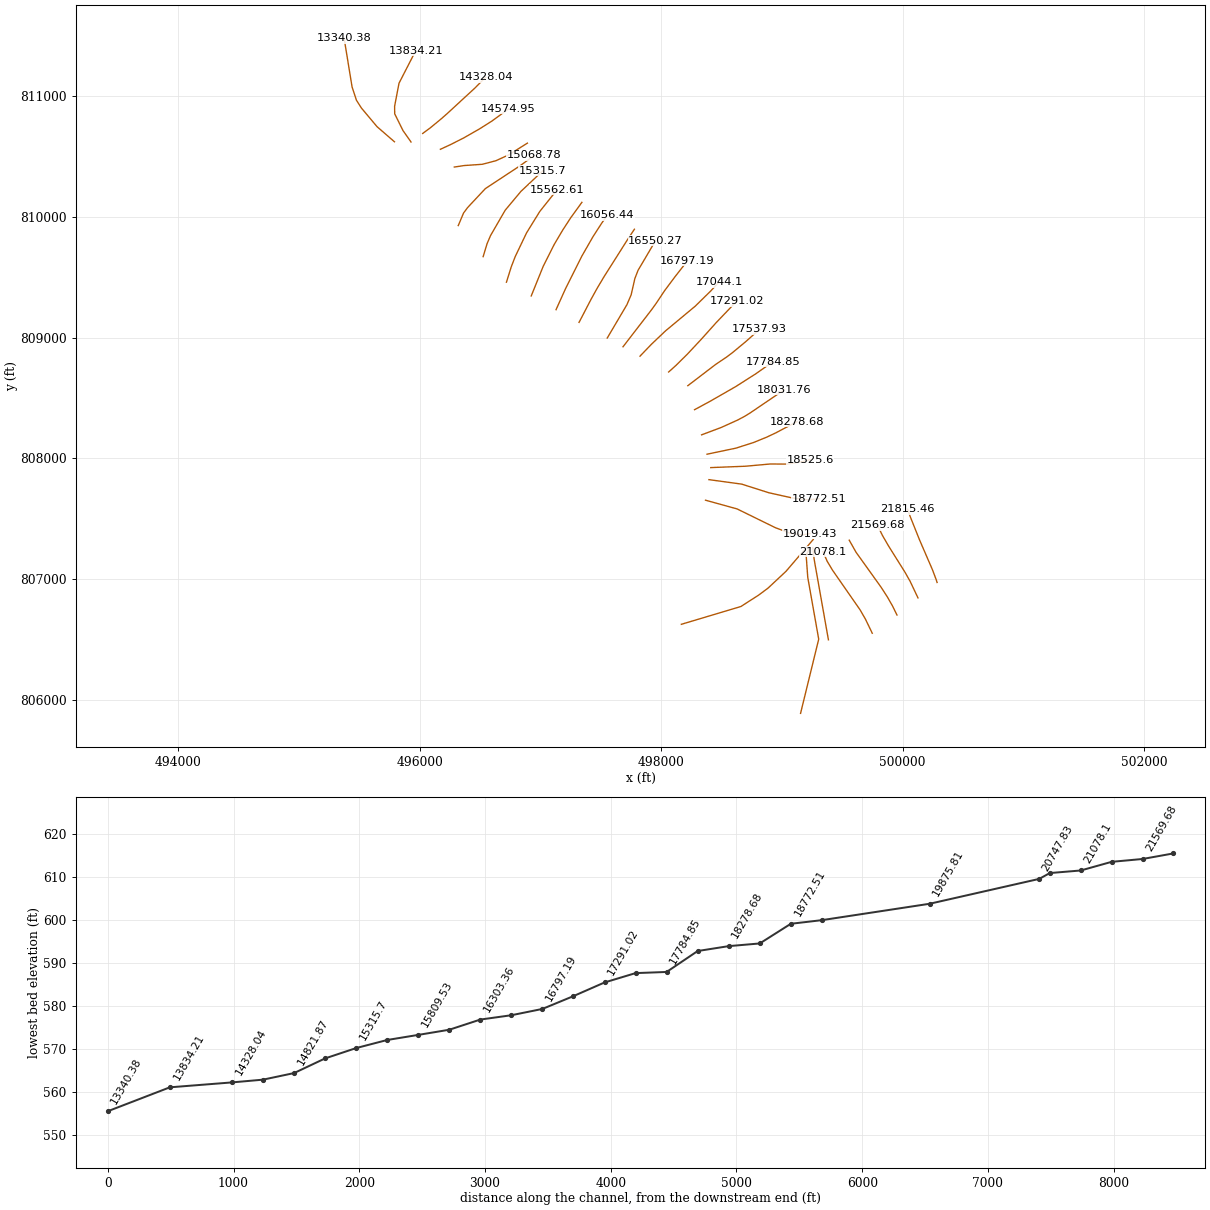
HEC-RAS study 5238_ras.prj: 5238

--- 5238_ras.g01 (geometry) --- (continued)

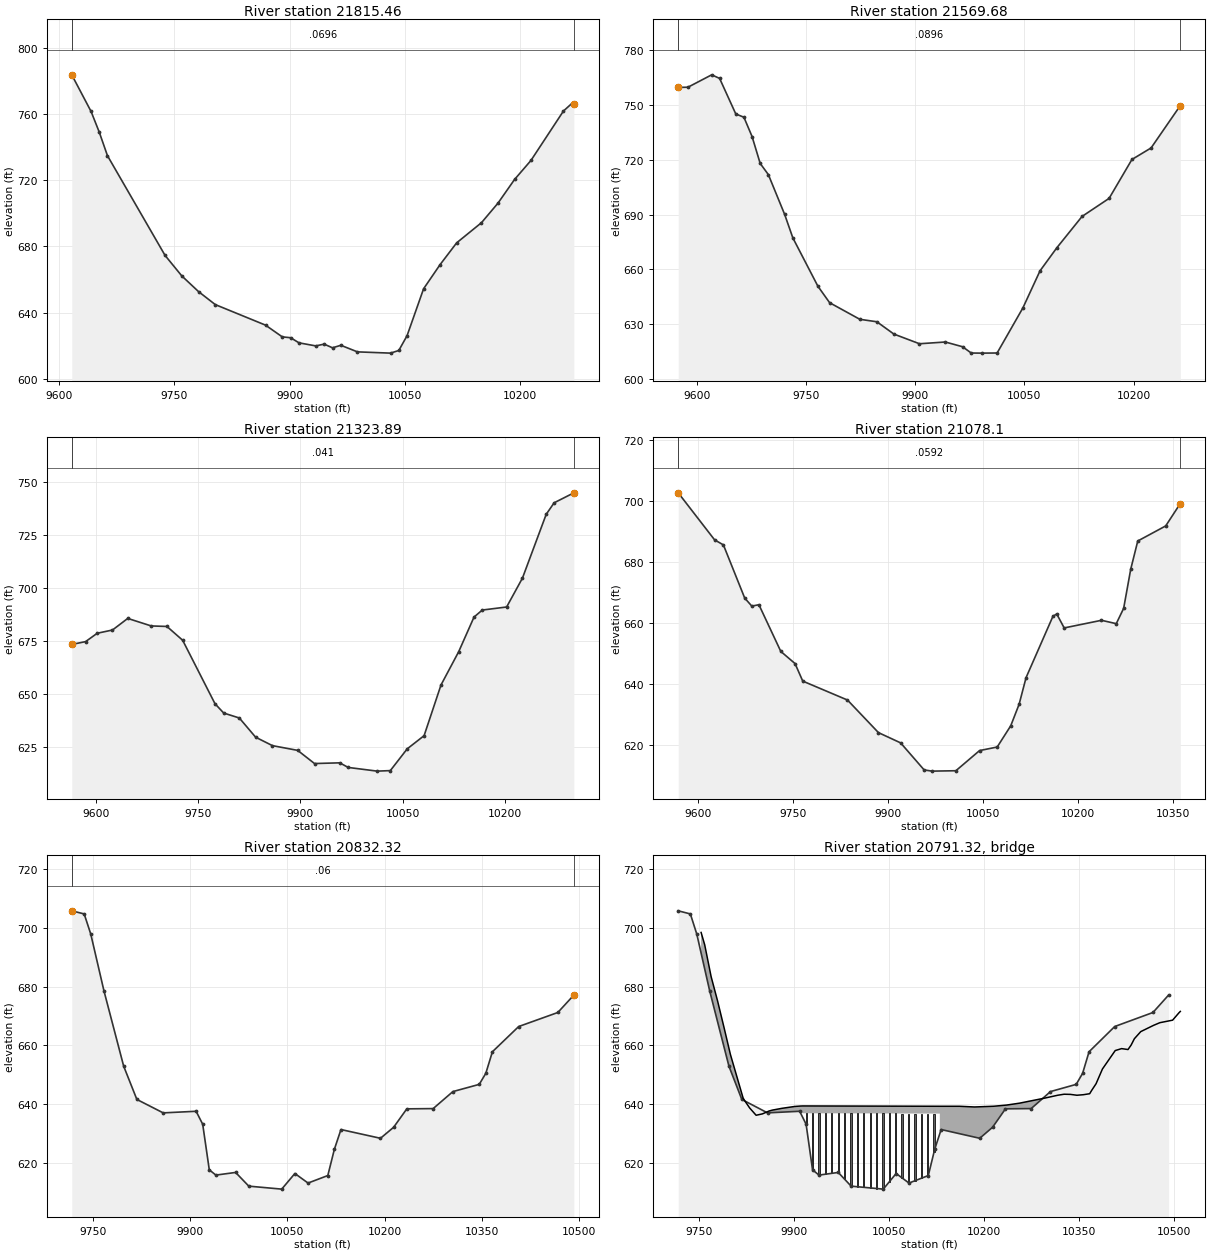
Type RM Length L Ch R = 1 ,21815.46,245.785500,245.785500,245.785500
XS GIS Cut Line= 6
500285.639148913806971.068297131500279.826110532806990.099167656
500248.082516102807074.564462923500139.901876935807324.806166333
500063.664652859807515.444372143500041.865127634807577.749199421
#Sta/Elev= 30
9616.236783.82389641.371761.67179652.053749.14479662.736734.90129737.752 674.602
9759.568662.18989781.385652.69889803.201644.83999868.651632.41399890.467625.3155
9901.375624.79619912.284621.7014  9934.1619.85489945.008  620.929955.917618.7052
9966.782620.2247  9988.4616.244310031.52615.481110042.29617.084810053.06626.0402
 10074.6654.433310096.14669.062110117.68682.200910149.99 694.37810171.53706.2229
10193.07720.516310214.44732.019310256.82761.946510267.41766.363510270.33765.8759
#Mann= 3 , 0 , 0
9616.236  0.0696       09616.236  0.0696       010270.33  0.0696       0
#XS Ineff= 2 , 0
       0                               0
Bank Sta=9616.236,10270.33
Exp/Cntr=0.3,0.1

Type RM Length L Ch R = 1 ,21569.68,245.785500,245.785500,245.785500
XS GIS Cut Line= 6
500127.649249099806842.775746895500062.366249971806980.600943599
500019.892899608807055.791898793499885.603951826807269.993478235
499833.880351394807359.097338505499791.598501185807444.921604782
#Sta/Elev= 30
9573.896759.52299587.216759.61369619.903766.39689630.799764.43679653.036745.0039
9664.229 743.1939675.422732.65529686.615717.92459697.807711.84269720.193690.1039
9731.514677.2164 9765.97650.76929782.104641.7578 9823.61632.68889847.047631.3348
9870.483624.60219905.665 619.3149941.243620.26649964.962617.67219976.822614.2375
 9992.08614.184410012.45614.258410047.92638.948310071.44659.192110094.56671.8069
10129.25688.951610166.45698.829310197.82720.093410224.18726.410710264.37749.5874
#Mann= 3 , 0 , 0
9573.896  0.0896       09573.896  0.0896       010264.37  0.0896       0
#XS Ineff= 2 , 0
       0                               0
Bank Sta=9573.896,10264.37
Exp/Cntr=0.3,0.1

Type RM Length L Ch R = 1 ,21323.89,245.785600,245.785600,245.785600
XS GIS Cut Line= 6
499953.479053497806701.344309844499915.305031569806778.749314917
499874.008950302806850.959593445499820.868510655806933.056507949
499613.902780152807221.968054877499558.179608904807321.035849677
#Sta/Elev= 30
9564.492673.27119584.755674.60739601.833678.55119624.223680.08159646.613685.5499
9681.051682.0013 9704.09681.7584 9727.13675.25739774.544645.3319 9787.38640.9112
9810.281638.58459834.188629.51989858.878625.54249895.882 623.3079920.559617.0982
9957.576617.43579969.915615.264410012.41613.522410031.75613.766710056.53624.0278
10081.31630.250110106.11654.1675 10132.1669.887110154.54686.189510166.66689.4991
10202.35690.934810225.58704.570110260.42734.659210272.04740.080610300.96744.7855
#Mann= 3 , 0 , 0
9564.492   0.041       09564.492   0.041       010300.96   0.041       0
#XS Ineff= 2 , 0
       0                               0
Bank Sta=9564.492,10300.96
Exp/Cntr=0.3,0.1

Type RM Length L Ch R = 1 , 21078.1,245.785500,245.785500,245.785500
XS GIS Cut Line= 6
499748.786192021806550.368413796499691.401664492806668.865557768
499647.315281956806745.080262901499420.114840429807071.902974945
499375.707189363807146.021505698499339.916392184807226.598933162
#Sta/Elev= 30
9569.274702.59219626.663687.20239640.588685.54679674.222668.14159685.433665.5182
9696.644665.9722 9731.17 650.6989753.706646.70199765.827640.97529836.466634.7756
9885.332624.11559920.355620.75539957.486611.89939970.008611.512510007.57611.6412
10044.97 618.23910072.79619.401910094.19626.357110107.41633.407610118.38 642.121
10160.74662.161910166.76662.957610178.52658.376310237.44660.872410260.76659.7753
10272.42664.786110283.58677.589410294.69686.8276 10338.8691.759110361.86699.0976
#Mann= 3 , 0 , 0
9569.274  0.0592       09569.274  0.0592       010361.86  0.0592       0
#XS Ineff= 2 , 0
       0                               0
Bank Sta=9569.274,10361.86
Exp/Cntr=0.3,0.1

Type RM Length L Ch R = 1 ,20832.32,84.486500,84.486500,84.486500
XS GIS Cut Line= 3
499385.594622459806496.142335179499266.891436726807165.807477206
499256.474770039807259.557477206
#Sta/Elev= 30
9717.413705.87689736.565704.8154 9746.72697.94469767.032678.5919  9797.5652.8494
9817.812641.51969858.435636.93339909.215637.47889919.371  633.069929.526617.5063
9939.682615.7035 9970.15616.60969990.462611.933510041.24 610.91610061.55616.2452
10081.86612.989510112.33615.547110122.49624.529910132.64631.248810193.58628.2639
10213.89632.0263 10234.2638.308710274.83638.395410305.29644.200110345.92646.6605
10356.07650.437510366.23657.787210406.77666.400310467.14671.186110491.84677.1326
#Mann= 3 , 0 , 0
9717.413    0.06       09717.413    0.06       010491.84    0.06       0
#XS Ineff= 2 , 0
       09910.808        10147.35       0
Bank Sta=9717.413,10491.84
Exp/Cntr=0.3,0.1

Type RM Length L Ch R = 3 ,20791.32,,,
BEGIN DESCRIPTION:
END DESCRIPTION:
Bridge Culvert--1,0,-1,-1, 0
Deck Dist Width WeirC Skew NumUp NumDn MinLoCord MaxHiCord MaxSubmerge Is_Ogee
23.214400,38.057700,2.6,0, 45, 46, , , 0.95, 0, 0,0,,
 9753.53 9759.22 9769.37 9779.51 9789.66 9799.81 9820.10 9830.25 9840.39 9850.54
 9860.69 9866.07 9880.98 9901.27 9910.41 9910.41 9914.1810130.5610130.5610161.32
10185.3810215.8210236.0410256.2110296.5710316.7510326.8410336.9310347.0210357.11
10367.2010370.2810377.2910387.3710407.5510417.6410427.7310432.6110437.8110447.87
10468.0010478.0610498.1810508.2510510.35
  698.50  694.28  683.41  675.15  666.13  656.87  641.82  638.60  636.12  636.60
  637.56  637.88  638.48  639.12  639.27  639.27  639.30  639.19  639.19  639.19
  638.95  639.20  639.60  640.24  641.99  642.95  643.30  643.24  642.95  643.13
  643.47  644.58  646.88  651.91  658.20  658.86  658.55  660.05  662.24  664.66
  666.79  667.71  668.57  671.09  671.55
 -301.50 -305.72 -316.59 -324.85 -333.87 -343.13 -358.18 -361.40 -363.88 -363.40
 -362.44 -362.12 -361.52 -360.88 -360.73  636.77  636.80  636.69 -360.81 -360.81
 -361.05 -360.80 -360.40 -359.76 -358.01 -357.05 -356.70 -356.76 -357.05 -356.87
 -356.53 -355.42 -353.12 -348.09 -341.80 -341.14 -341.45 -339.95 -337.76 -335.34
 -333.21 -332.29 -331.43 -328.91 -328.45
 9753.53 9759.22 9769.37 9779.51 9789.66 9799.81 9820.10 9830.25 9840.39 9850.54
 9860.69 9866.07 9880.98 9901.27 9911.42 9933.24 9933.2410153.3810153.3810165.08
10175.2310185.3810215.8210236.0410256.2110296.5710316.7510326.8410336.9310347.02
10357.1110367.2010370.2810377.2910387.3710407.5510417.6410427.7310432.6110437.81
10447.8710468.0010478.0610498.1810508.2510510.35
  698.50  694.28  683.41  675.15  666.13  656.87  641.82  638.60  636.12  636.60
  637.56  637.88  638.48  639.12  639.29  639.29  639.29  639.18  639.18  639.17
  639.01  638.95  639.20  639.60  640.24  641.99  642.95  643.30  643.24  642.95
  643.13  643.47  644.58  646.88  651.91  658.20  658.86  658.55  660.05  662.24
  664.66  666.79  667.71  668.57  671.09  671.55
 -301.50 -305.72 -316.59 -324.85 -333.87 -343.13 -358.18 -361.40 -363.88 -363.40
 -362.44 -362.12 -361.52 -360.88 -360.71 -360.71  636.79  636.68 -360.82 -360.83
 -360.99 -361.05 -360.80 -360.40 -359.76 -358.01 -357.05 -356.70 -356.76 -357.05
 -356.87 -356.53 -355.42 -353.12 -348.09 -341.80 -341.14 -341.45 -339.95 -337.76
 -335.34 -333.21 -332.29 -331.43 -328.91 -328.45
Pier Skew, UpSta & Num, DnSta & Num=  ,9919.51, 2 ,9942.33, 2 , 0 , 0 , 0 ,,
    2.00    2.00
 -360.71  639.29
    2.00    2.00
 -360.72  639.28
Pier Skew, UpSta & Num, DnSta & Num=  ,9929.61, 2 ,9952.43, 2 , 0 , 0 , 0 ,,
    2.00    2.00
 -360.71  639.29
    2.00    2.00
 -360.72  639.28
Pier Skew, UpSta & Num, DnSta & Num=  ,9939.70, 2 ,9962.53, 2 , 0 , 0 , 0 ,,
    2.00    2.00
 -360.71  639.29
    2.00    2.00
 -360.73  639.27
Pier Skew, UpSta & Num, DnSta & Num=  ,9949.80, 2 ,9972.63, 2 , 0 , 0 , 0 ,,
    2.00    2.00
 -360.72  639.28
    2.00    2.00
 -360.73  639.27
Pier Skew, UpSta & Num, DnSta & Num=  ,9959.90, 2 ,9982.72, 2 , 0 , 0 , 0 ,,
    2.00    2.00
 -360.72  639.28
    2.00    2.00
 -360.74  639.26
Pier Skew, UpSta & Num, DnSta & Num=  ,9970.00, 2 ,9992.82, 2 , 0 , 0 , 0 ,,
    2.00    2.00
 -360.73  639.27
    2.00    2.00
 -360.74  639.26
Pier Skew, UpSta & Num, DnSta & Num=  ,9980.09, 2 ,10002.92, 2 , 0 , 0 , 0 ,,
    2.00    2.00
 -360.73  639.27
    2.00    2.00
 -360.74  639.26
Pier Skew, UpSta & Num, DnSta & Num=  ,9990.19, 2 ,10013.01, 2 , 0 , 0 , 0 ,,
    2.00    2.00
 -360.74  639.26
    2.00    2.00
 -360.75  639.25
Pier Skew, UpSta & Num, DnSta & Num=  ,10000.29, 2 ,10023.11, 2 , 0 , 0 , 0 ,,
    2.00    2.00
 -360.74  639.26
    2.00    2.00
 -360.75  639.25
Pier Skew, UpSta & Num, DnSta & Num=  ,10010.39, 2 ,10033.21, 2 , 0 , 0 , 0 ,,
    2.00    2.00
 -360.75  639.25
    2.00    2.00
 -360.76  639.24
Pier Skew, UpSta & Num, DnSta & Num=  ,10020.48, 2 ,10043.31, 2 , 0 , 0 , 0 ,,
    2.00    2.00
 -360.75  639.25
    2.00    2.00
 -360.76  639.24
Pier Skew, UpSta & Num, DnSta & Num=  ,10030.58, 2 ,10053.40, 2 , 0 , 0 , 0 ,,
    2.00    2.00
 -360.76  639.24
    2.00    2.00
 -360.77  639.23
Pier Skew, UpSta & Num, DnSta & Num=  ,10040.68, 2 ,10063.50, 2 , 0 , 0 , 0 ,,
    2.00    2.00
 -360.76  639.24
    2.00    2.00
 -360.77  639.23
Pier Skew, UpSta & Num, DnSta & Num=  ,10050.78, 2 ,10073.60, 2 , 0 , 0 , 0 ,,
    2.00    2.00
 -360.77  639.23
    2.00    2.00
 -360.78  639.22
Pier Skew, UpSta & Num, DnSta & Num=  ,10060.87, 2 ,10083.70, 2 , 0 , 0 , 0 ,,
    2.00    2.00
 -360.77  639.23
    2.00    2.00
 -360.78  639.22
Pier Skew, UpSta & Num, DnSta & Num=  ,10070.97, 2 ,10093.79, 2 , 0 , 0 , 0 ,,
    2.00    2.00
 -360.78  639.22
    2.00    2.00
 -360.79  639.21
Pier Skew, UpSta & Num, DnSta & Num=  ,10081.07, 2 ,10103.89, 2 , 0 , 0 , 0 ,,
    2.00    2.00
 -360.78  639.22
    2.00    2.00
 -360.79  639.21
Pier Skew, UpSta & Num, DnSta & Num=  ,10091.17, 2 ,10113.99, 2 , 0 , 0 , 0 ,,
    2.00    2.00
 -360.79  639.21
    2.00    2.00
 -360.80  639.20
Pier Skew, UpSta & Num, DnSta & Num=  ,10101.26, 2 ,10124.09, 2 , 0 , 0 , 0 ,,
    2.00    2.00
 -360.79  639.21
    2.00    2.00
 -360.80  639.20
Pier Skew, UpSta & Num, DnSta & Num=  ,10111.36, 2 ,10134.18, 2 , 0 , 0 , 0 ,,
    2.00    2.00
 -360.80  639.20
    2.00    2.00
 -360.81  639.19
Pier Skew, UpSta & Num, DnSta & Num=  ,10121.46, 2 ,10144.28, 2 , 0 , 0 , 0 ,,
    2.00    2.00
 -360.80  639.20
    2.00    2.00
 -360.81  639.19
BR Coef=-1 , 0 , 0 ,, 0 ,,,0.8,0,1,0,
WSPro=,,,, 1 ,,,, 0 ,,,, 0 ,,,,-1 ,-1 ,-1 , 0 , 0 , 0 , 0 , 0
BC Design=,, 0 ,, 0 ,,,,,,

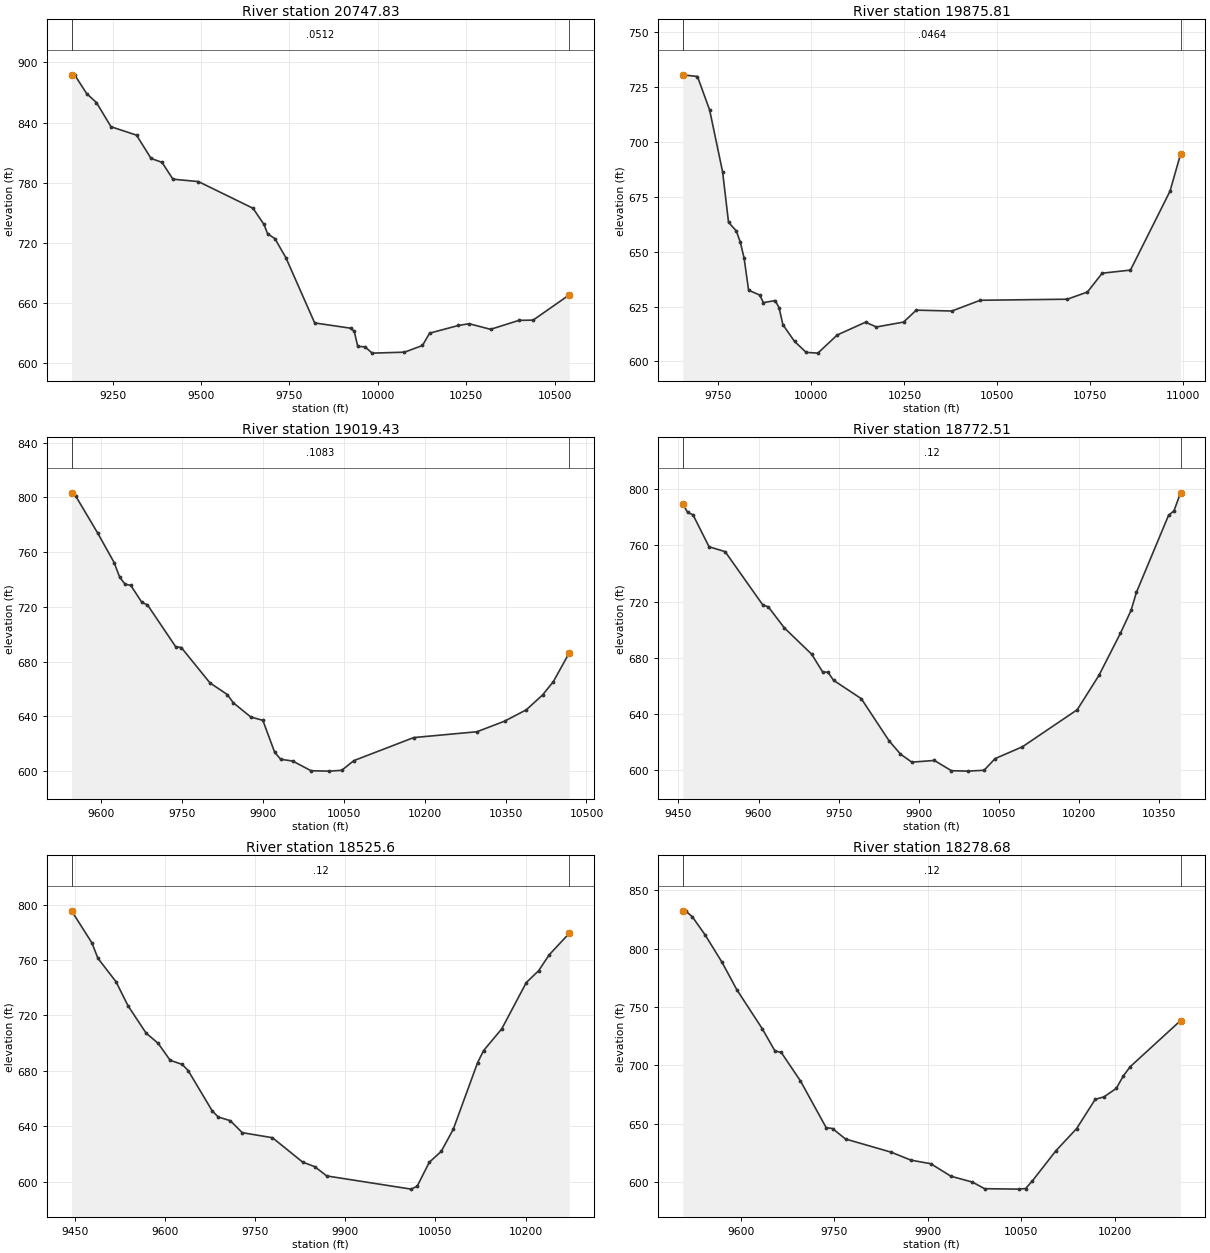
Type RM Length L Ch R = 1 ,20747.83,872.018500,872.018500,872.018500
XS GIS Cut Line= 5
499154.833593041805886.609292999499305.216545433806501.286266536
499214.476850897807013.195109174499200.919214487807199.488032773
 499234.25254783807258.515810534
#Sta/Elev= 30
9134.139887.47929142.778887.67779176.919 868.8989204.547859.98329245.727835.7918
9317.791827.40579358.971804.10369389.856800.23749420.741783.39659492.805780.9952
9647.229754.31849678.114738.17519688.409728.88669708.999723.96469739.883705.1003
9821.496639.73569923.055634.46639933.211631.47249943.367616.19169963.678615.9072
 9983.99609.558610075.39610.505510126.17617.184510146.48629.514610227.73637.1822
 10258.2638.947910318.72633.341610398.93642.296710439.04642.544810541.41667.7954
#Mann= 3 , 0 , 0
9134.139  0.0512       09134.139  0.0512       010541.41  0.0512       0
#XS Ineff= 2 , 0
       09921.702        10159.97       0
Bank Sta=9134.139,10541.41
Exp/Cntr=0.3,0.1

Type RM Length L Ch R = 1 ,19875.81,856.388000,856.388000,856.388000
XS GIS Cut Line= 6
498167.120559633806624.313907087 498660.42507595806771.785687634
498809.052852371806867.214344216498885.583928472806924.300478251
499034.336353974807063.422606758499259.969456243807326.995640122
#Sta/Elev= 30
9654.276730.62489693.812729.85349726.498714.59369761.412 686.357 9777.31663.3867
9798.185659.48389808.622654.49049819.059647.19129831.239632.44899860.808630.2766
9871.246626.78869902.558627.74249912.995624.55589923.432616.72659954.744 609.107
9986.056604.116910017.37603.774510069.55612.057310145.46617.870910174.81615.7036
10247.69617.919210281.96623.371410377.48 622.97110453.83627.869510687.94628.3511
10742.04631.641710781.59640.210210857.57641.624510963.77677.562110992.14 694.413
#Mann= 3 , 0 , 0
9654.276  0.0464       09654.276  0.0464       010992.14  0.0464       0
#XS Ineff= 2 , 0
       0                 10478.8       0
Bank Sta=9654.276,10992.14
Exp/Cntr=0.3,0.1

Type RM Length L Ch R = 1 ,19019.43,246.915200,246.915200,246.915200
XS GIS Cut Line= 6
 498367.54447842 807652.43983455498629.206302517 807580.15908673
498946.652559821807424.519443443499068.863317146807378.771937435
 499166.77085615807364.106696186499233.423690505807375.805596483
#Sta/Elev= 30
9544.566803.39739552.136801.12049592.858774.11879623.576752.44049633.816741.7832
9644.055736.48319654.353735.82539675.093723.27339685.464721.49879737.696690.9382
9748.203690.31359801.394664.45189833.659655.93939844.494649.9953 9877.32639.4778
9899.431637.13419921.542613.66389932.598608.62719954.834607.36019988.889600.2504
10023.06599.970310045.86600.554410068.28607.637510179.35624.492910296.79628.7622
10348.08636.502710388.34644.799510418.44655.617910438.52665.395910468.14 686.534
#Mann= 3 , 0 , 0
9544.566  0.1083       09544.566  0.1083       010468.14  0.1083       0
#XS Ineff= 2 , 0
       0                               0
Bank Sta=9544.566,10468.14
Exp/Cntr=0.3,0.1

Type RM Length L Ch R = 1 ,18772.51,246.915200,246.915200,246.915200
XS GIS Cut Line= 6
 498395.92476333807822.721543999498667.554298685807785.568678708
498892.237075302807714.101540919 499086.54734694807670.893765435
499214.090803806807655.614540787499307.050135051807664.419440154
#Sta/Elev= 30
9458.212789.79369467.303783.50039477.334781.87069507.428759.05019537.522755.5844
9608.109717.52229618.202716.2669 9648.48 701.1769699.482682.47379719.893669.8871
9730.099669.59279740.441663.86149792.385650.76759844.576620.6304 9865.73611.2664
9886.883605.53029929.191606.73679960.921599.4402 9991.77599.125410022.24599.7363
10042.62608.024810094.08616.504810196.52642.887110237.03667.292410277.19697.2771
10297.22713.633310307.22726.459510367.49781.496910377.64 784.64310389.87797.4895
#Mann= 3 , 0 , 0
9458.212    0.12       09458.212    0.12       010389.87    0.12       0
#XS Ineff= 2 , 0
       0                               0
Bank Sta=9458.212,10389.87
Exp/Cntr=0.3,0.1

Type RM Length L Ch R = 1 , 18525.6,246.915200,246.915200,246.915200
XS GIS Cut Line= 6
498411.149359139 807922.43761398 498697.80660329 807933.80582711
498904.998541708807952.392620778499042.127188386 807951.46276234
499161.769373465 807969.45162357 499234.08542942 807988.70702069
#Sta/Elev= 30
9444.753795.58239478.646772.41939488.654761.26759518.676744.4122 9538.69727.0169
9568.712707.28849588.727699.92629608.742687.64849628.757 684.6559638.764680.2003
9678.794651.06579688.801646.66439708.816644.0007 9728.83635.33269778.952 631.702
9829.154614.11789849.249610.81179869.345 604.08110009.77594.556610019.77596.6513
10039.79 613.91110059.81621.844510079.84637.848410120.15685.784310130.23694.6284
10160.57710.416810201.31743.788510221.86752.339910239.37763.805210272.87779.4146
#Mann= 3 , 0 , 0
9444.753    0.12       09444.753    0.12       010272.87    0.12       0
#XS Ineff= 2 , 0
       0                               0
Bank Sta=9444.753,10272.87
Exp/Cntr=0.3,0.1

Type RM Length L Ch R = 1 ,18278.68,246.915300,246.915300,246.915300
XS GIS Cut Line= 6
 498380.03530052  808033.3659969498618.790314454808083.418841539
498763.813856088808129.683767455498871.727112786808173.462358871
 498948.93259712808209.765997515499125.474069929808303.204344932
#Sta/Elev= 30
9507.173 832.3949512.223832.04699522.395827.40119542.738 811.9969570.063788.3788
9593.682764.92619634.472731.49069654.867712.36669665.065711.01539695.872686.6057
9736.991646.63139747.271645.83659768.018636.88399841.262625.57959872.981618.7563
9904.723615.69549937.042604.96919971.512 599.9519990.906594.310410045.62593.9331
10056.67594.413610067.72601.128310105.22 626.79210138.52645.859410168.27670.8999
10182.24672.957710202.01680.227910213.25690.8997 10224.5698.930210304.99738.3206
#Mann= 3 , 0 , 0
9507.173    0.12       09507.173    0.12       010304.99    0.12       0
#XS Ineff= 2 , 0
       0                               0
Bank Sta=9507.173,10304.99
Exp/Cntr=0.3,0.1

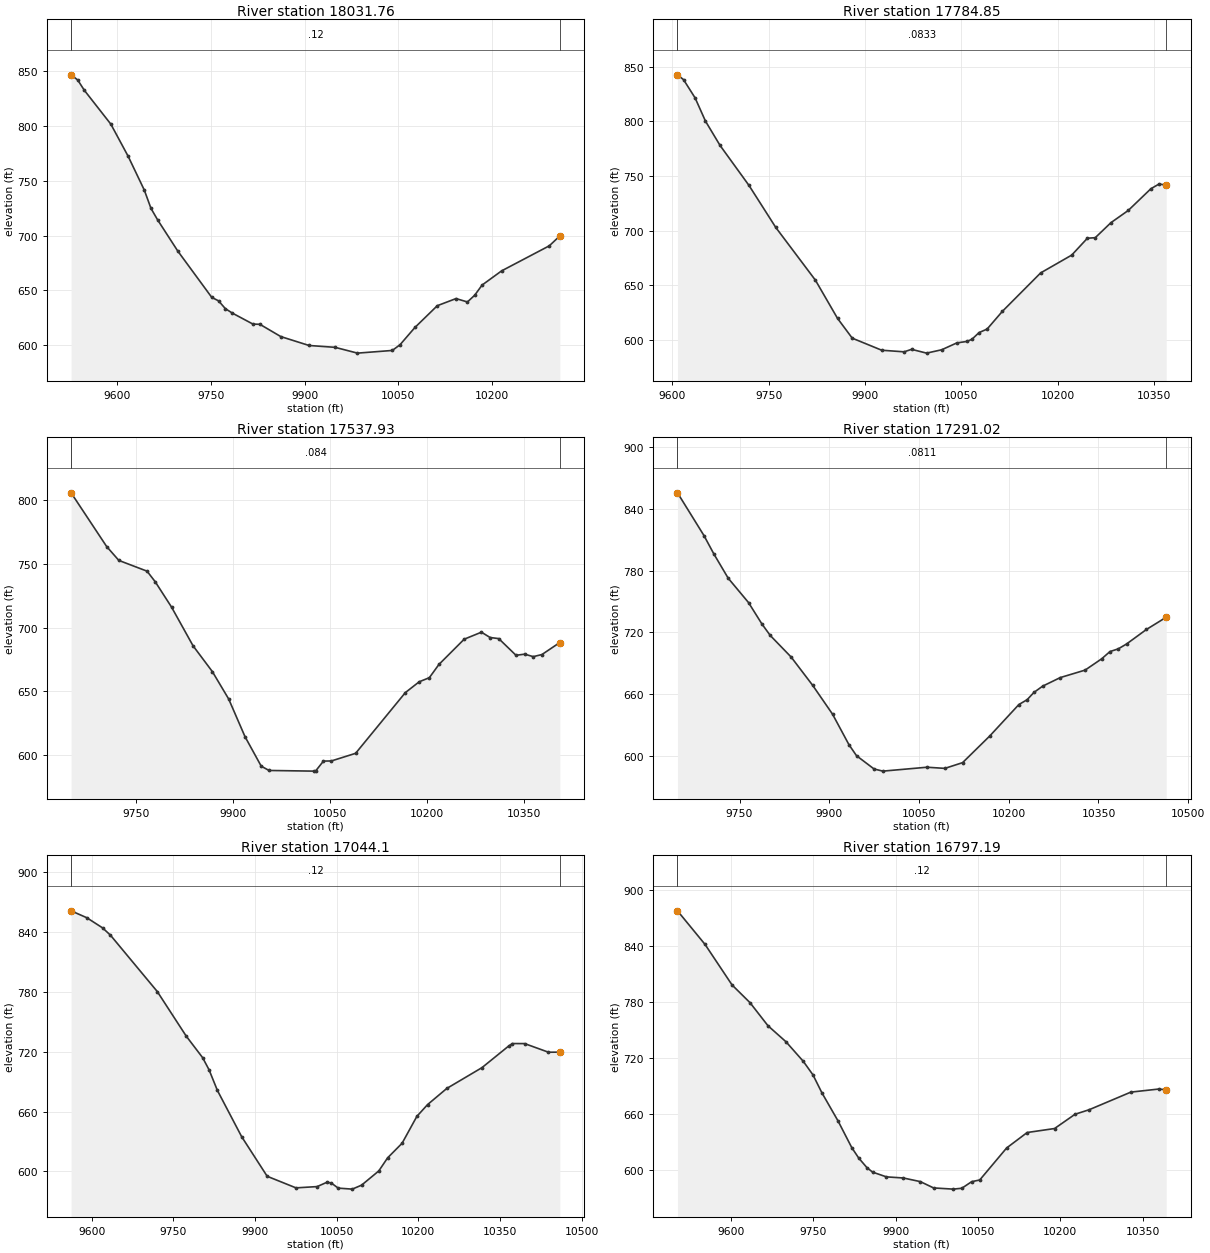
Type RM Length L Ch R = 1 ,18031.76,246.915200,246.915200,246.915200
XS GIS Cut Line= 6
498335.046640525808193.760349977498497.350140604808254.751884476
498630.419977351808314.765930629498689.703488049808346.025365149
498737.821509545 808375.46419725499018.859656123808566.449811146
#Sta/Elev= 30
9525.745846.68999536.316841.98329546.936832.57449589.416801.67559617.178772.3159
9642.965741.57829653.697724.82299664.429714.26929696.625685.90329751.021643.6621
9761.907640.49699772.794633.39619783.841629.36359817.027619.28679828.089619.1045
9861.629607.89369906.849599.77029948.525 598.0839984.447592.797110040.18595.2372
10052.55600.428210076.46 616.20710112.33636.081110142.28642.559510160.53639.4747
 10172.1 645.55910184.05654.902110215.27667.826410291.65690.691310308.51699.6834
#Mann= 3 , 0 , 0
9525.745    0.12       09525.745    0.12       010308.51    0.12       0
#XS Ineff= 2 , 0
       0                               0
Bank Sta=9525.745,10308.51
Exp/Cntr=0.3,0.1

Type RM Length L Ch R = 1 ,17784.85,246.915200,246.915200,246.915200
XS GIS Cut Line= 6
498276.659565752808401.922964405 498402.73397581808470.205531712
498617.728529416808593.466039454498784.413479935808699.669789541
498871.968870445808761.281972307498923.957603848808800.775866162
#Sta/Elev= 30
9607.776842.56369617.261838.11399635.235821.42089651.379800.18899674.124777.9173
9719.226741.30319760.927702.87749822.611654.67859857.039619.75279879.991601.6166
9925.895 590.5859960.719589.12349972.416591.38439995.809587.930810019.37591.0104
10042.93597.2938 10058.6598.624610066.49 600.64410077.52606.733710090.05609.9358
10113.73626.088810173.46661.332410221.83677.621210246.28693.072810258.51693.5494
10282.97707.304110309.86718.4436 10345.2738.362810357.76742.606910369.01741.7813
#Mann= 3 , 0 , 0
9607.776  0.0833       09607.776  0.0833       010369.01  0.0833       0
#XS Ineff= 2 , 0
       0                               0
Bank Sta=9607.776,10369.01
Exp/Cntr=0.3,0.1

Type RM Length L Ch R = 1 ,17537.93,246.915200,246.915200,246.915200
XS GIS Cut Line= 6
498220.881913462808600.782420351498451.943590128808777.399009773
498539.403840536808836.192445752498592.058809174808875.725584539
498700.262170418 808965.36402193498815.720382486809068.028264543
#Sta/Elev= 30
9648.838805.49079703.882 763.4799722.782752.59279766.473744.17349779.121735.9125
9804.417716.06269837.769685.75069867.657665.56769892.953644.1243 9918.25614.6295
9943.374 591.5379955.462588.182110024.85587.664110027.77587.851610039.78595.5216
10052.06595.630810089.58601.599810166.67649.141610188.15657.612110203.82 660.797
10218.62671.139910257.76690.914510284.52696.415410297.91692.252710311.29691.3985
10338.05678.336910351.43679.207810364.81 677.28410378.19678.909510405.92688.3215
#Mann= 3 , 0 , 0
9648.838   0.084       09648.838   0.084       010405.92   0.084       0
#XS Ineff= 2 , 0
       0                               0
Bank Sta=9648.838,10405.92
Exp/Cntr=0.3,0.1

Type RM Length L Ch R = 1 ,17291.02,246.915200,246.915200,246.915200
XS GIS Cut Line= 6
498062.033752286808714.361835303498121.598846972808767.819458677
498216.069558943808861.031619048498330.206216269808983.016493387
498455.532945331809122.801508858498627.849049659809302.934209901
#Sta/Elev= 30
9646.352855.39419690.648813.91829707.195796.06049731.166772.54579765.087748.9701
9787.359728.29739801.407717.05749836.277696.15719872.212668.77059905.503640.7469
9932.823 611.2569945.609600.42789974.967587.54669989.647585.4878 10063.3589.2664
10093.26588.159210122.84593.703810168.16619.498210216.94650.064310230.78654.7708
10242.06661.786610256.53667.850510286.14 676.21210327.65683.464910355.33694.4101
10369.17701.435510383.01704.059510396.85708.761610430.13722.866910463.18734.7254
#Mann= 3 , 0 , 0
9646.352  0.0811       09646.352  0.0811       010463.18  0.0811       0
#XS Ineff= 2 , 0
       0                               0
Bank Sta=9646.352,10463.18
Exp/Cntr=0.3,0.1

Type RM Length L Ch R = 1 , 17044.1,246.915200,246.915200,246.915200
XS GIS Cut Line= 6
497825.026501858808845.586188652497919.738051883808944.240686243
498035.672170336809054.457799441498282.287993652809259.567490558
498408.938554046809383.561107536498479.225466743809458.417342876
#Sta/Elev= 30
9562.351860.94599591.192854.03349620.071843.89639634.511 836.6319720.557780.1762
 9773.69735.57329803.839713.97299815.585701.92919831.013681.13389875.574634.8189
9922.456595.17699975.342583.577910014.24584.865910032.32589.226110040.01588.5132
10052.89  583.3310078.66582.322410095.76586.287510127.42600.546910143.62613.6364
 10170.2628.261710197.34655.170810217.01 666.96410252.26683.114410316.92703.9592
10366.01725.625610372.85728.054410395.23728.034110439.06719.381110459.84719.4754
#Mann= 3 , 0 , 0
9562.351    0.12       09562.351    0.12       010459.84    0.12       0
#XS Ineff= 2 , 0
       0                               0
Bank Sta=9562.351,10459.84
Exp/Cntr=0.3,0.1

Type RM Length L Ch R = 1 ,16797.19,246.915300,246.915300,246.915300
XS GIS Cut Line= 6
 497684.30187747808923.501517405497923.217835251809233.392105806
497958.434981839809282.624177308498027.109574856809385.736282438
498114.718426877809503.267327868 498218.40803225 809635.65281495
#Sta/Elev= 30
9502.594877.85689552.872841.77529602.006798.35939634.762779.32929667.518754.5536
9700.274737.42559731.771716.45149749.408701.94119765.786682.60089794.906652.7274
 9820.16623.86299832.786612.69759847.676602.4558 9858.04597.58579883.294592.4893
9914.142591.28729945.048587.40959969.233580.624110005.15 579.33910020.72580.2994
10038.65587.344510053.33589.154110102.34623.499810139.76640.065310189.65644.3378
 10227.1659.691310252.51664.466110328.72683.414410379.53686.695910393.06685.9041
#Mann= 3 , 0 , 0
9502.594    0.12       09502.594    0.12       010393.06    0.12       0
#XS Ineff= 2 , 0
       0                               0
Bank Sta=9502.594,10393.06
Exp/Cntr=0.3,0.1

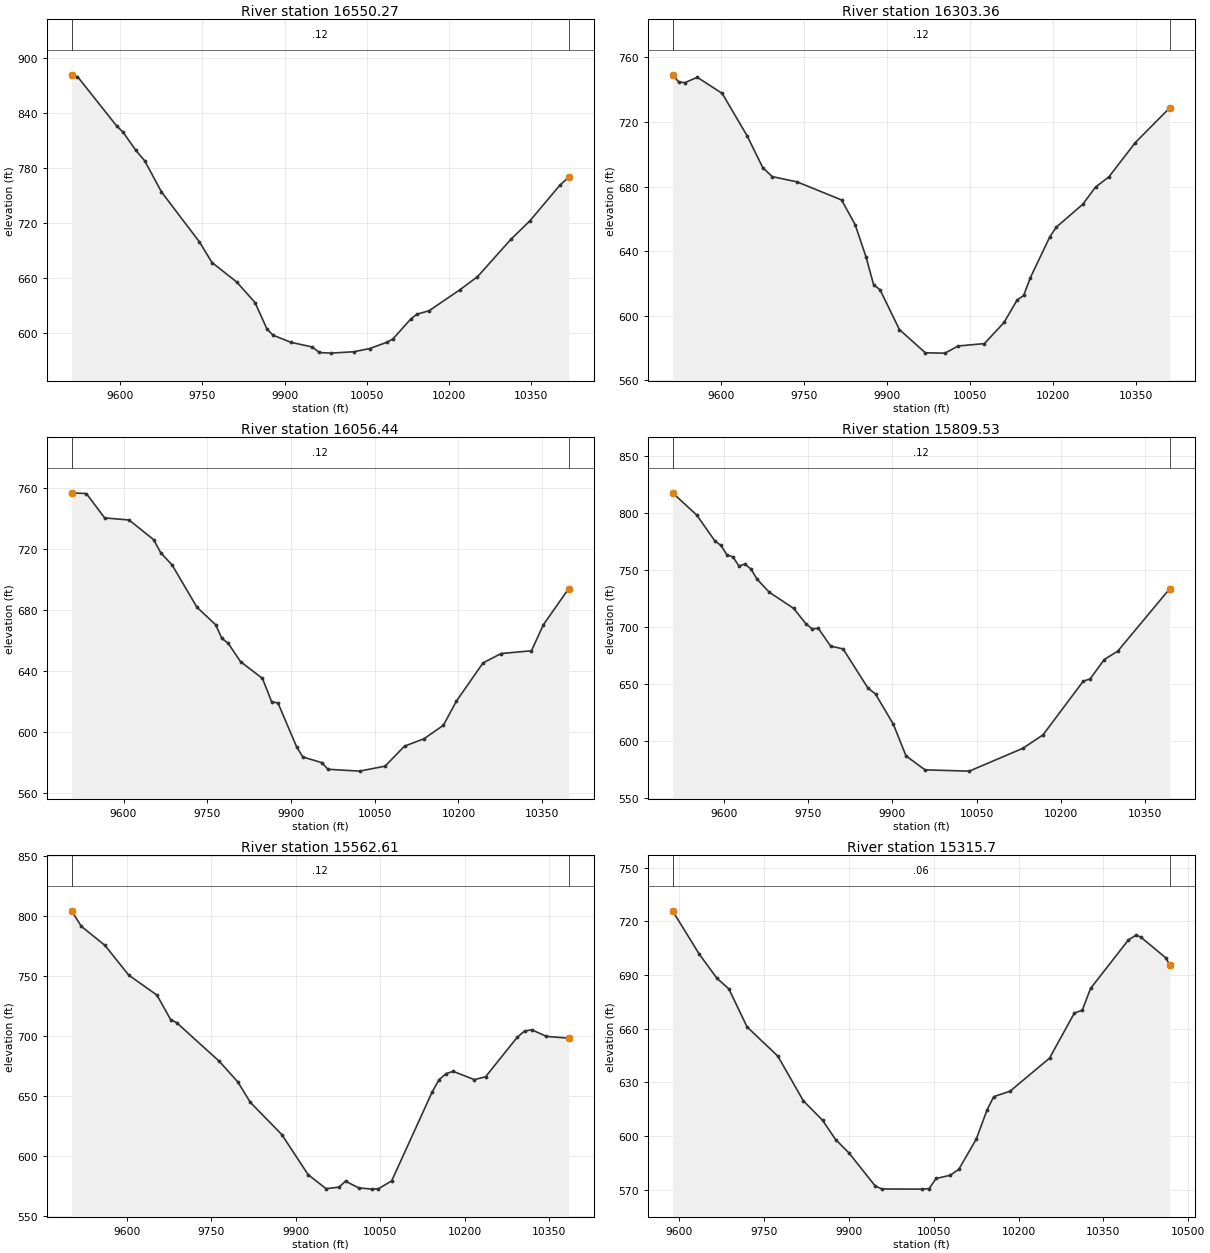
Type RM Length L Ch R = 1 ,16550.27,246.915200,246.915200,246.915200
XS GIS Cut Line= 6
497553.660079339808995.834264401497716.179530075809271.278691729
497751.566246535809353.639999594497782.498746088809489.086330268
497808.859944827809556.815435352497954.101061581809803.134459716
#Sta/Elev= 30
9510.926881.16789521.817879.25489593.109825.62789604.952818.75269628.324798.8717
9644.782787.31029675.069753.61379744.417 699.1569767.381676.61469812.578655.3936
 9846.01632.9525 9868.02603.79229879.024597.41749911.327589.68139950.318584.5885
9963.551578.56499983.975577.876310026.32579.375210055.46582.886510087.09589.7945
 10097.8593.361210130.42615.128710141.54620.293910163.87624.091610220.46647.1185
   10252661.067710313.77   702.310347.53721.8323 10402.4760.792810418.63 769.599
#Mann= 3 , 0 , 0
9510.926    0.12       09510.926    0.12       010418.63    0.12       0
#XS Ineff= 2 , 0
       0                               0
Bank Sta=9510.926,10418.63
Exp/Cntr=0.3,0.1

Type RM Length L Ch R = 1 ,16303.36,246.915200,246.915200,246.915200
XS GIS Cut Line= 6
497319.957741291809125.228779225497418.746697461809315.082065153
497468.603124487 809405.61173918 497527.60511521809504.718317505
497725.249407448 809816.69022387497778.410558305809896.801539634
#Sta/Elev= 30
9512.349749.24719523.329744.84979534.566744.39859557.041747.70559602.001737.7487
9647.192711.36669675.338691.72379692.383686.20529737.692682.89089817.605671.7477
9842.224656.43389861.773636.52759875.559619.24669887.197616.08469922.111591.4979
9969.077577.053610004.61576.868210028.28581.297110075.63582.763710111.14595.8453
10134.82609.769610146.65 612.59110158.49623.4345   10194648.981310205.84 654.981
10253.18668.983410276.86  679.8610300.53685.993810348.35707.280210410.51728.7995
#Mann= 3 , 0 , 0
9512.349    0.12       09512.349    0.12       010410.51    0.12       0
#XS Ineff= 2 , 0
       0                               0
Bank Sta=9512.349,10410.51
Exp/Cntr=0.3,0.1

Type RM Length L Ch R = 1 ,16056.44,246.915200,246.915200,246.915200
XS GIS Cut Line= 6
497129.553250862809230.650474509497208.601841781809405.869124116
497344.030965766809675.667500743497435.098631952809834.701924886
497506.498654215809945.468283272497553.307494542810012.166859819
#Sta/Elev= 30
9506.871756.68819533.465756.20239566.231740.26639610.006738.90879654.077725.9955
9666.699717.45579687.129709.43879731.603681.78739765.071670.32159776.227661.4474
9787.383658.25959809.695646.17289848.887635.21499865.475619.82579876.631619.2275
  9910.1590.45739921.269583.75789955.113 580.0649966.394575.711610023.01574.5043
 10068.7577.763510103.48590.869910138.26595.666810173.04604.502510196.54620.4037
10244.13645.353210276.39 651.46710330.87653.299810352.15670.271410397.55693.9761
#Mann= 3 , 0 , 0
9506.871    0.12       09506.871    0.12       010397.55    0.12       0
#XS Ineff= 2 , 0
       0                               0
Bank Sta=9506.871,10397.55
Exp/Cntr=0.3,0.1

Type RM Length L Ch R = 1 ,15809.53,246.915200,246.915200,246.915200
XS GIS Cut Line= 6
496923.971271793809344.475525066497023.226151786809590.119962816
497114.248255822809770.893074107497185.685207035809891.682637807
497254.679340798 809997.28862696497343.529793008 810119.67793187
#Sta/Elev= 30
 9508.67817.43979551.727797.93839583.885775.30849594.636771.34429605.388763.1725
9616.139761.19679626.891753.27949637.643754.92329648.394750.50019659.146741.6829
 9680.82730.26499724.462716.01129746.284702.40819757.195698.15079768.105698.5459
 9790.17 682.9799812.318680.49679856.614646.12689870.044640.91059901.727614.4755
9924.308 586.682 9958.18574.420110037.01573.303110132.37 593.333 10168.2605.0903
10239.87652.209510252.11654.223610277.39671.2177 10301.4678.594910393.86733.3208
#Mann= 3 , 0 , 0
 9508.67    0.12       0 9508.67    0.12       010393.86    0.12       0
#XS Ineff= 2 , 0
       0                               0
Bank Sta=9508.67,10393.86
Exp/Cntr=0.3,0.1

Type RM Length L Ch R = 1 ,15562.61,246.915200,246.915200,246.915200
XS GIS Cut Line= 6
496718.602697188809458.182419451496758.616688098809585.815331099
496791.069231591809670.013990382496885.436801562809867.200770239
496995.334245623810045.066732968497138.710679508810224.647727533
#Sta/Elev= 30
9502.369804.3916  9519.8791.46279561.797775.50299603.794750.74479653.896734.0574
9678.142 713.6279688.859711.04459764.684 678.7139797.526661.48199819.421644.6161
9875.267617.68689922.052584.17189953.996572.46459976.909573.81869988.365578.7482
10011.47573.202310034.78572.121910046.44572.394310070.18578.997310142.17653.3587
10154.17663.395910166.69668.510110179.21670.440210216.79663.531510236.73665.8683
10292.86698.848510305.83704.0333 10318.8705.103810344.75 699.58710384.14698.1522
#Mann= 3 , 0 , 0
9502.369    0.12       09502.369    0.12       010384.14    0.12       0
#XS Ineff= 2 , 0
       0                               0
Bank Sta=9502.369,10384.14
Exp/Cntr=0.3,0.1

Type RM Length L Ch R = 1 , 15315.7,246.915200,246.915200,246.915200
XS GIS Cut Line= 6
496525.606984711809669.701136912496557.670540544809775.973797589
 496586.86356273809844.586355778496708.395241008810054.763813513
496838.681127048810210.550826127497018.755816091810380.075964719
#Sta/Elev= 30
9588.063 725.959 9634.81701.94919666.449688.24599687.562682.30719719.824660.9867
9774.179644.68689819.395619.64319853.306 608.7759876.398597.96449899.532590.6769
9946.458572.0053 9958.19570.329710029.31570.243210041.71570.5238 10054.1576.1973
10078.89 577.973 10094.2581.278610125.21598.281910144.26614.569710156.07621.9755
10184.93625.053610254.68643.512310298.76668.8284 10312.5670.280410327.24682.5131
10394.09709.6214 10407.7712.359110415.62711.389610459.82699.785710467.29695.8253
#Mann= 3 , 0 , 0
9588.063    0.06       09588.063    0.06       010467.29    0.06       0
#XS Ineff= 2 , 0
       0                               0
Bank Sta=9588.063,10467.29
Exp/Cntr=0.3,0.1

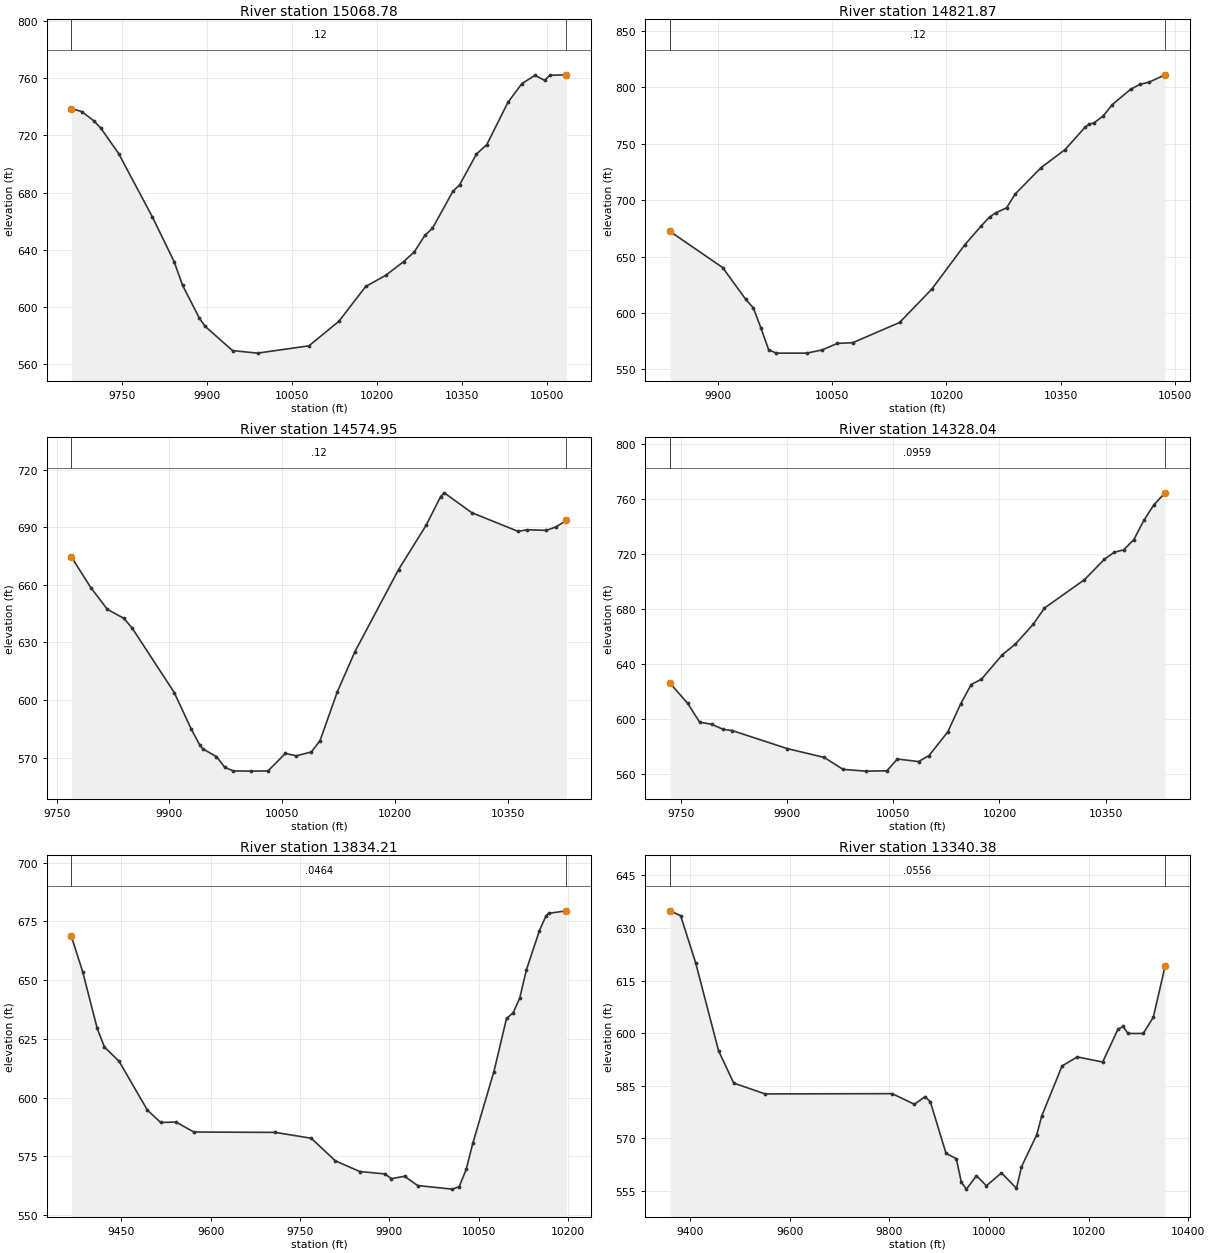
Type RM Length L Ch R = 1 ,15068.78,246.915300,246.915300,246.915300
XS GIS Cut Line= 6
496319.431600651809927.420366994496363.480379566810031.389582957
 496396.79487949810076.327999076 496544.18920061810233.656561383
496834.153170154810424.563766243496948.253371337810508.093561714
#Sta/Elev= 30
9660.509738.75699678.695736.62869699.643730.29559712.115725.20979743.835707.3183
9803.393663.0364 9841.76631.84049856.739615.23619886.178  592.479896.272586.6677
9945.056569.60249989.214567.840210079.95 572.94410132.92590.171310180.05614.4147
10215.41622.179610246.99 631.78510265.89638.5938 10284.8650.280410297.98655.0833
10333.97680.882910345.97685.515210375.64706.971510393.69 713.44110431.04 742.971
10455.74756.147610478.91761.909610495.95758.429610505.13762.003410534.37762.2915
#Mann= 3 , 0 , 0
9660.509    0.12       09660.509    0.12       010534.37    0.12       0
#XS Ineff= 2 , 0
       0                               0
Bank Sta=9660.509,10534.37
Exp/Cntr=0.3,0.1

Type RM Length L Ch R = 1 ,14821.87,246.915200,246.915200,246.915200
XS GIS Cut Line= 6
496286.775492426810412.091576624496368.404908384810424.480661201
 496519.66423543810434.970782307496631.941174636810464.613804398
496738.431534457810513.544359134496892.054904577 810610.13814606
#Sta/Elev= 30
 9837.44672.26379906.496640.24849936.656612.16089946.671604.50779956.687586.6988
9966.702567.52549976.717 564.43710016.78  564.4310036.84567.258410056.95573.0619
10077.15573.662210138.62591.624610180.69621.073210223.97660.358910245.74677.2652
10256.62685.1034 10264.4688.676110278.94693.270210290.17705.422710324.27728.9216
 10355.6744.811710382.31764.988210387.34767.266210394.07768.755710405.83774.7805
10417.71784.796610441.83798.416610453.88802.654210465.94804.633810486.83811.1275
#Mann= 3 , 0 , 0
 9837.44    0.12       0 9837.44    0.12       010486.83    0.12       0
#XS Ineff= 2 , 0
       0                               0
Bank Sta=9837.44,10486.83
Exp/Cntr=0.3,0.1

Type RM Length L Ch R = 1 ,14574.95,246.915200,246.915200,246.915200
XS GIS Cut Line= 6
496171.618451423810559.235414597 496252.78848151810596.666797438
496363.713706399810652.694247011496495.816897599810728.244650353
496597.930441833810792.747362426 496735.92727018810893.633061052
#Sta/Elev= 30
9769.719674.44579795.467658.50719817.491 647.1619839.515642.47399850.527637.3511
9906.395603.81889928.801584.89079940.004576.69139944.129574.56279962.411570.4433
9973.614564.84689984.855563.011710008.21562.903410030.93563.013510053.97 572.123
10068.62570.879810088.53572.903410100.05578.8395 10123.1604.335610146.42625.1612
10204.38667.907810241.04691.006910260.23705.9213   10265707.863210301.78 697.492
10363.07 687.80710375.34688.629510400.74688.317910413.32690.085210427.32693.4737
#Mann= 3 , 0 , 0
9769.719    0.12       09769.719    0.12       010427.32    0.12       0
#XS Ineff= 2 , 0
       0                               0
Bank Sta=9769.719,10427.32
Exp/Cntr=0.3,0.1

Type RM Length L Ch R = 1 ,14328.04,493.830400,493.830400,493.830400
XS GIS Cut Line= 6
496024.739778973810690.132194926496087.819009484810736.831688967
496176.209786968810809.476700689496230.098508975810856.915079486
496458.509921686811067.492993418496546.120808606811155.902615324
#Sta/Elev= 30
9734.309626.17869759.296611.55679776.102597.86419792.909596.41899809.286592.6662
9822.088591.80669899.752578.70579952.239572.22749978.885563.516710011.06562.2627
10040.86562.497810055.76 571.09110085.56569.213110100.46573.6136   10127590.8454
10145.16611.218910160.01625.278910174.62 629.20510203.82646.822910222.53654.6958
10247.63 669.067 10263.7680.957110320.25701.605610348.41716.446210362.49721.6158
10375.73723.281410389.94730.709910404.14744.681210418.35756.089410434.15764.8021
#Mann= 3 , 0 , 0
9734.309  0.0959       09734.309  0.0959       010434.15  0.0959       0
#XS Ineff= 2 , 0
       0                               0
Bank Sta=9734.309,10434.15
Exp/Cntr=0.3,0.1

Type RM Length L Ch R = 1 ,13834.21,493.830400,493.830400,493.830400
XS GIS Cut Line= 6
495928.188267916810619.539601535495862.216045707810713.289601535
495792.962834426810852.754561382495792.232663865810915.687045118
495828.639064693811106.257704615495967.202124078811376.208841343
#Sta/Elev= 30
9365.845668.5719 9384.75653.58919409.206629.45559421.434 621.5079445.889 615.523
9493.556594.72429515.886589.47879541.675589.63199571.711585.40229708.523585.2494
9768.863582.75719809.411573.16899850.485568.60959892.608567.58929903.597565.5706
9925.693566.59279947.788562.640210005.83561.121510017.53562.144810029.24569.4939
10040.67580.8722 10075.9611.1363 10097.1633.722910108.34636.146910119.37642.4415
 10130.4654.300410152.45671.096110163.48677.393410167.74678.399610197.69679.4715
#Mann= 3 , 0 , 0
9365.845  0.0464       09365.845  0.0464       010197.69  0.0464       0
#XS Ineff= 2 , 0
       0                               0
Bank Sta=9365.845,10197.69
Exp/Cntr=0.3,0.1

Type RM Length L Ch R = 1 ,13340.38,740.745700,740.745700,740.745700
XS GIS Cut Line= 6
495791.035490155810621.275712654495646.938267916810746.275712654
495517.738664062 810900.11545948495475.695654878810966.227139734
495439.852795815811075.548777289495374.104598037811478.207516543
#Sta/Elev= 30
9359.582634.90569380.811633.51539411.048 620.041 9456.83595.06299487.352585.8054
9550.341582.70999805.648582.78379850.103579.7589 9871.78 581.9329882.276580.4173
9913.721 565.7439934.246564.25839944.508557.48249954.619555.56419974.816559.3916
9994.863556.511410024.93560.204110055.13555.795510065.21561.942310095.75571.0354
10105.94576.4645 10146.7590.685310177.27593.257310228.22591.7962 10258.8 601.111
10268.99601.947110279.15 599.946 10309.6 599.938 10329.9 604.56410353.46619.0916
#Mann= 3 , 0 , 0
9359.582  0.0556       09359.582  0.0556       010353.46  0.0556       0
#XS Ineff= 2 , 0
       0                               0
Bank Sta=9359.582,10353.46
Exp/Cntr=0.3,0.1