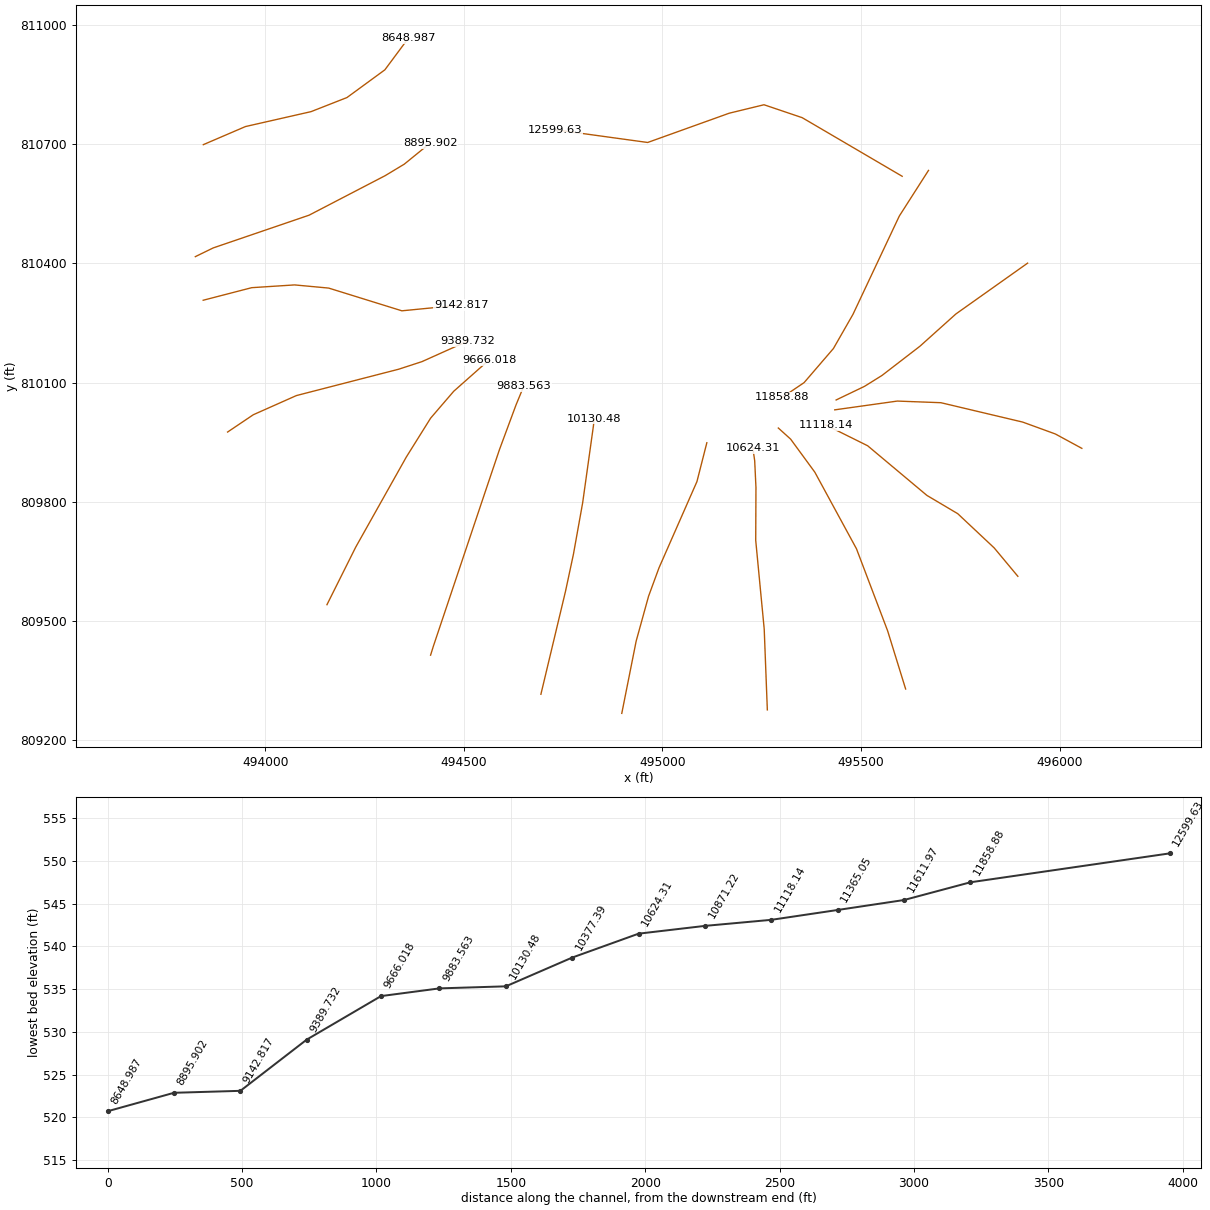
HEC-RAS study 5238_ras.prj: 5238

--- 5238_ras.g01 (geometry) --- (continued)

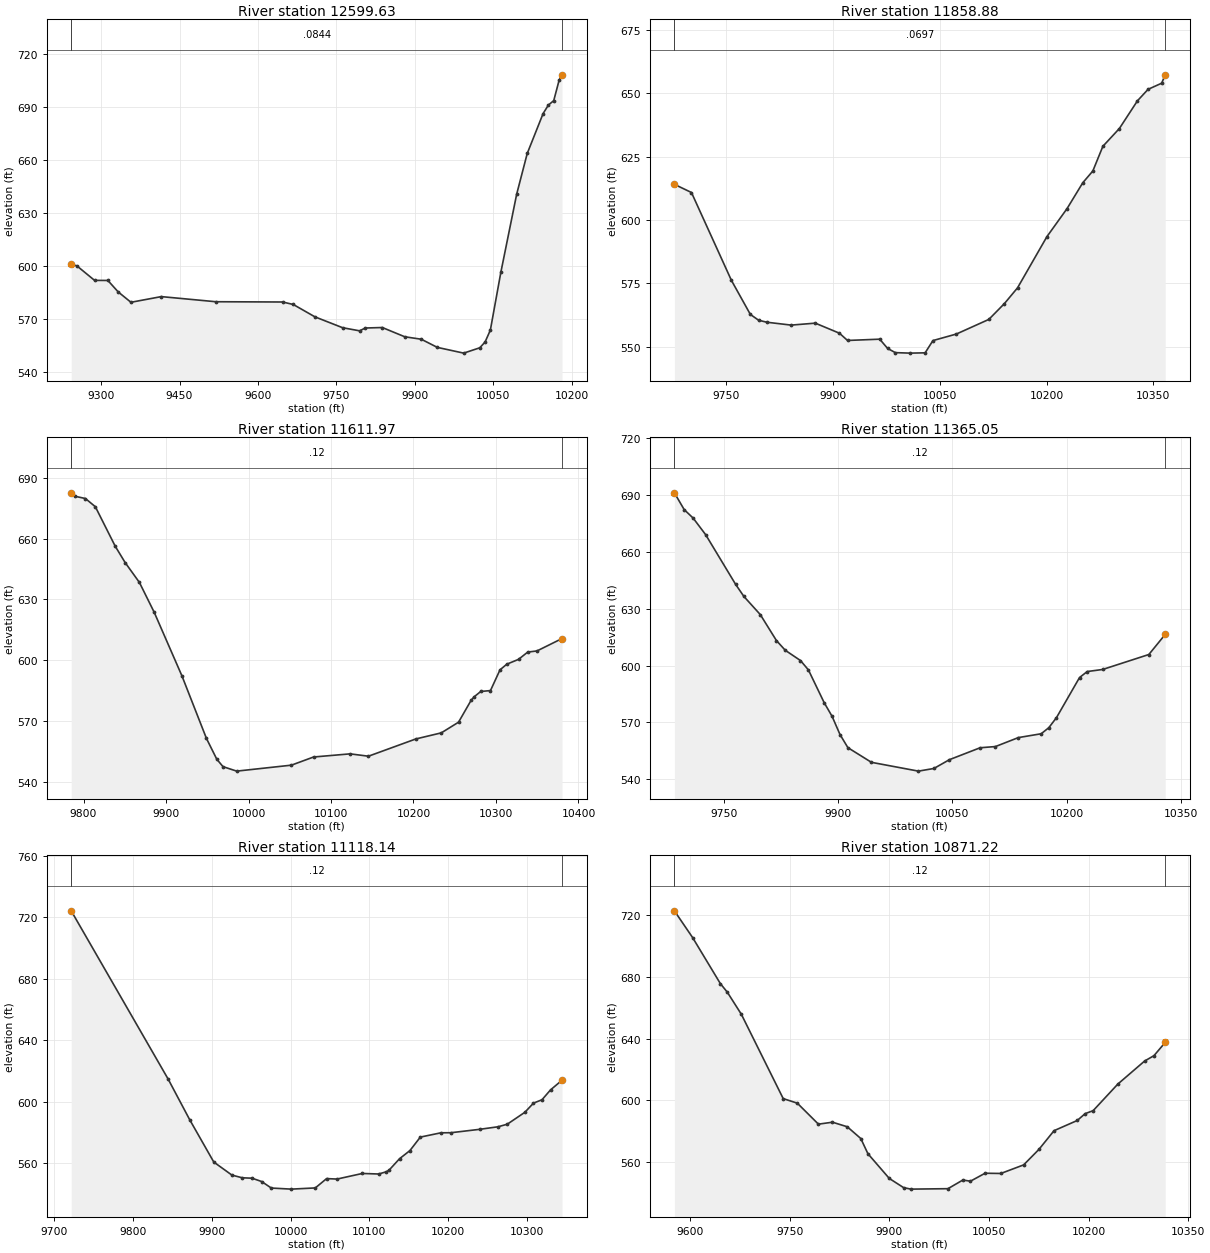
Type RM Length L Ch R = 1 ,12599.63,740.745600,740.745600,740.745600
XS GIS Cut Line= 6
495603.535490155810619.539601535495351.799379021810767.109045982
 495255.66274035810799.626287671495168.061595409810778.340233901
494962.745663422810704.646204203494729.638449721810736.742778406
#Sta/Elev= 30
9242.958601.17099253.755600.23729287.626592.01759313.076591.9664 9332.85 585.466
9357.176 579.6299415.133582.83859519.457579.94199647.095579.79219667.445578.3909
9708.899 571.3879761.808565.24679794.199563.49749805.061565.08439837.646565.3636
9880.577560.13149912.085558.74649942.792554.13449993.204550.886710023.92553.9042
10034.09557.186710044.16563.9133 10064.3596.727910094.51640.809410114.64663.7696
   10145686.339910155.15691.1491 10165.3693.6436 10175.6705.170410181.13708.2255
#Mann= 3 , 0 , 0
9242.958  0.0844       09242.958  0.0844       010181.13  0.0844       0
#XS Ineff= 2 , 0
       0                               0
Bank Sta=9242.958,10181.13
Exp/Cntr=0.3,0.1

Type RM Length L Ch R = 1 ,11858.88,246.915300,246.915300,246.915300
XS GIS Cut Line= 6
495669.838674969810634.306708251 495596.27576535810519.269163687
495479.623348313810271.790112729495430.423665796810185.804527286
495356.654922129 810100.02696565 495301.68527512 810062.89720772
#Sta/Elev= 30
9676.768614.08379700.755610.86069756.924 576.1999783.528562.78029795.142560.4799
9806.756559.69439840.881558.56129874.837559.32949908.793555.35879920.112552.5027
9965.386553.01099976.479549.35859987.321547.703810008.21547.507310029.21547.6279
10040.19552.457410073.14555.039910118.75560.805810140.65567.051410159.08573.2499
10200.33593.417610228.78604.549410250.86 614.72510264.95619.351310279.04629.0783
10302.25636.102610327.69647.042910342.55651.547610361.68653.972110366.66657.2741
#Mann= 3 , 0 , 0
9676.768  0.0697       09676.768  0.0697       010366.66  0.0697       0
#XS Ineff= 2 , 0
       0                               0
Bank Sta=9676.768,10366.66
Exp/Cntr=0.3,0.1

Type RM Length L Ch R = 1 ,11611.97,246.915200,246.915200,246.915200
XS GIS Cut Line= 6
495919.424755202810400.872558714495738.887386655810272.922481441
495648.301978234810191.645149093495552.763184624810118.064255683
495508.600660617810090.531555417495437.255424419810056.297488114
#Sta/Elev= 30
9785.048 682.5099790.227680.7597 9802.27679.70779814.313675.66279838.398656.2122
9850.441648.15099867.729 638.3719885.676623.65739919.295592.33959949.024561.5172
9961.554551.28429969.086547.63469985.683545.4321   10052548.368910078.87552.3886
10123.15553.9379 10145.4552.781810202.82561.281410233.73564.281910254.61569.5304
10269.76580.242710273.52582.038810281.54584.667110293.32585.1055 10304.9595.3377
10313.13598.103610327.31600.476710338.51604.075710349.71604.629510380.06610.7367
#Mann= 3 , 0 , 0
9785.048    0.12       09785.048    0.12       010380.06    0.12       0
#XS Ineff= 2 , 0
       0                               0
Bank Sta=9785.048,10380.06
Exp/Cntr=0.3,0.1

Type RM Length L Ch R = 1 ,11365.05,246.915200,246.915200,246.915200
XS GIS Cut Line= 6
496055.909633898809934.519776417495989.159554475809970.723732174
495907.172686011810000.594125166495700.955707139810049.451224781
495591.316848224810053.540982536495433.757504495810031.447080227
#Sta/Elev= 30
9684.987691.12459697.834682.27979709.609677.79019726.002669.05429765.475642.7612
 9776.25636.44039797.801626.84999818.963613.16179830.576608.03099850.545602.6178
9860.918597.68899881.664580.36339892.038573.16529902.411563.57549912.784556.6398
9943.672548.913210005.32544.266410025.68545.664710046.03550.305610086.39556.5995
10106.48557.233210136.53561.960610166.54563.985610176.57567.190110186.63572.5146
10216.86593.642610226.97596.818210247.19597.906110307.87605.804410329.35616.3936
#Mann= 3 , 0 , 0
9684.987    0.12       09684.987    0.12       010329.35    0.12       0
#XS Ineff= 2 , 0
       0                               0
Bank Sta=9684.987,10329.35
Exp/Cntr=0.3,0.1

Type RM Length L Ch R = 1 ,11118.14,246.915200,246.915200,246.915200
XS GIS Cut Line= 6
495894.809588313 809612.31968526495835.266430036809683.816733839
495743.429067293809770.043820276495665.859727479809816.010889572
495516.578192583809941.061238189495411.121658127809993.377702244
#Sta/Elev= 30
9721.746724.13619844.624614.7811 9872.07588.25299902.615560.73459925.589552.2455
9938.813550.48189951.181550.22959963.389548.04179975.598543.8167   10001543.1129
10031.42543.894810045.76549.960710058.97549.656710091.08553.301910111.82552.9508
10121.69554.433710125.03555.478410138.24562.875710151.45568.189210164.66576.9588
10190.85579.7586 10203.3579.793310239.83582.0062 10263.3583.678110274.97585.3458
 10297.3593.112710308.21599.063210319.01601.2534 10329.8607.655110344.39613.9534
#Mann= 3 , 0 , 0
9721.746    0.12       09721.746    0.12       010344.39    0.12       0
#XS Ineff= 2 , 0
       0                               0
Bank Sta=9721.746,10344.39
Exp/Cntr=0.3,0.1

Type RM Length L Ch R = 1 ,10871.22,246.915200,246.915200,246.915200
XS GIS Cut Line= 6
495612.255668401809328.603268387495566.958035305809475.019785825
495488.554643986809681.491053319495383.635408107809874.485348785
495322.707894406809957.734359592495291.751082996809985.668676547
#Sta/Elev= 30
9576.348722.78139603.846705.3962 9645.56675.61189656.065670.02669677.077655.7948
9740.203601.0607  9761.4 598.1299793.195584.51349814.392585.78229836.657582.8157
9857.021 575.1949867.743565.34339899.911549.33069921.573543.34149932.523 542.404
9988.211542.689910010.65548.296210022.08547.545110044.14552.700910067.86552.5509
 10102.2558.113610125.09568.099710147.98 580.28810182.87586.887910194.84591.3457
10206.81 593.248 10244.1 610.52910284.32 625.42410298.41628.903410315.34637.4745
#Mann= 3 , 0 , 0
9576.348    0.12       09576.348    0.12       010315.34    0.12       0
#XS Ineff= 2 , 0
       0                               0
Bank Sta=9576.348,10315.34
Exp/Cntr=0.3,0.1

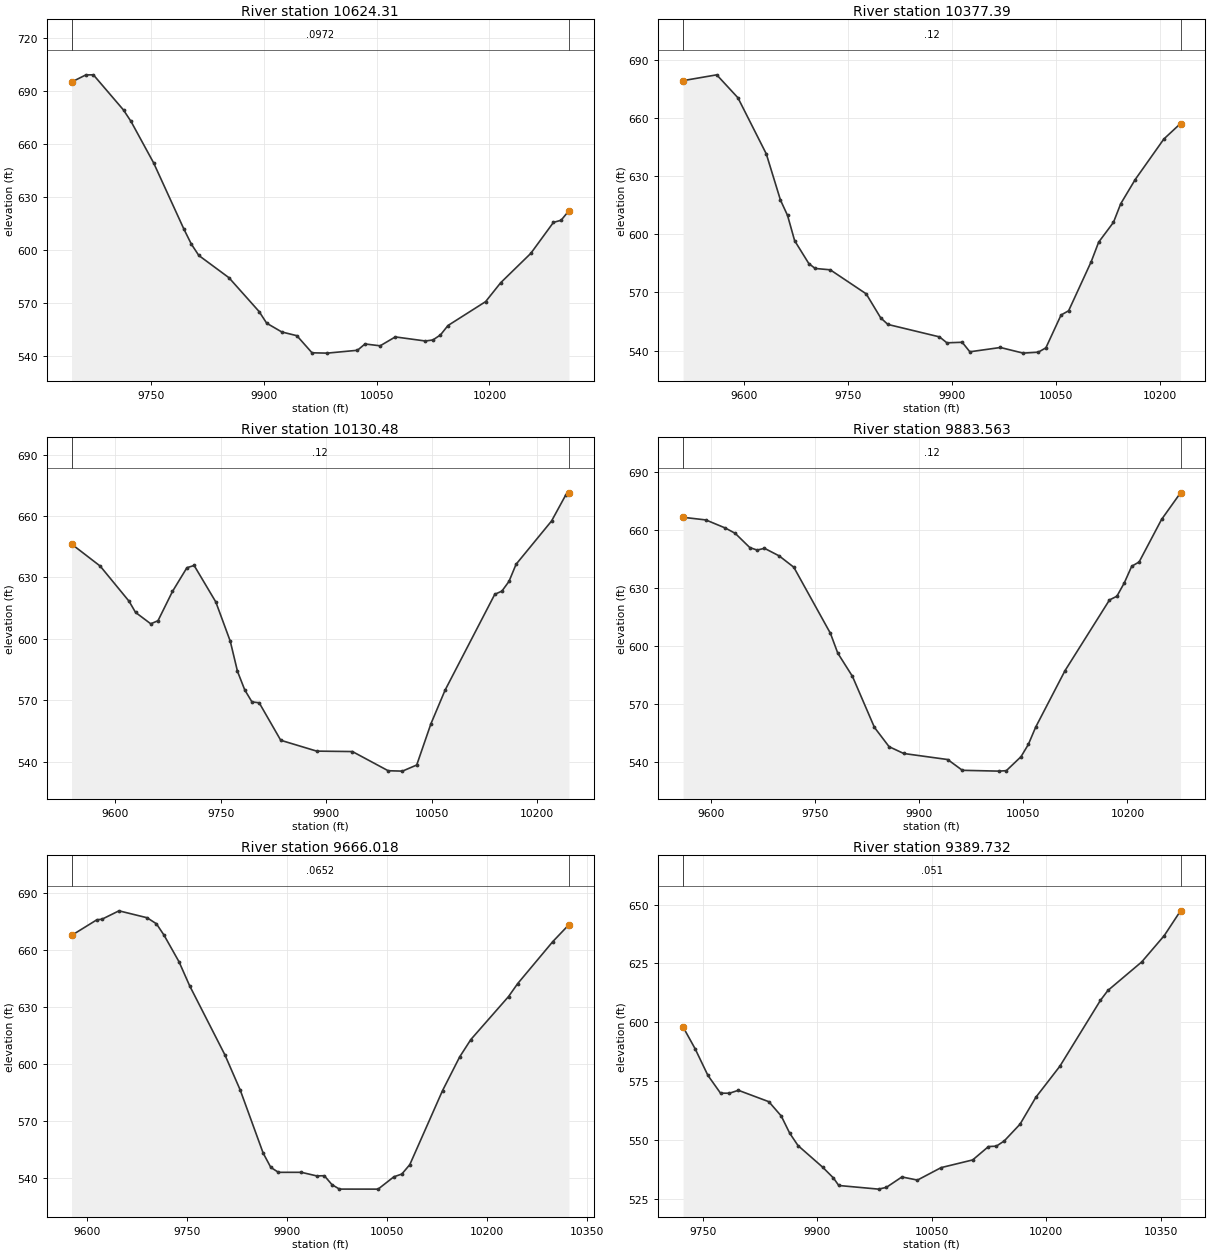
Type RM Length L Ch R = 1 ,10624.31,246.915200,246.915200,246.915200
XS GIS Cut Line= 6
495264.071741992  809275.9708144495256.210916607809479.242035416
495234.808785435809702.870944766495235.421746109 809835.87983747
495232.200822733809903.580190586495227.477063871809935.367270288
#Sta/Elev= 30
9644.644694.96499663.682699.01479673.686699.05789713.714679.13459723.722672.6442
9753.748649.18699793.782611.8849 9803.79603.27199813.799596.78479853.842584.1912
9893.941565.03119903.965558.44699924.015553.48389944.104 551.361 9964.23541.6783
9984.357541.4936 10024.6543.108410034.66546.684310054.79545.6373 10074.9550.6743
10114.91548.360110124.92548.949910134.92551.798610144.92557.120610194.93570.6488
10214.94 581.34110254.98597.967810285.11615.5351 10295.2616.700210305.73622.1597
#Mann= 3 , 0 , 0
9644.644  0.0972       09644.644  0.0972       010305.73  0.0972       0
#XS Ineff= 2 , 0
       0                               0
Bank Sta=9644.644,10305.73
Exp/Cntr=0.3,0.1

Type RM Length L Ch R = 1 ,10377.39,246.915200,246.915200,246.915200
XS GIS Cut Line= 6
494897.568869908809267.211183279494933.793848763809449.185466889
494964.956290959 809561.98143326494991.328929037809633.765611718
495086.811503428809850.806988361 495111.75718768 809948.64708646
#Sta/Elev= 30
9511.905679.12349560.398682.11859590.954670.30419631.853641.40419652.303617.5886
9662.528609.66779672.753 596.6529693.203584.86189702.366582.33169724.122 581.635
9775.954569.25079796.814556.89769807.244553.48129881.663 547.0649892.362544.0104
 9914.41544.29289925.434 539.384 9969.53541.6014 10002.3538.696810024.16  539.19
10035.09541.422310056.96558.327110067.89560.532510100.46585.8359 10111.2595.8848
10132.56606.1122   10143615.6636 10163.9628.155810205.23 649.04510229.29657.0281
#Mann= 3 , 0 , 0
9511.905    0.12       09511.905    0.12       010229.29    0.12       0
#XS Ineff= 2 , 0
       0                               0
Bank Sta=9511.905,10229.29
Exp/Cntr=0.3,0.1

Type RM Length L Ch R = 1 ,10130.48,246.915300,246.915300,246.915300
XS GIS Cut Line= 6
494693.950072877809315.339262568494755.864814236809574.484391179
494775.846630501 809667.93231741494799.090317605809797.557279977
494826.108217567809990.549866279494828.239287313810009.618677941
#Sta/Elev= 30
9537.749646.30189578.494635.53879619.625618.33429628.788612.91069650.474607.3219
9660.757608.83139681.323623.11949701.889 634.7319712.172 635.8259743.021617.9964
9763.587598.8077 9773.87584.08169784.153575.04419794.436569.15989804.716 568.737
9835.394550.41029886.524545.10939937.414544.89149988.221535.523310008.55535.3301
10028.85538.319610049.06558.461310069.25574.926310139.93621.741310150.03623.2988
10160.13628.042910170.23636.418310220.71657.567310240.86670.2562 10245.5671.3311
#Mann= 3 , 0 , 0
9537.749    0.12       09537.749    0.12       0 10245.5    0.12       0
#XS Ineff= 2 , 0
       0                               0
Bank Sta=9537.749,10245.5
Exp/Cntr=0.3,0.1

Type RM Length L Ch R = 1 ,9883.563,217.545000,217.545000,217.545000
XS GIS Cut Line= 6
 494416.17358466809413.771556714494423.309840399809436.720442632
494555.957932091809831.668758896494589.576383296809931.262151754
494631.357018634810043.966181697494650.430831408810090.243217551
#Sta/Elev= 30
9560.338666.46059593.105665.09589621.086660.91849635.301658.17289656.399650.7794
9666.948649.49629677.497650.41189698.595646.49479719.693640.62269772.438606.3782
9782.987596.15329804.085584.15499835.732557.7452 9856.83547.74339877.928544.2169
9941.222541.0857 9962.32535.510310015.07535.090410025.62535.332510046.73542.5611
10057.29548.905410067.84557.8515 10110.1587.107510174.09623.688710184.76625.6188
10195.42632.526510206.09641.127410216.75 643.34310249.06665.364410276.37679.1266
#Mann= 3 , 0 , 0
9560.338    0.12       09560.338    0.12       010276.37    0.12       0
#XS Ineff= 2 , 0
       0                               0
Bank Sta=9560.338,10276.37
Exp/Cntr=0.3,0.1

Type RM Length L Ch R = 1 ,9666.018,276.285400,276.285400,276.285400
XS GIS Cut Line= 6
494155.262769163809540.844388113494227.807117424809686.008277398
494355.065231601809912.622018194494416.332727482810010.607615205
494474.420683734 810078.19762504494563.397659306810157.005496749
#Sta/Elev= 30
9577.323667.47579615.199675.67519622.993676.00529648.466680.40459690.659676.7652
9704.593 673.5959715.893667.69129738.494653.63279754.324641.09879807.288604.7231
9830.226586.26949864.632553.1384  9876.1 545.6119887.569543.01289921.975543.0191
9944.912541.13599956.381541.23069967.849 536.5339978.994 534.20610036.98534.1873
10060.64540.660610072.59542.116510084.54547.058810133.62585.9608 10159.3 603.651
10176.07612.7885 10232.6635.375210246.34642.194210299.01664.259510323.22673.1657
#Mann= 3 , 0 , 0
9577.323  0.0652       09577.323  0.0652       010323.22  0.0652       0
#XS Ineff= 2 , 0
       0                               0
Bank Sta=9577.323,10323.22
Exp/Cntr=0.3,0.1

Type RM Length L Ch R = 1 ,9389.732,246.915200,246.915200,246.915200
XS GIS Cut Line= 6
493905.080612121809975.564077228493969.826031406810019.137998498
494078.359413767810067.414458062494335.820775854810133.753366545
494394.424127769810152.830911855494510.306041191810204.879087167
#Sta/Elev= 30
9724.143597.96149739.916588.71559756.632577.4292 9773.17569.86519784.891569.8365
9796.612571.08029836.506566.23919852.779560.1536 9863.75552.91279874.721547.6002
9906.884538.46059921.187533.81789928.135 530.6389980.249529.09589990.463529.8392
10010.86534.267810031.25532.941610062.27538.237810103.63541.502210124.31547.1832
10134.65547.353410144.99549.577510165.67556.690710186.35568.096610217.89581.3265
10271.08609.3322 10280.8613.499210325.15625.632810354.57636.775410375.98647.3267
#Mann= 3 , 0 , 0
9724.143   0.051       09724.143   0.051       010375.98   0.051       0
#XS Ineff= 2 , 0
       0                               0
Bank Sta=9724.143,10375.98
Exp/Cntr=0.3,0.1

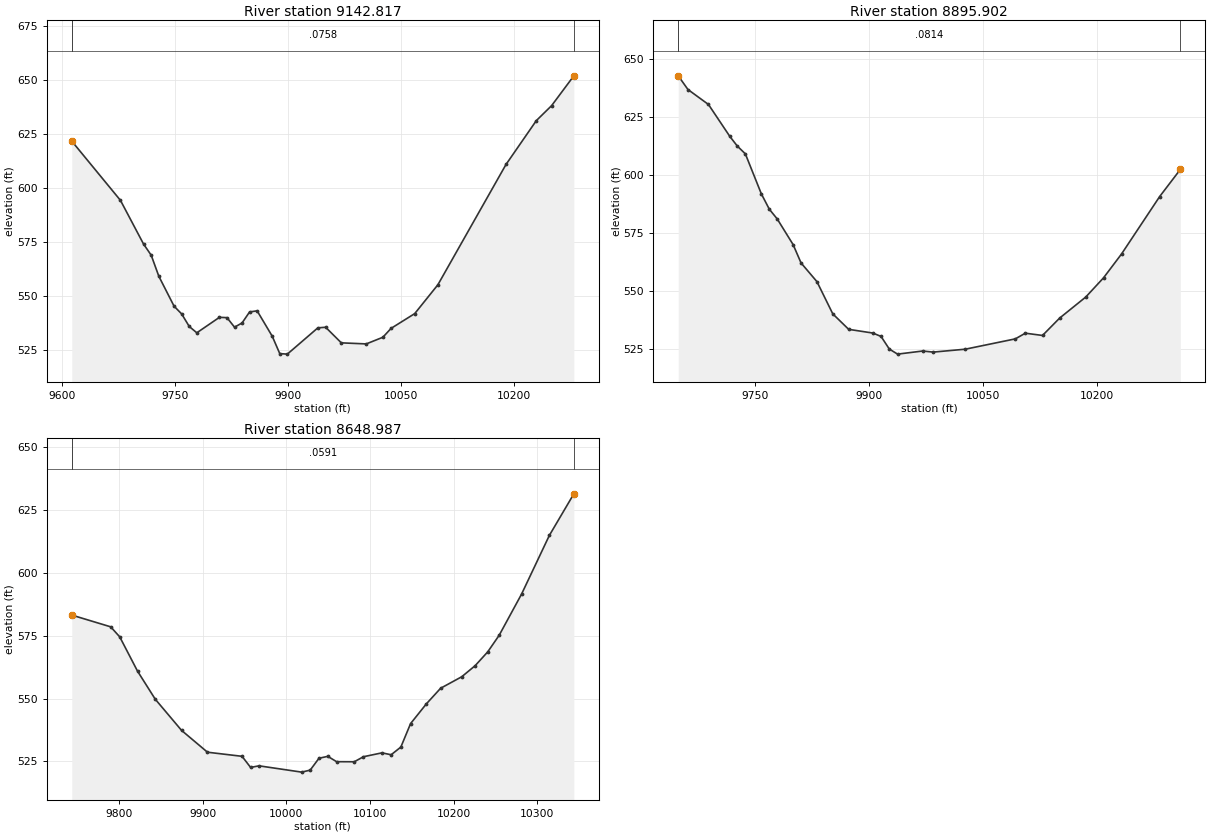
Type RM Length L Ch R = 1 ,9142.817,246.915200,246.915200,246.915200
XS GIS Cut Line= 6
493843.627993711810307.408216659493965.850753884810339.062082572
494073.746417294810346.007844417494159.568845626810338.042805358
494343.880906475810280.809299952494493.488824848810295.433329028
#Sta/Elev= 30
9612.669621.76439677.324594.31249707.944574.10069718.107568.92359728.269559.1453
9748.499545.29599758.558541.71989768.617535.91139778.675532.97779808.714540.1486
 9818.72539.99629828.726535.58079838.732537.53559848.739542.64389858.752543.1512
9878.778531.4042 9888.79523.33549898.845523.09959939.369535.27769949.687535.5438
9970.509528.323910003.61527.830410025.63530.907210036.59535.036810067.95 541.869
 10098.7555.227310189.13610.951710229.37 631.25510249.71638.213110279.19652.0105
#Mann= 3 , 0 , 0
9612.669  0.0758       09612.669  0.0758       010279.19  0.0758       0
#XS Ineff= 2 , 0
       0                               0
Bank Sta=9612.669,10279.19
Exp/Cntr=0.3,0.1

Type RM Length L Ch R = 1 ,8895.902,246.915200,246.915200,246.915200
XS GIS Cut Line= 6
 493823.86045105 810417.19292616 493868.91324543 810439.17232221
494110.334190869810521.604754273 494301.87066159810621.121026097
494349.868283721810650.015899331494414.709498537810702.751238372
#Sta/Elev= 30
9648.934642.82479661.722 636.9289688.746630.47159716.841616.72459726.746612.5375
9737.335609.18739758.416591.92179768.866585.33879779.315 581.1239800.215 570.073
9810.664562.17229831.563554.11949852.462540.21419873.388533.55489905.293531.9496
9916.012530.49279926.883525.05889937.755522.87069970.766524.20889984.793 523.749
10026.86524.993310092.84529.449310105.99531.8959 10128.6530.918110151.21538.4172
10185.61547.493910208.95555.750810232.66566.031310282.88 590.78710310.07602.4621
#Mann= 3 , 0 , 0
9648.934  0.0814       09648.934  0.0814       010310.07  0.0814       0
#XS Ineff= 2 , 0
       0                               0
Bank Sta=9648.934,10310.07
Exp/Cntr=0.3,0.1

Type RM Length L Ch R = 1 ,8648.987,246.915200,246.915200,246.915200
XS GIS Cut Line= 6
493843.962222133 810699.15161166493950.044901662810744.728119709
494115.258020762810782.306183118494205.674973735810817.791375813
494301.071229001810887.554467978494360.002129238810966.855779901
#Sta/Elev= 30
9743.321583.23549789.837578.56119800.682574.55719821.917560.92929843.152549.7419
 9874.58537.33559905.582 528.6419946.917527.00719957.141522.58799967.318523.2164
10018.21520.711910028.39521.506710038.91526.229910049.43526.998110059.96524.8666
10081.11524.842210092.13526.846410114.19528.383810125.21 527.632 10136.8530.6852
10148.44540.034910167.32547.896610184.33554.100110209.61558.683710225.64563.0942
10240.68568.591710254.36575.195710281.11591.570910314.37614.955410343.65631.5111
#Mann= 3 , 0 , 0
9743.321  0.0591       09743.321  0.0591       010343.65  0.0591       0
#XS Ineff= 2 , 0
       0                               0
Bank Sta=9743.321,10343.65
Exp/Cntr=0.3,0.1