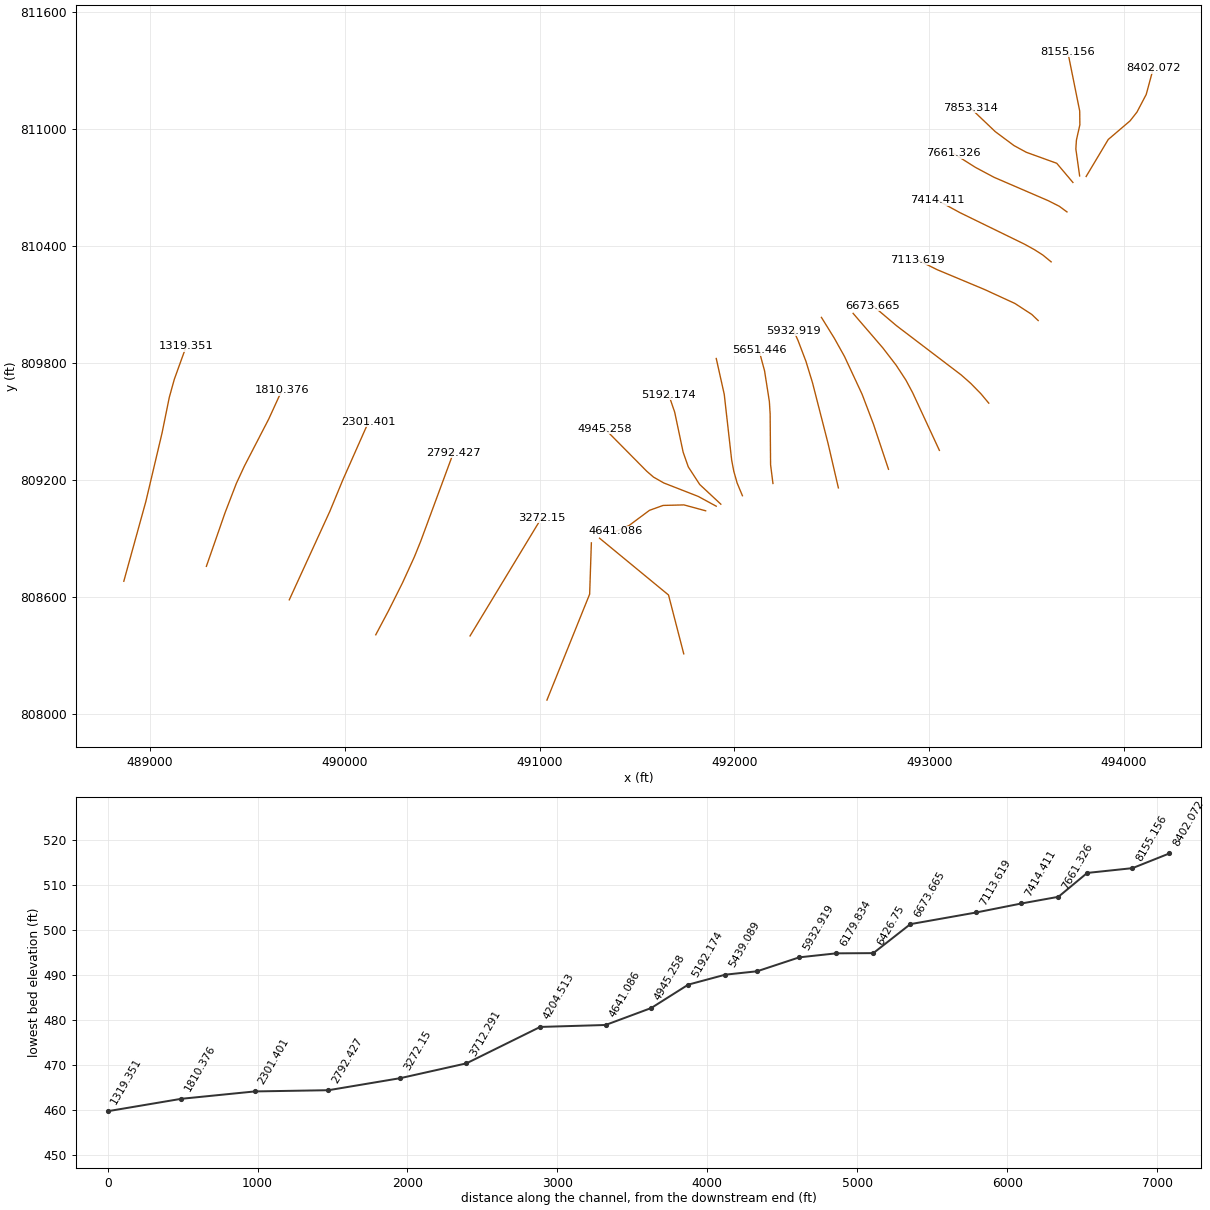
HEC-RAS study 5238_ras.prj: 5238

--- 5238_ras.g01 (geometry) --- (continued)

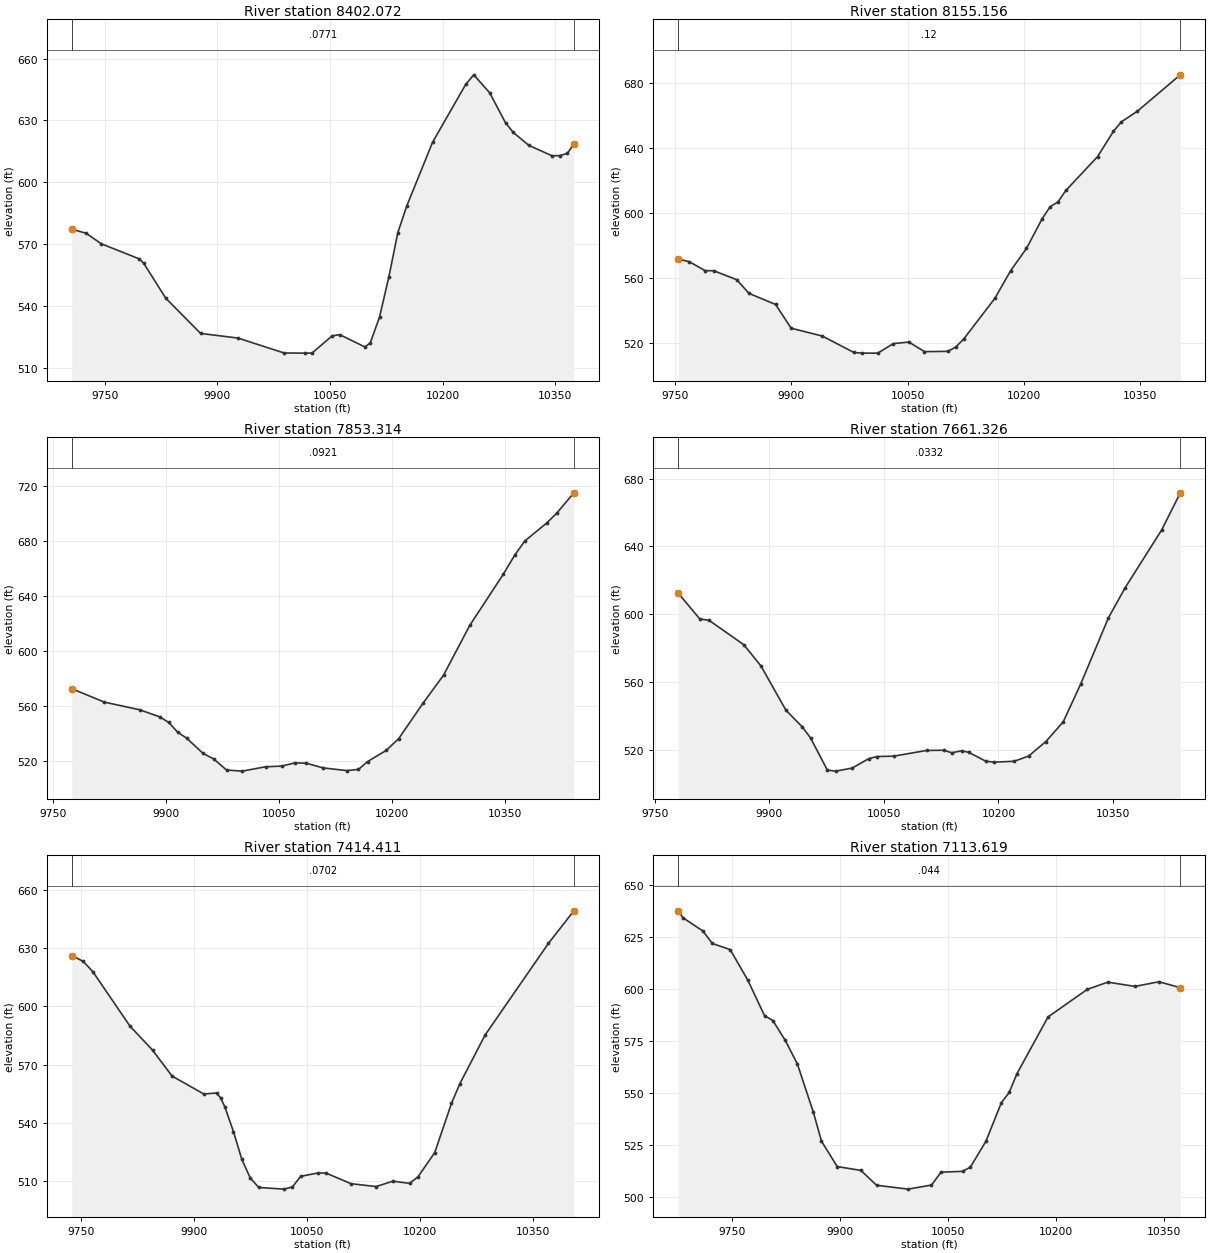
Type RM Length L Ch R = 1 ,8402.072,246.915300,246.915300,246.915300
XS GIS Cut Line= 6
493805.753328945810757.938418715 493919.21165926810947.812339053
494031.259222264811043.420322867 494066.74242605811088.579526389
494114.282762674811179.228684205494150.544950102811313.547376923
#Sta/Elev= 30
9706.048577.2566 9725.19575.24789745.328570.16249795.861562.83929801.968560.6446
9831.208543.74819877.626526.68059927.307524.43389988.826517.1913 10017.2 517.127
10025.86517.138510052.82525.524210062.83526.071710096.36520.139810103.43522.0475
10115.81534.596510128.17553.989610140.14575.509910151.88588.311310186.39 619.365
 10230.5647.416210241.26652.090110262.51643.352910283.56 628.81510293.88624.1506
10314.52617.897810345.49612.820910355.74 612.91410365.87 613.99610374.52618.5664
#Mann= 3 , 0 , 0
9706.048  0.0771       09706.048  0.0771       010374.52  0.0771       0
#XS Ineff= 2 , 0
       0                               0
Bank Sta=9706.048,10374.52
Exp/Cntr=0.3,0.1

Type RM Length L Ch R = 1 ,8155.156,301.842200,301.842200,301.842200
XS GIS Cut Line= 6
493772.355765112810760.706309739493752.858367383  810899.3622359
493755.862095675810945.006417735 493773.55019068811023.203717559
493772.708775825811093.862389175493711.166233404811399.048100179
#Sta/Elev= 30
9753.767571.80579768.191570.13229788.484564.63219799.618564.59849829.152559.1138
9845.189550.63969879.526543.81069899.585 529.2019939.672524.39449980.543  514.28
 9990.89513.850810011.49513.852110031.71 519.73910051.74520.656310071.81514.7726
   10102514.9359 10112.1 517.56710122.21522.3762 10162.8547.654110183.16564.6741
10203.51578.324710223.87596.709210234.05603.970210244.23607.006310254.41614.0373
10295.31634.852710315.86650.470110326.13656.278310346.68662.822810402.22685.2508
#Mann= 3 , 0 , 0
9753.767    0.12       09753.767    0.12       010402.22    0.12       0
#XS Ineff= 2 , 0
       0                               0
Bank Sta=9753.767,10402.22
Exp/Cntr=0.3,0.1

Type RM Length L Ch R = 1 ,7853.314,191.988200,191.988200,191.988200
XS GIS Cut Line= 6
493737.787195259810727.255253444 493654.73852547810825.672409595
493498.492732749810882.123886209493435.160597879810916.673992571
493339.219582751810988.092716417493209.686662803811111.360345198
#Sta/Elev= 30
9774.621572.7628 9818.02562.97949864.712557.45069891.477552.29319903.537548.1869
9915.753540.92289927.192 536.8759949.024525.72219963.277521.65189980.444513.5689
 10001.1512.787810032.36515.952410053.62516.430710071.39518.797410086.46518.5315
10108.93515.128610140.29513.163710155.83514.053110167.88519.743110192.57527.8028
10209.35536.495510241.93562.430410268.89582.604510303.81618.854510348.22655.9292
10363.65670.0216 10377.1680.279610405.95693.258210419.25700.342210442.14715.2471
#Mann= 3 , 0 , 0
9774.621  0.0921       09774.621  0.0921       010442.14  0.0921       0
#XS Ineff= 2 , 0
       0                               0
Bank Sta=9774.621,10442.14
Exp/Cntr=0.3,0.1

Type RM Length L Ch R = 1 ,7661.326,246.915200,246.915200,246.915200
XS GIS Cut Line= 6
493707.343251865810576.031602396493667.319754674810605.205548008
493610.312166487810634.015429522493332.102665414810754.035328146
493236.596264836810805.053613691493124.746913926810875.922147595
#Sta/Elev= 30
9780.851 612.3959809.118597.22389821.187596.43989866.669582.05229889.078569.5513
9921.779543.45759943.467533.44369954.311526.85119975.999 508.1139986.843507.4826
10008.58509.273210030.25514.849910041.09516.098110062.76516.3089 10106.1519.6855
10128.12519.798710139.13518.321510151.87519.488410161.15518.559210183.17 513.386
10194.18512.766810220.64513.301610239.43516.356310262.11524.935510284.78536.5281
10307.52 558.66910344.06597.963610366.02615.747310413.69649.740510438.09671.6283
#Mann= 3 , 0 , 0
9780.851  0.0332       09780.851  0.0332       010438.09  0.0332       0
#XS Ineff= 2 , 0
       0                               0
Bank Sta=9780.851,10438.09
Exp/Cntr=0.3,0.1

Type RM Length L Ch R = 1 ,7414.411,300.792000,300.792000,300.792000
XS GIS Cut Line= 6
493626.073731259810319.538641809493582.717329638810355.089013638
493539.778573611810382.475470487493488.713350981810410.675825672
493157.670814993810572.263195673493041.947313063810635.504029389
#Sta/Elev= 30
9738.059626.20869753.226623.19279765.912617.94979815.194 589.8979845.108577.5514
9871.016564.17999913.058554.96139929.993555.47119935.293553.03759941.189548.1615
9952.385535.63699963.581521.24659974.777   511.79985.974506.858310019.46505.9983
10030.56507.133210041.67512.597810063.87514.270410074.97514.292610108.27508.7958
10141.58507.327510163.78510.086510185.98508.959210197.08512.344210219.29524.7871
10241.49  550.1610252.59560.264610286.19585.388910369.98632.443110403.72649.2106
#Mann= 3 , 0 , 0
9738.059  0.0702       09738.059  0.0702       010403.72  0.0702       0
#XS Ineff= 2 , 0
       0                               0
Bank Sta=9738.059,10403.72
Exp/Cntr=0.3,0.1

Type RM Length L Ch R = 1 ,7113.619,439.953700,439.953700,439.953700
XS GIS Cut Line= 6
493559.463692524810018.169484455493526.734787308810049.509625974
493440.249620359810105.798816873493284.682958429810177.381801888
 493040.54222739810279.498302158492938.805286092810329.987766773
#Sta/Elev= 30
9674.838637.74529681.365634.42129709.125628.04099722.345622.0447 9747.12619.1003
9771.615604.4178 9794.81587.39689806.408 585.0279823.515575.58599840.543564.1216
9862.876540.84829874.042527.02539895.987514.8406 9928.81512.99529950.692 505.871
 9994.45504.004210027.02505.968610040.41512.162510070.24512.541510081.04514.5682
10102.65526.962610124.25545.580810135.06550.470710145.86559.463410189.13586.7579
10243.68599.999510272.21603.471810309.92601.418510343.35603.659710373.05 600.811
#Mann= 3 , 0 , 0
9674.838   0.044       09674.838   0.044       010373.05   0.044       0
#XS Ineff= 2 , 0
       0                               0
Bank Sta=9674.838,10373.05
Exp/Cntr=0.3,0.1

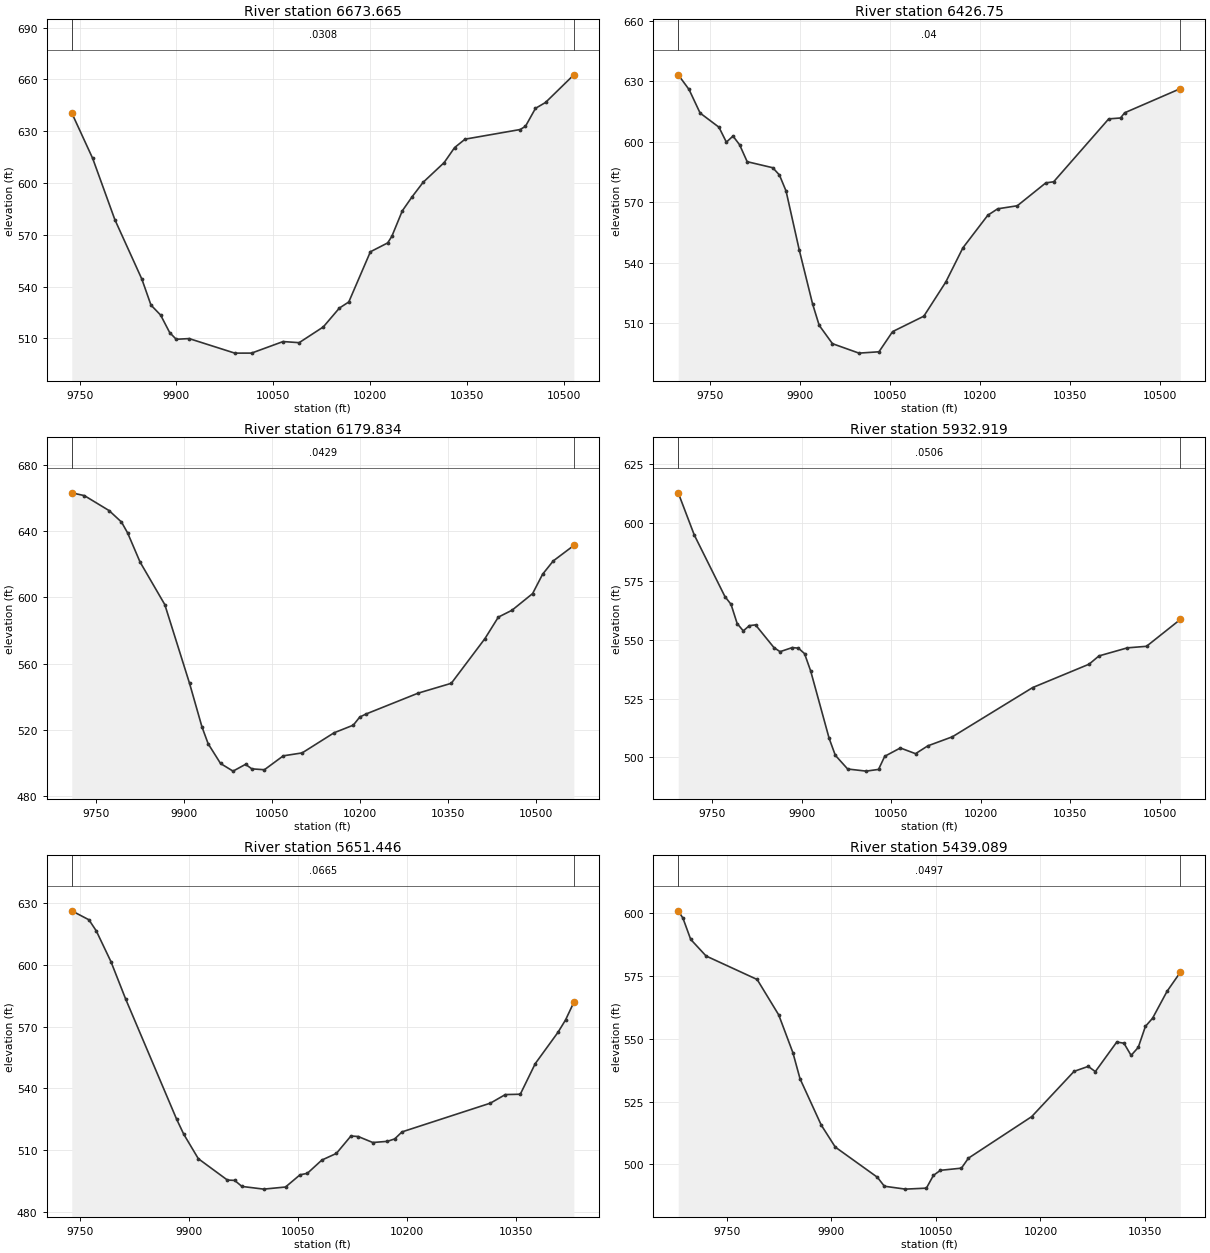
Type RM Length L Ch R = 1 ,6673.665,246.915200,246.915200,246.915200
XS GIS Cut Line= 6
493305.784643974809594.017913563 493265.63797353809642.102391922
493213.061428471809695.720026516 493164.52617754809738.647754077
492831.228189683 809992.31511423492711.708891352810093.645247331
#Sta/Elev= 30
9737.718640.59739770.148614.24039804.417578.82659846.433544.22049860.439529.2684
9875.453523.4437 9889.46513.32349899.565 509.4389919.648509.83339990.408 501.408
10016.37501.422110065.19508.113610090.13507.470410127.54516.591310152.48 527.531
10167.03531.054810200.51560.138610227.31565.275810233.75569.087910249.97583.8642
10265.42592.1464 10282.4600.462810314.83611.820510331.05620.534410347.27625.4038
10432.67630.989510440.87632.864110456.38643.2686 10471.9646.652910515.83662.6858
#Mann= 3 , 0 , 0
9737.718  0.0308       09737.718  0.0308       010515.83  0.0308       0
#XS Ineff= 2 , 0
       0                               0
Bank Sta=9737.718,10515.83
Exp/Cntr=0.3,0.1

Type RM Length L Ch R = 1 , 6426.75,246.915200,246.915200,246.915200
XS GIS Cut Line= 6
493052.228769591 809351.60958769492914.535487694809648.443552416
492880.230079726809712.496918044492830.609542227809788.338156438
492761.268427751809878.406629732492609.405071464810054.885147834
#Sta/Elev= 30
 9696.64633.30329714.654626.01519733.095614.30319764.493607.27879776.891599.8396
9787.944602.86439798.997598.51519811.567 590.1269854.261 587.1199865.314583.5243
9876.366575.57849898.472546.14829920.578519.4737 9931.63508.78649953.736499.6707
9997.947494.968410031.31495.6363   10054505.661310106.09513.330910142.62530.2762
10171.23547.312410212.76563.520510229.15566.697510261.94 568.22410309.46579.6045
10322.54 580.14210414.32611.404210433.97  611.8510440.88614.436810533.67626.4307
#Mann= 3 , 0 , 0
 9696.64    0.04       0 9696.64    0.04       010533.67    0.04       0
#XS Ineff= 2 , 0
       0                               0
Bank Sta=9696.64,10533.67
Exp/Cntr=0.3,0.1

Type RM Length L Ch R = 1 ,6179.834,246.915200,246.915200,246.915200
XS GIS Cut Line= 6
492790.921948325809254.457051582492713.358881511809487.193004461
492655.753834547809638.802653285 492565.40994853809832.998452098
492512.389350143809928.033545843 492446.48919684  810034.5206635
#Sta/Elev= 30
9709.103663.20879730.617661.51699772.753652.46469793.854645.53779804.405638.8968
9825.507621.3671 9867.71595.60019909.913547.93549931.015 521.6879941.565 511.487
9962.735499.5356 9984.01494.922510005.32499.031110016.05496.294710037.49495.7684
10069.66504.172510101.82 505.943 10156.2518.1038   10189522.725710199.93527.6066
10210.86529.488410299.52542.079710356.06548.039110413.32575.037310436.22588.0508
10459.55592.217810494.65602.288310511.69613.995610529.79622.016310564.93631.3883
#Mann= 3 , 0 , 0
9709.103  0.0429       09709.103  0.0429       010564.93  0.0429       0
#XS Ineff= 2 , 0
       0                               0
Bank Sta=9709.103,10564.93
Exp/Cntr=0.3,0.1

Type RM Length L Ch R = 1 ,5932.919,281.473000,281.473000,281.473000
XS GIS Cut Line= 6
492533.630665323809158.797472001492480.512291803809387.625835984
 492400.75943709809698.812023335 492367.21585105809808.344469847
492326.429786764809915.772125529492303.659948823809966.737148658
#Sta/Elev= 30
9692.675612.81849719.574 594.8129770.904568.5562 9781.17565.22229791.435557.0192
9801.701 553.8939811.967556.13599822.233556.45299853.031546.78289863.297545.0182
9883.828546.77099894.094546.5222 9904.36544.18449914.626536.78879945.563508.0443
9955.909500.8061  9976.6494.945110007.66494.033710028.38 494.76610038.75500.3664
10064.89503.916410090.38 501.48610110.99504.8245 10152.2 508.69710286.69529.7024
10381.22539.675810397.82543.209310445.39546.650810477.48547.310810534.13558.7685
#Mann= 3 , 0 , 0
9692.675  0.0506       09692.675  0.0506       010534.13  0.0506       0
#XS Ineff= 2 , 0
       0                               0
Bank Sta=9692.675,10534.13
Exp/Cntr=0.3,0.1

Type RM Length L Ch R = 1 ,5651.446,212.357400,212.357400,212.357400
XS GIS Cut Line= 6
492197.682860781809181.652900158492185.465963193809278.014026681
492183.214775164809538.917230813492179.182427461809602.956793289
492154.579447966809760.043413049 492125.99462135809865.953748876
#Sta/Elev= 30
9738.436 626.3269762.083621.95869772.195616.55589792.372601.59979812.475583.5432
9882.632525.07369892.641517.61089912.657505.73229952.664495.35029962.665495.1754
9972.666492.247710002.67490.934510032.67491.962810052.68497.910710062.68498.6068
10082.68505.070810102.69508.304710122.73516.780810132.75516.528410152.79513.6172
 10172.9514.181910182.97515.364810193.05518.782310314.72532.769710335.26536.9333
10355.87537.102410376.47552.004310407.68567.191810418.13573.229910429.58581.8328
#Mann= 3 , 0 , 0
9738.436  0.0665       09738.436  0.0665       010429.58  0.0665       0
#XS Ineff= 2 , 0
       0                               0
Bank Sta=9738.436,10429.58
Exp/Cntr=0.3,0.1

Type RM Length L Ch R = 1 ,5439.089,246.915200,246.915200,246.915200
XS GIS Cut Line= 6
492040.820118712 809118.87744199492013.731649961809184.111683614
491996.818688867809243.359643476491985.719658402809301.322419062
 491947.51711983809639.704459417491906.515524999809823.348073487
#Sta/Elev= 30
 9680.52600.93839687.301 598.0039698.376589.5838 9720.46582.96279793.709573.6138
9824.654559.51569845.018544.46199855.199534.11819885.605 515.6939905.764 506.919
9966.147494.90899976.191491.336710006.32  490.1810036.47490.572210046.52  495.64
10056.57497.663510086.72498.526610096.76502.505210187.46519.024310248.28537.0464
10268.61539.025710278.79536.953610309.57548.735310319.83548.246110330.09543.3999
10340.35546.5892 10350.6554.936710360.88558.194110381.64 568.89410400.68576.4807
#Mann= 3 , 0 , 0
 9680.52  0.0497       0 9680.52  0.0497       010400.68  0.0497       0
#XS Ineff= 2 , 0
       0                               0
Bank Sta=9680.52,10400.68
Exp/Cntr=0.3,0.1

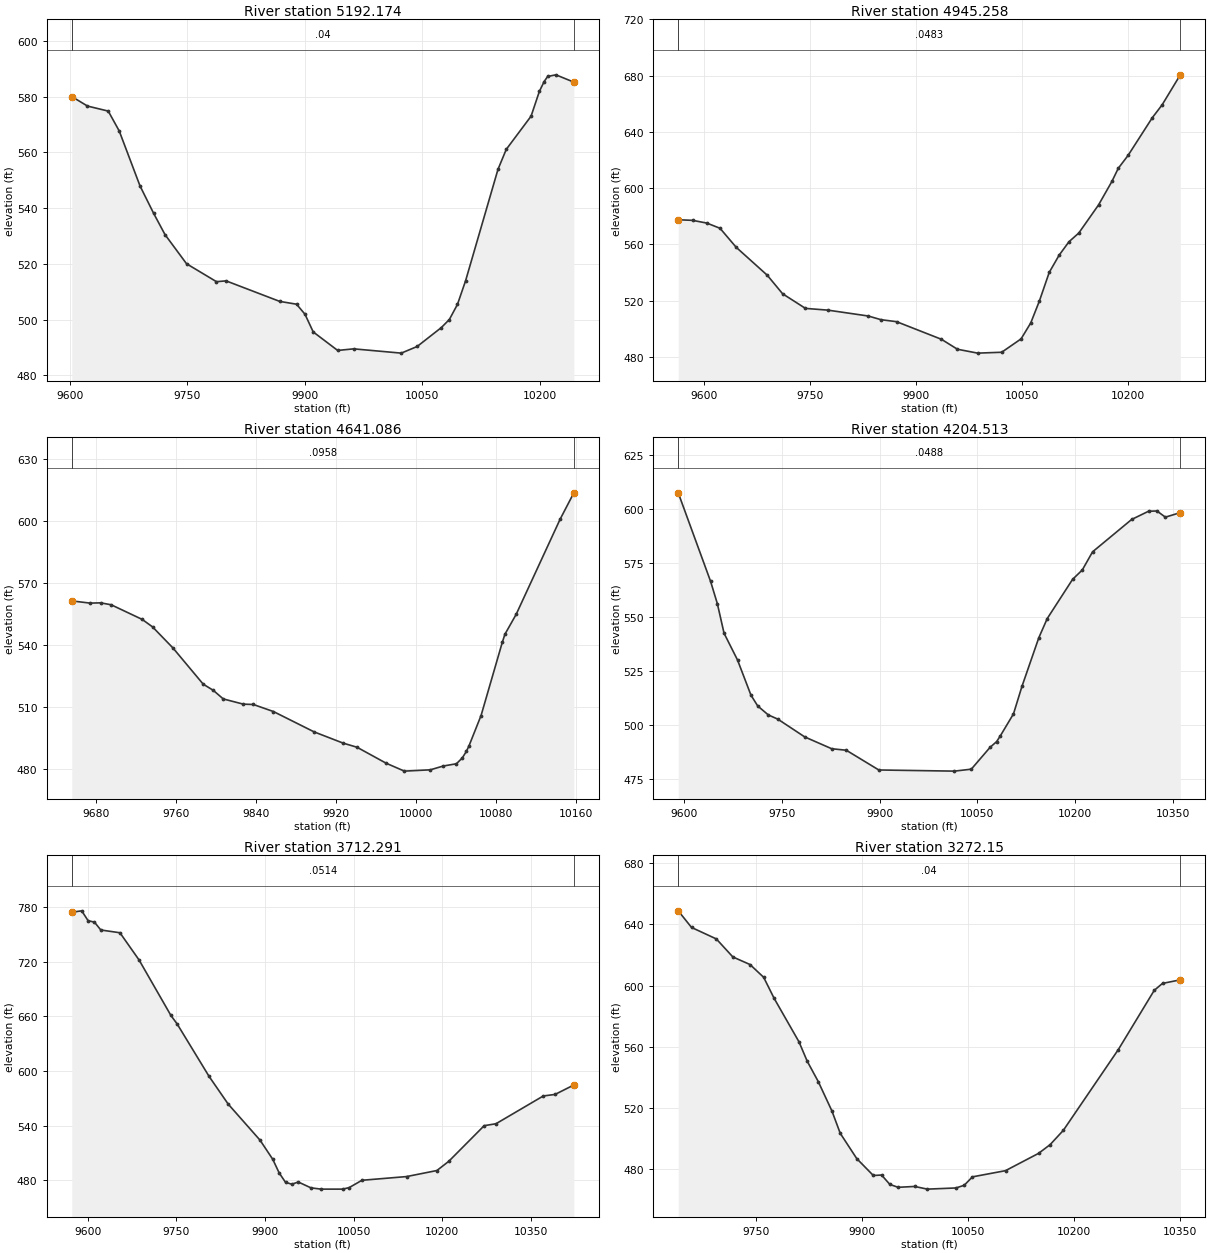
Type RM Length L Ch R = 1 ,5192.174,246.915300,246.915300,246.915300
XS GIS Cut Line= 6
491930.147005617809075.292119629491821.654663773809176.435520853
491763.033510708809266.650590374491736.466844633809342.589017394
491693.093342611809547.890515273  491662.6940173809636.650314154
#Sta/Elev= 30
9602.773580.05239622.832576.64139649.317574.83739663.344567.70389689.839547.9999
9707.248 538.1399721.792530.49869749.266520.04369787.452513.60789799.719513.8983
9868.121506.53579889.655505.52479900.422501.92769910.937495.57349942.137488.9273
9962.555489.499710023.32487.965410043.59 490.34710074.34497.107410084.68 500.026
10095.03505.448210105.38513.905910146.77553.930410157.28561.080310188.99573.0115
10199.56581.8821 10205.6585.405910210.13587.2534 10220.7587.851810243.58585.2231
#Mann= 3 , 0 , 0
9602.773    0.04       09602.773    0.04       010243.58    0.04       0
#XS Ineff= 2 , 0
       0                               0
Bank Sta=9602.773,10243.58
Exp/Cntr=0.3,0.1

Type RM Length L Ch R = 1 ,4945.258,304.172400,304.172400,304.172400
XS GIS Cut Line= 6
491906.331831606809064.962646563491814.014912956  809115.2063534
 491637.11184493809184.294478265491584.306710483809214.478998961
 491549.91967427809244.177615825491333.137572807 809463.39085987
#Sta/Elev= 30
9564.063577.54119584.329577.12439604.519575.17979623.151571.48289645.998557.9793
9689.887538.14319711.632524.94489743.936514.55819775.765513.31569832.705  509.15
9850.742506.53189872.775505.11689936.172492.60229958.799485.53559987.344482.7723
10021.37483.391510048.74492.887410062.45504.248210074.62519.769210088.56540.1367
 10102.5552.333110116.44561.901810130.38568.117410158.26588.068210177.28604.8662
10186.14614.078310200.08623.300210234.21650.002210248.19659.209510273.88680.5267
#Mann= 3 , 0 , 0
9564.063  0.0483       09564.063  0.0483       010273.88  0.0483       0
#XS Ineff= 2 , 0
       0                               0
Bank Sta=9564.063,10273.88
Exp/Cntr=0.3,0.1

Type RM Length L Ch R = 1 ,4641.086,436.573200,436.573200,436.573200
XS GIS Cut Line= 6
491852.060706269809041.423363282491740.888757592809071.566370097
491633.412861787809068.913141297491563.494359799809043.667646613
491459.064257907 808965.90114137491392.128704144808935.915459139
#Sta/Elev= 30
 9655.92561.42859674.133560.3644  9684.8560.48429695.281559.56089726.303 552.472
9736.643548.85549757.102538.61959787.318521.10369797.342 518.1389807.366513.9584
9827.394511.43679837.402511.2689 9857.49507.86349898.261497.9881 9927.22492.5608
9941.071490.56489970.206482.82689988.416479.0017 10014.3479.633910027.37481.4869
10040.44482.568210046.23485.361810050.35488.533810052.97491.206210065.06505.9217
10086.28 541.34910088.91545.278410100.18554.947510144.06600.958110157.81613.7625
#Mann= 3 , 0 , 0
 9655.92  0.0958       0 9655.92  0.0958       010157.81  0.0958       0
#XS Ineff= 2 , 0
       0                               0
Bank Sta=9655.92,10157.81
Exp/Cntr=0.3,0.1

Type RM Length L Ch R = 1 ,4204.513,492.221900,492.221900,492.221900
XS GIS Cut Line= 3
491739.600007236 808306.89578706491661.475007236808608.979120404
491307.308340579808900.645787075
#Sta/Elev= 30
9590.926607.56499640.613566.50849650.942 556.2259661.271542.48659681.929530.0883
9702.587513.78199712.916508.78439729.115504.63929743.903502.64739785.219494.4096
9826.535488.95119848.931488.24649898.839479.102510014.97478.567910040.88 479.476
10069.72489.607110079.75492.240210085.46 494.92610105.65505.121410118.61517.8213
10144.52540.394510157.47549.297410196.34567.4476 10211.3 571.81710227.03 580.211
10287.02595.210710312.93599.021810325.88599.151210338.84596.287710361.76598.3886
#Mann= 3 , 0 , 0
9590.926  0.0488       09590.926  0.0488       010361.76  0.0488       0
#XS Ineff= 2 , 0
       0                               0
Bank Sta=9590.926,10361.76
Exp/Cntr=0.3,0.1

Type RM Length L Ch R = 1 ,3712.291,440.140500,440.140500,440.140500
XS GIS Cut Line= 3
491037.115833312 808069.37896876491256.504053563808613.461755067
491265.279582411808876.727619395
#Sta/Elev= 30
9572.731774.13989589.575775.68369600.357764.89269611.139763.26279621.922754.6642
9654.269751.63899686.616721.84199740.528661.0134 9751.31 651.4449805.222594.0853
9837.569 563.728 9891.48524.17779913.045503.16679923.828488.3012 9934.61477.9329
9945.392475.84519956.175478.30849977.739471.85819994.917470.471510031.65470.4715
10042.43472.1692   10064480.171710139.47484.230710190.94490.873210210.95 500.937
10270.98540.053810290.99542.189310371.04572.634610391.05  574.3410422.79584.6856
#Mann= 3 , 0 , 0
9572.731  0.0514       09572.731  0.0514       010422.79  0.0514       0
#XS Ineff= 2 , 0
       0                               0
Bank Sta=9572.731,10422.79
Exp/Cntr=0.3,0.1

Type RM Length L Ch R = 1 , 3272.15,479.723500,479.723500,479.723500
XS GIS Cut Line= 2
490642.377785027808398.909675971491010.433340579809006.548564836
#Sta/Elev= 30
9639.991648.77939658.803637.93429693.878630.4479 9717.26618.68829741.562613.7359
9760.864605.40199775.717591.64569810.792563.35319822.483550.66769838.071537.4075
9857.373518.26879869.249503.59239892.631487.08239916.014476.08949927.706476.3815
9939.397470.26449951.088468.38069974.471468.93399992.486467.190610032.93467.9514
10044.62469.699910056.31475.195810103.08479.239710149.84490.5241 10166.2496.2205
10184.92505.566810262.71558.246110313.52596.892810325.21601.425210350.41603.7426
#Mann= 3 , 0 , 0
9639.991    0.04       09639.991    0.04       010350.41    0.04       0
#XS Ineff= 2 , 0
       0                               0
Bank Sta=9639.991,10350.41
Exp/Cntr=0.3,0.1

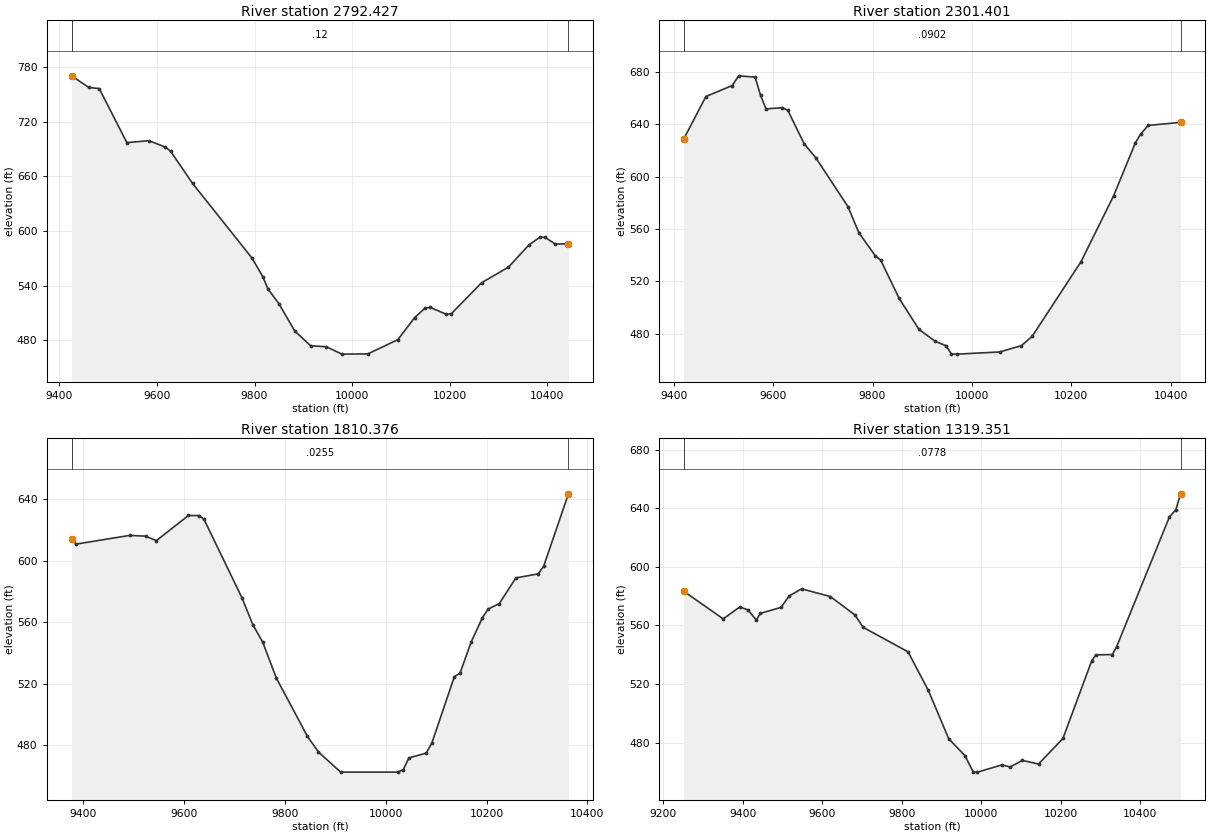
Type RM Length L Ch R = 1 ,2792.427,491.025400,491.025400,491.025400
XS GIS Cut Line= 6
 490158.31301952808404.807821498 490223.79956722808528.077933681
490296.434686067808673.224861979490356.679216019808805.078986494
490389.174477415808885.410878772490557.243590351809340.137625132
#Sta/Elev= 30
9424.962  770.699460.531757.88489481.797756.64889538.415697.1879 9583.47699.3184
9617.017 692.4279628.199687.61889672.928652.39189794.772570.24839816.761549.8917
9827.755535.97639849.744520.19339882.521489.95119914.883473.75499947.244472.5783
 9979.29464.5095 10032.4464.778210093.84480.467910128.23504.771410149.58515.2622
10160.25515.850510192.28508.545710202.95508.793810265.35543.083410320.37560.1941
10363.07585.045610384.42592.942110395.09593.097710416.44 585.56510443.28585.9139
#Mann= 3 , 0 , 0
9424.962    0.12       09424.962    0.12       010443.28    0.12       0
#XS Ineff= 2 , 0
       0                               0
Bank Sta=9424.962,10443.28
Exp/Cntr=0.3,0.1

Type RM Length L Ch R = 1 ,2301.401,491.025400,491.025400,491.025400
XS GIS Cut Line= 6
489714.253599559808584.225768956489922.738629753809039.119312616
489953.645685977809113.958620393489990.187576361809202.250026381
490112.139288501809477.401366438490121.126384415809498.290018513
#Sta/Elev= 30
9419.635628.69719464.488661.32359517.433669.7288 9530.49677.1424 9563.49676.1518
9574.491662.19479585.491651.81399618.492652.80379629.492650.68339662.493625.0586
9685.443614.61329750.494577.09029772.495  557.119805.496539.49359816.496536.0783
9853.453506.97599893.498483.13619926.393473.99589948.036470.69069958.857464.2418
9969.679464.237910056.24465.902310099.56470.701910121.44 477.83510219.88534.9995
10285.51585.468510329.26625.9088 10340.2632.718910355.22639.210910420.26641.5141
#Mann= 3 , 0 , 0
9419.635  0.0902       09419.635  0.0902       010420.26  0.0902       0
#XS Ineff= 2 , 0
       0                               0
Bank Sta=9419.635,10420.26
Exp/Cntr=0.3,0.1

Type RM Length L Ch R = 1 ,1810.376,491.025400,491.025400,491.025400
XS GIS Cut Line= 6
489288.581989854808756.214298129489384.538580387 809031.47194985
489442.267724911809181.322388296489483.210060119809269.784331477
489608.904446445809512.830148743489676.072221276809659.683286485
#Sta/Elev= 30
9377.625614.3805 9386.93610.89159492.832616.53039524.602616.05829545.783613.1262
9609.324629.50789630.505629.43619640.152627.0433 9715.53575.87229736.851558.5393
9756.638547.06139783.444523.83599844.803486.07299866.841475.74419910.917462.5975
10023.64462.600110034.98464.159510046.32471.867610080.33474.926810091.67481.4685
10136.36524.740810147.51526.937110169.82547.424210192.05563.140910203.25568.6405
10225.25 572.16110258.25588.898510302.26591.516810313.26 596.46710362.35643.5796
#Mann= 3 , 0 , 0
9377.625  0.0255       09377.625  0.0255       010362.35  0.0255       0
#XS Ineff= 2 , 0
       0                               0
Bank Sta=9377.625,10362.35
Exp/Cntr=0.3,0.1

Type RM Length L Ch R = 1 ,1319.351,0.000000,0.000000,0.000000
XS GIS Cut Line= 6
 488864.62107442808679.560797106488977.948705465809089.626340762
 489060.98867026809440.851883117489098.229169206809624.001816822
489124.198746384809717.375679251489185.194027054809886.186996932
#Sta/Elev= 30
9251.351583.36499350.759564.4474 9392.35572.55129413.145570.5982 9433.94563.6573
9444.337 568.2029496.237572.28869516.919580.12039547.942584.95049620.329 579.686
9682.338567.08489702.884 558.6629815.734541.95779866.887515.5651 9918.04482.6334
9959.082471.02069979.829459.83899990.202459.835810052.24464.799210072.61 463.338
10103.18467.853210143.92465.351610205.26482.799810277.68535.792910288.06539.8513
10329.71540.114810340.26545.389210473.16634.0112 10489.2 638.875 10501.2649.7931
#Mann= 3 , 0 , 0
9251.351  0.0778       09251.351  0.0778       0 10501.2  0.0778       0
#XS Ineff= 2 , 0
       0                               0
Bank Sta=9251.351,10501.2
Exp/Cntr=0.3,0.1